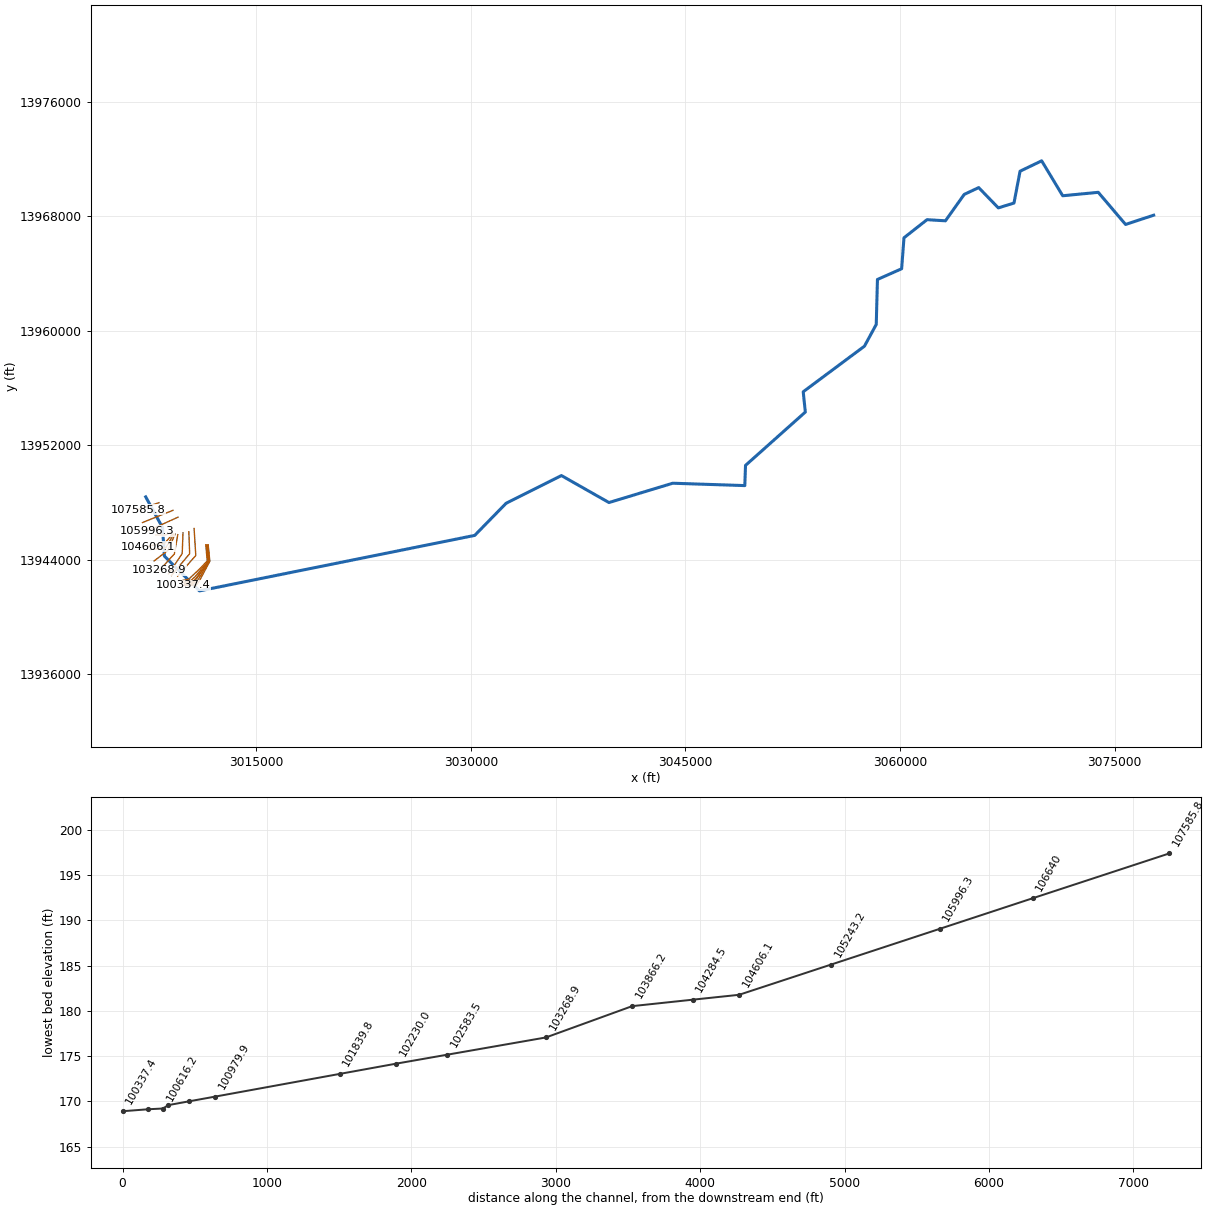
--- M100-00-00.prj (project) ---

Proj Title=M100-00-00
Current Plan=p01
Default Exp/Contr=.3,.1
English Units
Geom File=g01
Flow File=f01
Flow File=f02
Plan File=p01
Plan File=p02
Y Axis Title=Elevation
X Axis Title(PF)=Main Channel Distance
X Axis Title(XS)=Station
BEGIN DESCRIPTION:
HCFCD MODEL SUMMARY METADATA
The purpose of this summary is to document the high points of hydrologic and hydraulic models filed within the HCFCD Model and Map Management (M3) system.  The document includes references to the project that prompted the creation or update of the model.
DESCRIPTION OF PROJECT:
The following model was the hydraulic model which represented the effective condition of Harris County’s watersheds.
PURPOSE OF PROJECT:
Development of effective models to support the National Flood Insurance Program.
HCFCD Watershed Unit ID: M
M3 Study Identifier: 2007_Effective_M
Engineer: HCFCD
Project Name: EffectiveFEMA Study for watershed Willow Creek (M)
Study Completion Date: 6/18/2007
FEMA Case Number: [No Data]
FEMA Approval Date: [No Date in Database]
Vertical Datum: NAVD 1988
Datum Note: 2001 ADJ
HYDRAULICS
HCFCD Unit No.:  M100-00-00
Hydraulic Program Name: HEC-RAS
Hydraulic Program Version: 3.0.1
Steady Hydraulic Model: Yes
Unsteady Hydraulic Model: No
Update1:
The effective FEMA hydraulic model for unit number M100-00-00 has been updated by FEMA LOMR 07-06-1888P with an effective date of 7/25/2007.
Update2:
The effective FEMA hydraulic model for unit number M100-00-00 has been updated by FEMA LOMR 07-06-2077P with an effective date of 10/30/2008.
Update3:
The effective FEMA hydraulic model for unit number M100-00-00 has been updated by FEMA LOMR 12-06-2603P with an effective date of 1/28/2013.
Update4:
The effective FEMA hydraulic model for unit number M100-00-00 has been updated by FEMA LOMR 15-06-0175P with an effective date of 8/26/2015.
Update5:
The effective FEMA hydraulic model for unit number M100-00-00 has been pulled back to FEMA LOMR 12-06-2603P with an effective date of 1/28/2013.
The GIS cross sections have been updated to reflect the new regulatory water surface elevations from 15-06-0175P with an effective date of 8/26/2015.
Update6:
The effective FEMA hydraulic model for unit number M100-00-00 has been updated by FEMA LOMR 15-06-0921P with an effective date of 6/29/2016.
Update 7:
The effective FEMA hydraulic model for unit number M100-00-00 has been updated by FEMA LOMR 16-06-4206P with an effective date of 9/18/2017.
Update 8:
The effective FEMA hydraulic model for unit number M100-00-00 has been updated by FEMA LOMR 16-06-3930P with an effective date of 9/25/2017.
END DESCRIPTION:
DSS File=dss
DSS Export Rating Curves= 0
DSS Export Rating Curve Sorted= 0
DSS Export Volume Flow Curves= 0
DXF Filename=..\..\Willow Creek LOMR Submittal CD 031215\Models\Hydraulics\M100_00_00.
DXF OffsetX= 0
DXF OffsetY= 0
DXF ScaleX= 1
DXF ScaleY= 10

--- M100-00-00.p01 (plan) ---

Plan Title=Effective Multi-Profile Sept 30 2017
Version=Version 3.0.1  May 2012
Short Identifier=Eff+LOMR MP
Geom File=g01
Flow File=f01
Subcritical Flow
K Sum by GR= 0
Std Step Tol= 0.01
Critical Tol= 0.01
Num of Std Step Trials= 20
Max Error Tol= 0.3
Flow Tol Ratio= 0.001
Split Flow NTrial= 30
Split Flow Tol= 0.02
Split Flow Ratio= 0.02
Log Output Level= 0
Friction Slope Method= 1
Unsteady Friction Slope Method= 2
Parabolic Critical Depth
Global Vel Dist= 0 , 0 , 0
Global Log Level= 0
CheckData=True
Encroach Param=-1 ,0,0, 0
BEGIN DESCRIPTION:
FEMA Effective June 2007 + LOMR 07-06-1888P + LOMR 07-06-2077P + LOMR 12-06-2603P + LOMR 15-06-0921P + LOMR 16-06-4206P + LOMR 16-06-3930P
END DESCRIPTION:
Computation Interval=1HOUR
Output Interval=1HOUR
Run HTab= 0
Run UNet= 0
Run PostProcess= 0
UNET Theta= 1
UNET ZTol= 0.02
UNET ZSATol= 0.1
UNET MxIter= 20
UNET MaxInSteps= 20
UNET DtIC= 0
UNET DtMin= 0
UNET MaxCRTS= 20
UNET WFStab= 2
UNET SFStab= 1
UNET WFX= 1
UNET SFX= 1
UNET Convert EG Bridges=-1
UNET Use Existing IB Tables=-1
Instantaneous Interval=1HOUR
Write IC File= 0
IC Time=0
Write Velocity= 0
Write Detailed= 0

--- M100-00-00.p02 (plan) ---

Plan Title=Effective Floodway Sept 30 2017
Version=Version 3.0.1  May 2012
Short Identifier=Eff+LOMR FW
Geom File=g01
Flow File=f02
Subcritical Flow
K Sum by GR= 0
Std Step Tol= 0.01
Critical Tol= 0.01
Num of Std Step Trials= 20
Max Error Tol= 0.3
Flow Tol Ratio= 0.001
Split Flow NTrial= 30
Split Flow Tol= 0.02
Split Flow Ratio= 0.02
Log Output Level= 0
Friction Slope Method= 1
Unsteady Friction Slope Method= 2
Parabolic Critical Depth
Global Vel Dist= 0 , 0 , 0
Global Log Level= 0
CheckData=True
Encroach Param=-1 ,0,0, 2
Encroach River=M100-00-00
Encroach Reach=M100-00-00_0006
Encroach Node=107585.8
       1    4930    5100
Encroach Node=106640
       1    4900    5090
Encroach Node=105996.3
       1    4905    5110
Encroach Node=105243.2
       1    4880    5155
Encroach Node=104606.1
       1    4765 5126.91
Encroach Node=104284.5
       1    4680 5142.98
Encroach Node=103866.2
       1    4570 5011.06
Encroach Node=103268.9
       1    4560 5027.45
Encroach Node=102583.5
       1    4780 5130.26
Encroach Node=102230.0
       1    4800    5110
Encroach Node=101839.8
       1    4790    5125
Encroach Node=100979.9
       1 4748.97    5155
Encroach Node=100799.5
       1    4550    5210
Encroach Node=100655.2
       1    4610    5160
Encroach Node=100635.7
       1    4610    5160
Encroach Node=100616.2
       1    4610    5160
Encroach Node=100516.2
       1    4640    5155
Encroach Node=100337.4
       1    4620    5145
Encroach Node=100236.7
       1    4550 4724.59
Encroach Node=100205.7
       1    4550 4724.59
Encroach Node=100174.7
       1    4550 4724.59
Encroach Node=99984.3
       1    4660  5024.8
Encroach Node=99101.3
       1    4825    5230
Encroach Node=98759.7
       1    4830    5230
Encroach Node=98461.3
       1    4880    5290
Encroach Node=98125.2
       1    4855    5330
Encroach Node=97828.9
       1    4850    5675
Encroach Node=97649.3
       1    4780    5910
Encroach Node=97633.3
       1    4780    5910
Encroach Node=97617.3
       1    4780    5910
Encroach Node=97477.7
       1    4625    6190
Encroach Node=96805.8
       1    4600    5900
Encroach Node=96339.7
       1    3885    5380
Encroach Node=96322.2
       1    3885    5380
Encroach Node=96304.7
       1    3885    5380
Encroach Node=95855.3
       1    4580    5900
Encroach Node=95168.4
       1    4290    5900
Encroach Node=94029.1
       1    3820    5785
Encroach Node=92513.6
       1  3860.5    5310
Encroach Node=91781.8
       1    3880    5355
Encroach Node=90312.5
       1    2455    5250
Encroach Node=89034.1
       1    2235    5415
Encroach Node=87905.9
       1    2260    5635
Encroach Node=86715.9
       1    2720    5940
Encroach Node=86219.1
       1    2840    6045
Encroach Node=85963.3
       1  3005.8  6054.8
Encroach Node=85883
       1  3133.9  6069.9
Encroach Node=85707.6
       1    3262    6085
Encroach Node=85451.9
       1    3400    6160
Encroach Node=85326.6
       1    3400    6160
Encroach Node=85297.6
       1  3439.8    6160
Encroach Node=85150.1
       1    3770    5825
Encroach Node=84470.6
       1    3970    5835
Encroach Node=84400
       1    4010  5737.5
Encroach Node=84090
       1    4051    5638
Encroach Node=83424.1
       1    4140    5260
Encroach Node=82544.2
       1    4250    5380
Encroach Node=81921.5
       1    4190    5305
Encroach Node=81334.1
       1    4115    5365
Encroach Node=81233.8
       1    4075    5320
Encroach Node=81208.7
       1    4075    5320
Encroach Node=81183.6
       1    4075    5320
Encroach Node=81037.0
       1    4000    5260
Encroach Node=80324.7
       1    3790    5245
Encroach Node=79204.5
       1    3870    5560
Encroach Node=78020.2
       1    3905    5400
Encroach Node=76985.3
       1    4200    5520
Encroach Node=74697.9
       1    2425    5195
Encroach Node=74524.3
       1    2440    5140
Encroach Node=74508.8
       1    2440    5140
Encroach Node=74501
       1    2440    5140
Encroach Node=74233.9
       1    3705    5165
Encroach Node=73313.5
       1    3530    5280
Encroach Node=72146.3
       1  4479.7  5699.7
Encroach Node=70922.7
       1    4720    5165
Encroach Node=70851.2
       1  4862.6  5115.6
Encroach Node=70810.7
       1    4868    5121
Encroach Node=70807.7
       1    4868    5121
Encroach Node=70714.6
       1    4905    5167
Encroach Node=70589.7
       1    4899    5227
Encroach Node=70579.7
       1    4903    5231
Encroach Node=70561.3
       1    4903    5231
Encroach Node=70484.7
       1    4887    6251
Encroach Node=70158.3
       1  4622.9  6345.9
Encroach Node=68779.1
       1    3810    5530
Encroach Node=67642.9
       1    3505    5235
Encroach Node=65795.8
       1    4275    5200
Encroach Node=63393.8
       1    4325    5255
Encroach Node=61700.6
       1    4380    5255
Encroach Node=60586.2
       1    4660    5465
Encroach Node=59477.2
       1    3875    4925
Encroach Node=59459.2
       1    3875    4925
Encroach Node=59441.2
       1    3875    4925
Encroach Node=58914.9
       1    4130    5400
Encroach Node=58463.1
       1    4630    5645
Encroach Node=58365.5
       1    4700    5730
Encroach Node=58337.5
       1    4700    5730
Encroach Node=58309.5
       1    4700    5730
Encroach Node=58160.5
       1    4690 5926.01
Encroach Node=57612.0
       1    4460    5940
Encroach Node=55520.8
       1    4100    5300
Encroach Node=53968.4
       1    4695    5600
Encroach Node=53485.6
       1    4854    5686
Encroach Node=52902.9
       1    4572    5332
Encroach Node=52568.6
       1    4728    5439
Encroach Node=52453
       1    4820    5519
Encroach Node=52260
       1    4872    5537
Encroach Node=52013.9
       1    4810    5450
Encroach Node=51946.8
       1    4760    5405
Encroach Node=51639.6
       1    4615    5205
Encroach Node=50975.9
       1    4657    5272
Encroach Node=50016.2
       1    4873    5458
Encroach Node=49240.9
       1    4700    5195
Encroach Node=49198.6
       1    4695    5195
Encroach Node=48307.4
       1    4790    5415
Encroach Node=47406.9
       1    4265    5165
Encroach Node=46234.5
       14524.9995393.999
Encroach Node=46134.5
       1 4642.015456.999
Encroach Node=45834.5
       14715.9995423.999
Encroach Node=45734.5
       14715.9995423.999
Encroach Node=45634.5
       14744.9995454.999
Encroach Node=44176.8
       1    4185    5225
Encroach Node=43675.5
       14494.9995099.999
Encroach Node=43575.5
       1    4570    5055
Encroach Node=43154.5
       1  4874.1  5081.9
Encroach Node=43104.0
       1  4874.1  5081.9
Encroach Node=43053.5
       1  4874.1  5081.9
Encroach Node=42695.9
       1    4760    5310
Encroach Node=40656.7
       1    4265    5340
Encroach Node=40269.2
       1    4250    5270
Encroach Node=40240.2
       1    4250    5270
Encroach Node=40211.2
       1    4250    5270
Encroach Node=39949.4
       1 4424.98    5255
Encroach Node=39547.0
       1    4385    5345
Encroach Node=37581.6
       1    4450    5340
Encroach Node=36848.4
       1    4350  5040.1
Encroach Node=36544.0
       1    4600    5290
Encroach Node=36494.0
       1    4650    5290
Encroach Node=36484.0
       1    4650    5290
Encroach Node=36474.0
       1    4670    5250
Encroach Node=36424.0
       1    4660    5270
Encroach Node=33999.1
       1    4470    5490
Encroach Node=33123.8
       1    4957    6100
Encroach Node=31989.5
       1    4765    5700
Encroach Node=30984.1
       1    4650    5185
Encroach Node=30442.6
       1    4905    5084
Encroach Node=30409.1
       1    4905    5084
Encroach Node=30375.6
       1    4905    5084
Encroach Node=30311.7
       1    4892    5103
Encroach Node=30295.7
       1    4892    5103
Encroach Node=30279.7
       1    4892    5103
Encroach Node=30080.5
       1    4940    5240
Encroach Node=29955.1
       1    4920    5230
Encroach Node=29734.1
       1    4675    5072
Encroach Node=29698.1
       1    4675    5072
Encroach Node=29662.1
       1    4675    5072
Encroach Node=29255.9
       1    4500 5222.45
Encroach Node=27862.6
       1    4210    5155
Encroach Node=26111.5
       1    4785    5485
Encroach Node=24673.4
       1    4145 5113.39
Encroach Node=23156.8
       1    4745    5440
Encroach Node=21788.5
       1    4735    5275
Encroach Node=20391.1
       1    4905    5625
Encroach Node=19464.0
       1    4715    5345
Encroach Node=17773.6
       1    4515    5420
Encroach Node=17250.8
       1    4640    5140
Encroach Node=16516.8
       1    4710  5036.7
Encroach Node=15781.7
       1    4410    5330
Encroach Node=15743.6
       1    4410    5330
Encroach Node=15729.0
       1    4410    5330
Encroach Node=15714.4
       1    4410    5330
Encroach Node=15668.1
       1    4485    5330
Encroach Node=14512.1
       1    4450    5080
Encroach Node=13913.8
       1    4755    5175
Encroach Node=13811.9
       1    4700    5100
Encroach Node=13626.9
       1    4650    5090
Encroach Node=13515.3
       1    4705 5101.67
Encroach Node=13488.2
       1    4705 5101.67
Encroach Node=13461.2
       1    4705 5101.67
Encroach Node=13425.6
       1    4700    5120
Encroach Node=13412.1
       1    4700    5120
Encroach Node=13398.7
       1    4700    5120
Encroach Node=13208.9
       1    4725    5160
Encroach Node=13134.4
       1    4725    5185
Encroach Node=12731.6
       1    4800    5300
Encroach Node=11328.1
       1  4903.8    5375
Encroach Node=10539.7
       1 4601.78    5140
Encroach Node=10424.9
       1    4670    5170
Encroach Node=10410.3
       1    4670    5170
Encroach Node=10395.7
       1    4670    5170
Encroach Node=10197.7
       1    4730    5290
Encroach Node=9093.6
       1 4783.53    5120
Encroach Node=7228.8
       1    4375    5135
Encroach Node=7141.2
       1    4300    5170
Encroach Node=7112.7
       1    4300    5170
Encroach Node=7084.2
       1    4300    5170
Encroach Node=6957.7
       1    4310    5125
Encroach Node=5933.4
       1    4825    5455
Encroach Node=3712.1
       1    4780 5190.57
Encroach Node=2600.3
       1 4588.49    5170
Encroach Node=584.5
       1 4833.82    5420
BEGIN DESCRIPTION:
FEMA Effective June 2007 + LOMR 07-06-1888P + LOMR 07-06-2077P + LOMR 12-06-2603P + LOMR 15-06-0921P + LOMR 16-06-4206P + LOMR 16-06-3606P
END DESCRIPTION:
Computation Interval=1HOUR
Output Interval=1HOUR
Run HTab= 0
Run UNet= 0
Run PostProcess= 0
UNET Theta= 1
UNET ZTol= 0.02
UNET ZSATol= 0.1
UNET MxIter= 20
UNET MaxInSteps= 20
UNET DtIC= 0
UNET DtMin= 0
UNET MaxCRTS= 20
UNET WFStab= 2
UNET SFStab= 1
UNET WFX= 1
UNET SFX= 1
UNET Convert EG Bridges=-1
UNET Use Existing IB Tables=-1
Instantaneous Interval=1HOUR
Write IC File= 0
IC Time=0
Write Velocity= 0
Write Detailed= 0

--- M100-00-00.f01 (steady flow) ---

Flow Title=Effective Sept 2017
Version=Version 3.0.1  May 2012
Number of Profiles= 4
Profile Names=10PCT_10yr,2PCT_50yr, 1PCT_100yr,0.2PCT_500yr
River Rch & RM=M100-00-00,M100-00-00_0006 ,107585.8
     716    1183    1417    2113
River Rch & RM=M100-00-00,M100-00-00_0006 ,103268.9
     750    1190    1420    2230
River Rch & RM=M100-00-00,M100-00-00_0006 ,98759.7
     758    1197    1419    2262
River Rch & RM=M100-00-00,M100-00-00_0006 ,97649.3
    1610    2710    3300    5030
River Rch & RM=M100-00-00,M100-00-00_0006 ,96339.7
    1600    2730    3350    5160
River Rch & RM=M100-00-00,M100-00-00_0006 ,92513.6
    1600    2730    3390    5240
River Rch & RM=M100-00-00,M100-00-00_0006 ,91781.8
    1580    2750    3470    5450
River Rch & RM=M100-00-00,M100-00-00_0006 ,87905.9
    1566    2773    3555    5679
River Rch & RM=M100-00-00,M100-00-00_0006 ,85297.6
    2260    4030    5230    8880
River Rch & RM=M100-00-00,M100-00-00_0006 ,76985.3
    2286    4198    5404    9296
River Rch & RM=M100-00-00,M100-00-00_0006 ,74233.9
    3063    5606    7143   11903
River Rch & RM=M100-00-00,M100-00-00_0006 ,70922.7
    2960    5430    6910   11690
River Rch & RM=M100-00-00,M100-00-00_0006 ,67642.9
    2810    5180    6590   11390
River Rch & RM=M100-00-00,M100-00-00_0006 ,63393.8
    2700    4980    6340   11150
River Rch & RM=M100-00-00,M100-00-00_0006 ,61700.6
    2619    4847    6164   10984
River Rch & RM=M100-00-00,M100-00-00_0006 ,60586.2
    2889    5338    6784   12484
River Rch & RM=M100-00-00,M100-00-00_0006 ,59477.2
    2910    5390    6850   12500
River Rch & RM=M100-00-00,M100-00-00_0006 ,49198.6
    2918    5435    6903   12514
River Rch & RM=M100-00-00,M100-00-00_0006 ,44176.8
    2990    5633    7174   13050
River Rch & RM=M100-00-00,M100-00-00_0006 ,33999.1
    3227    5731    7327   13371
River Rch & RM=M100-00-00,M100-00-00_0006 ,26111.5
    3953    7006    8656   14041
River Rch & RM=M100-00-00,M100-00-00_0006 ,21788.5
    4015    7106    8811   14353
River Rch & RM=M100-00-00,M100-00-00_0006 ,15781.7
    4300    7700    9600   15700
River Rch & RM=M100-00-00,M100-00-00_0006 ,13515.3
    4500    7900    9800   16100
River Rch & RM=M100-00-00,M100-00-00_0006 ,10424.9
    4600    8100   10100   16600
River Rch & RM=M100-00-00,M100-00-00_0006 ,7141.2
    4766    8410   10480   17205
River Rch & RM=M100-00-00,M100-00-00_0006 ,584.5
    4979    8769   10929   17974
Boundary for River Rch & Prof#=M100-00-00,M100-00-00_0006 , 1
Up Type= 0
Dn Type= 3
Dn Slope=.0025
Boundary for River Rch & Prof#=M100-00-00,M100-00-00_0006 , 2
Up Type= 0
Dn Type= 3
Dn Slope=.0025
Boundary for River Rch & Prof#=M100-00-00,M100-00-00_0006 , 3
Up Type= 0
Dn Type= 3
Dn Slope=.0025
Boundary for River Rch & Prof#=M100-00-00,M100-00-00_0006 , 4
Up Type= 0
Dn Type= 3
Dn Slope=.0025
DSS Import GetInterval= 0
DSS Import GetPeak= 0
DSS Import FillOption= 0

--- M100-00-00.f02 (steady flow) ---

Flow Title=Effective Floodway Sept30 2017
Version=Version 3.0.1  May 2012
Number of Profiles= 2
Profile Names=1PCT_100yr,1PCTFloodway_100yr
River Rch & RM=M100-00-00,M100-00-00_0006 ,107585.8
    1417    1417
River Rch & RM=M100-00-00,M100-00-00_0006 ,103268.9
    1420    1420
River Rch & RM=M100-00-00,M100-00-00_0006 ,98759.7
    1419    1419
River Rch & RM=M100-00-00,M100-00-00_0006 ,97649.3
    3300    3300
River Rch & RM=M100-00-00,M100-00-00_0006 ,96339.7
    3350    3350
River Rch & RM=M100-00-00,M100-00-00_0006 ,92513.6
    3390    3390
River Rch & RM=M100-00-00,M100-00-00_0006 ,91781.8
    3470    3470
River Rch & RM=M100-00-00,M100-00-00_0006 ,87905.9
    3555    3555
River Rch & RM=M100-00-00,M100-00-00_0006 ,85297.6
    5230    5230
River Rch & RM=M100-00-00,M100-00-00_0006 ,76985.3
    5404    5404
River Rch & RM=M100-00-00,M100-00-00_0006 ,74233.9
    7143    7143
River Rch & RM=M100-00-00,M100-00-00_0006 ,70922.7
    6910    6910
River Rch & RM=M100-00-00,M100-00-00_0006 ,67642.9
    6590    6590
River Rch & RM=M100-00-00,M100-00-00_0006 ,63393.8
    6340    6340
River Rch & RM=M100-00-00,M100-00-00_0006 ,61700.6
    6164    6164
River Rch & RM=M100-00-00,M100-00-00_0006 ,60586.2
    6784    6784
River Rch & RM=M100-00-00,M100-00-00_0006 ,59477.2
    6850    6850
River Rch & RM=M100-00-00,M100-00-00_0006 ,49198.6
    6903    6903
River Rch & RM=M100-00-00,M100-00-00_0006 ,44176.8
    7174    7174
River Rch & RM=M100-00-00,M100-00-00_0006 ,33999.1
    7327    7327
River Rch & RM=M100-00-00,M100-00-00_0006 ,26111.5
    8656    8656
River Rch & RM=M100-00-00,M100-00-00_0006 ,21788.5
    8811    8811
River Rch & RM=M100-00-00,M100-00-00_0006 ,15781.7
    9600    9600
River Rch & RM=M100-00-00,M100-00-00_0006 ,13515.3
    9800    9800
River Rch & RM=M100-00-00,M100-00-00_0006 ,10424.9
   10100   10100
River Rch & RM=M100-00-00,M100-00-00_0006 ,7141.2
   10480   10480
River Rch & RM=M100-00-00,M100-00-00_0006 ,584.5
   10929   10929
Boundary for River Rch & Prof#=M100-00-00,M100-00-00_0006 , 1
Up Type= 0
Dn Type= 3
Dn Slope=.0025
Boundary for River Rch & Prof#=M100-00-00,M100-00-00_0006 , 2
Up Type= 0
Dn Type= 1
Dn Known WS=108.31
DSS Import GetInterval= 0
DSS Import GetPeak= 0
DSS Import FillOption= 0

--- M100-00-00.g01 (geometry) ---

Geom Title=M100-00-00
Version=Version 3.0.1  May 2012

River Reach=M100-00-00      ,M100-00-00_0006
Reach XY= 30
      3007265.56     13948390.39      3008438.41     13946250.83
      3008575.91     13944247.38      3011022.96     13941819.42
      3030265.94     13945698.61      3032461.05     13947944.38
      3036328.53     13949881.76      3039652.19     13947994.76
      3044109.78     13949346.17      3049148.85     13949180.37
      3049197.46     13950591.83      3053379.22     13954320.74
      3053232.54     13955740.72      3057512.87     13958927.11
      3058337.52     13960447.07      3058421.72      13963590.3
       3060112.7     13964339.43      3060276.76     13966505.23
      3061888.82     13967771.84       3063175.2     13967691.43
       3064487.7     13969537.35      3065499.85     13970013.05
      3066872.25     13968594.64        3067966.     13968933.18
       3068391.5     13971158.79      3069901.92     13971885.36
      3071372.88      13969442.8      3073857.25     13969683.26
      3075767.77     13967437.72        3077733.       13968084.

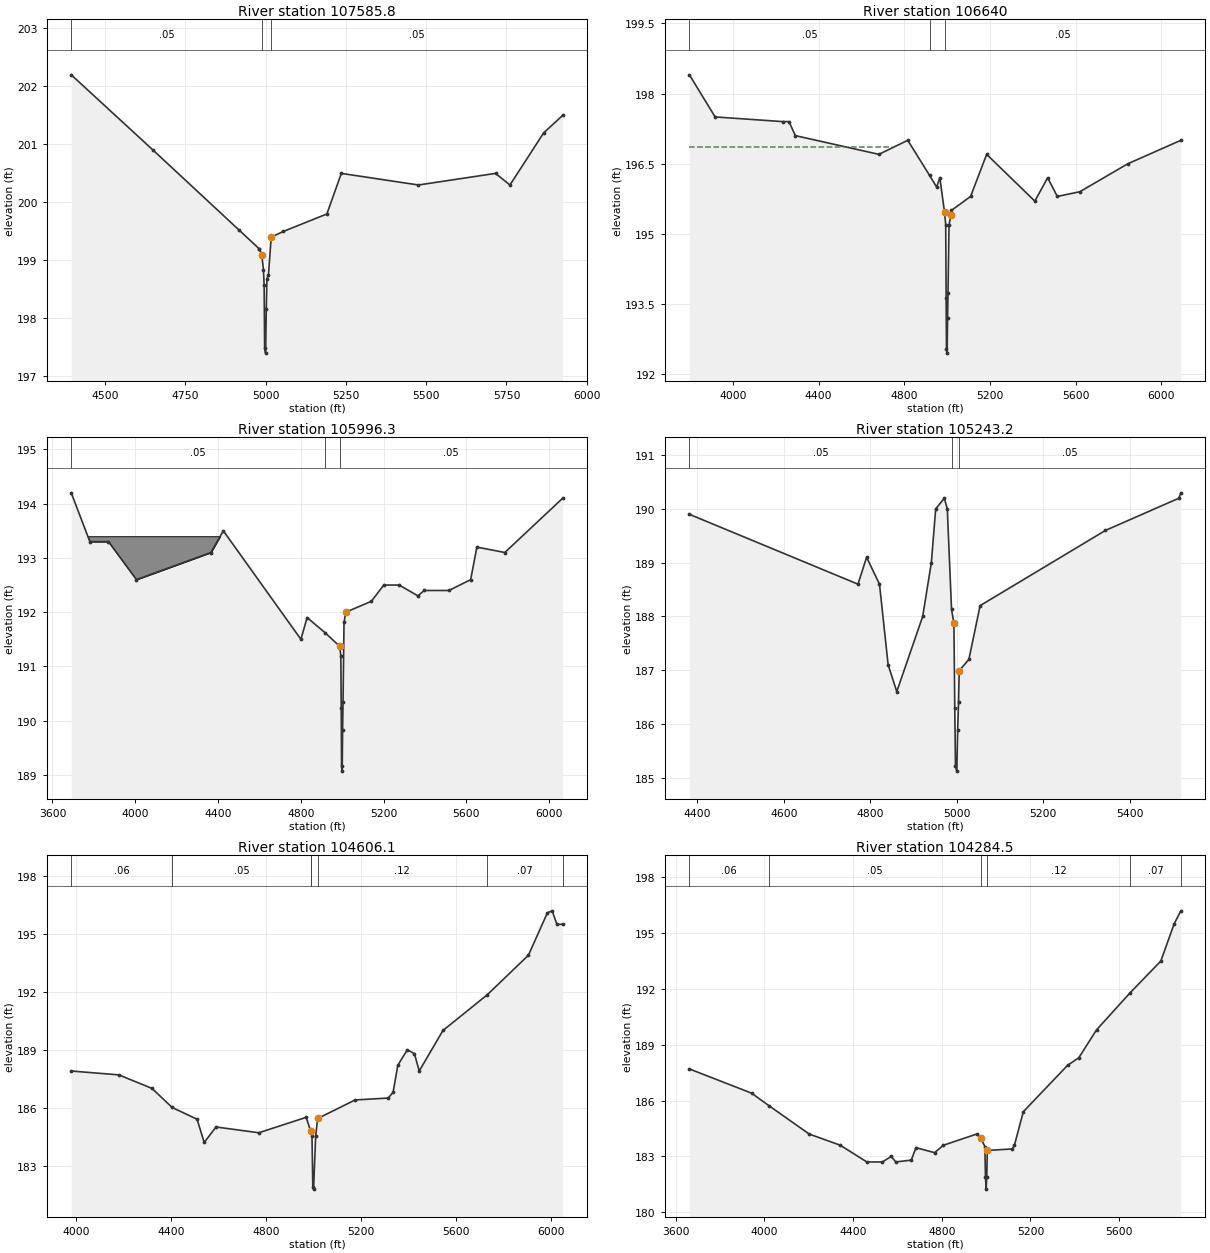
Type RM Length L Ch R = 1 ,107585.8,898.02,945.8,902.58
BEGIN DESCRIPTION:
Cross Section XS57
END DESCRIPTION:
XS GIS Cut Line= 2
      3008194.95      13947985.5      3006742.72      13947506.1
#Sta/Elev= 22
  4395.2   202.2  4650.2   200.9  4918.2  199.52  4980.2   199.2  4980.6   199.2
  4988.1   199.1  4993.6  198.84  4995.6  198.57  4997.2  197.49  5000.2   197.4
  5002.3  198.16  5004.3  198.68  5009.1  198.75  5017.6   199.4  5055.9   199.5
  5190.9   199.8  5235.9   200.5  5475.9   200.3  5715.9   200.5  5760.9   200.3
  5865.9   201.2  5924.9   201.5
#Mann= 3 ,-1 , 0
  4395.2     .05       0  4988.1     .07       0  5017.6     .05       0
Bank Sta=4988.1,5017.6
XS Rating Curve= 0
Exp/Cntr=.3,.1

Type RM Length L Ch R = 1 ,106640  ,635.53,643.7,642.95
BEGIN DESCRIPTION:
Cross Section XS56
END DESCRIPTION:
XS GIS Cut Line= 4
      3009171.28      13947450.1      3008074.87      13947015.6
       3008033.6      13946999.7      3007040.16      13946596.3
#Sta/Elev= 28
  3796.3   198.4  3916.3   197.5  4231.3   197.4  4261.3   197.4  4291.3   197.1
  4681.3   196.7  4816.3     197  4918.2  196.25  4951.3     196  4966.3   196.2
  4988.1  195.46  4993.6   195.2  4995.6  193.62  4997.2  192.54  5000.2  192.45
  5002.3  193.21  5004.3  193.73  5009.1  195.19  5017.6   195.4  5019.9   195.5
  5109.9   195.8  5184.9   196.7  5409.9   195.7  5469.9   196.2  5514.9   195.8
  5619.9   195.9  5844.9   196.5  6092.1     197
#Mann= 3 ,-1 , 0
  3796.3     .05       0  4918.2     .07       0  4988.1     .05       0
#XS Ineff= 2 , 0
       0    4745  196.85               0
Permanent Ineff=
       F       F
Bank Sta=4988.1,5017.6
XS Rating Curve= 0
Exp/Cntr=.3,.1

Type RM Length L Ch R = 1 ,105996.3,762.75,753.1,703.61
BEGIN DESCRIPTION:
Cross Section XS55
END DESCRIPTION:
XS GIS Cut Line= 4
      3009528.21      13946974.2      3008375.31      13946452.7
      3008302.27      13946419.7      3007357.21      13946011.2
#Sta/Elev= 28
  3690.7   194.2  3780.7   193.3  3870.7   193.3  4005.7   192.6  4365.7   193.1
  4425.7   193.5  4800.7   191.5  4830.7   191.9  4918.2  191.62  4988.1  191.37
  4993.6   191.2  4995.6  190.24  4997.2  189.16  5000.2  189.07  5002.3  189.83
  5004.3  190.35  5009.1  191.81  5017.6     192  5141.2   192.2  5201.2   192.5
  5276.2   192.5  5366.2   192.3  5396.2   192.4  5516.2   192.4  5621.2   192.6
  5651.2   193.2  5786.2   193.1  6065.8   194.1
#Mann= 3 ,-1 , 0
  3690.7     .05       0  4918.2     .07       0  4988.1     .05       0
#Block Obstruct= 2 , 0
       0    4430   193.4               0
Bank Sta=4988.1,5017.6
XS Rating Curve= 0
Exp/Cntr=.3,.1

Type RM Length L Ch R = 1 ,105243.2,598.85,637.1,607.44
BEGIN DESCRIPTION:
Cross Section XS54
END DESCRIPTION:
XS GIS Cut Line= 5
      3009068.73     13945925.92      3008672.97      13945734.1
      3008516.14     13945729.52      3008440.33     13945725.42
       3007975.9      13945725.7
#Sta/Elev= 24
  4381.6   189.9  4771.6   188.6  4791.6   189.1  4821.4   188.6  4841.4   187.1
  4861.4   186.6  4921.4     188  4941.4     189  4951.4     190  4971.4   190.2
  4978.3     190  4988.1  188.13  4993.6  187.87  4995.6  186.29  4997.2  185.21
  5000.2  185.12  5002.3  185.88  5004.3   186.4 5005.88  186.99  5028.3   187.2
  5054.2   188.2  5344.2   189.6  5514.2   190.2  5518.7   190.3
#Mann= 3 ,-1 , 0
  4381.6     .05       0  4988.1     .07       0 5005.88     .05       0
Bank Sta=4993.6,5005.88
XS Rating Curve= 0
Exp/Cntr=.3,.1

Type RM Length L Ch R = 1 ,104606.1,321.55,321.6,326.48
BEGIN DESCRIPTION:
Cross Section XS53
Cross Section 104606.1
Cross Section M100-00-00-X53
Located At: 4TH US JUERGEN
END DESCRIPTION:
XS GIS Cut Line= 4
      3009142.21     13945790.85      3008564.41     13945114.67
      3008258.53      13945125.4       3007410.2      13944914.2
#Sta/Elev= 30
  3979.7   187.9  4179.7   187.7  4319.7     187  4404.9  186.01  4509.7   185.4
  4539.7   184.2  4589.7     185  4769.7   184.7  4969.1   185.5  4987.4  184.81
  4988.1  184.79  4993.6  184.53  4997.2  181.87  5000.2  181.78  5009.1  184.52
  5017.6  185.44  5175.2   186.4  5315.2   186.5  5335.2   186.8  5355.2   188.2
  5395.2     189  5425.2   188.8  5445.2   187.9  5545.2     190  5730.9  191.84
  5905.2   193.9  5985.2   196.1  6005.2   196.2  6025.2   195.5  6049.4   195.5
#Mann= 7 ,-1 , 0
  3979.7     .06       0  4404.9     .05       0  4987.4     .12       0
  4988.1     .08       0  5017.6     .12       0  5730.9     .07       0
  6049.4      .2       0
Bank Sta=4988.1,5017.6
XS Rating Curve= 0
Exp/Cntr=.3,.1

Type RM Length L Ch R = 1 ,104284.5,235.77,418.3,494.47
BEGIN DESCRIPTION:
Cross Section xs52.5
END DESCRIPTION:
XS GIS Cut Line= 3
      3009226.28      13945787.3      3008670.49      13944832.2
      3007567.14      13944708.7
#Sta/Elev= 30
  3662.5   187.7  3942.5   186.4  4020.6  185.73  4202.5   184.2  4342.5   183.6
  4462.5   182.7  4532.5   182.7  4572.5     183  4592.5   182.7  4662.5   182.8
  4683.8  183.47  4767.6   183.2  4807.6   183.6  4957.6   184.2  4976.8  183.97
  4994.3  183.53  4997.1   181.9    5000  181.24  5002.9   181.9  5005.3  183.32
  5117.6   183.4  5127.6   183.6  5167.6   185.4  5367.6   187.9  5417.6   188.3
  5497.6   189.8  5648.8  191.79  5787.6   193.5  5847.6   195.5  5877.8   196.2
#Mann= 6 ,-1 , 0
  3662.5     .06       0  4020.6     .05       0  4976.8     .08       0
  5005.3     .12       0  5648.8     .07       0  5877.8      .2       0
Bank Sta=4976.8,5005.3
XS Rating Curve= 0
Exp/Cntr=.3,.1

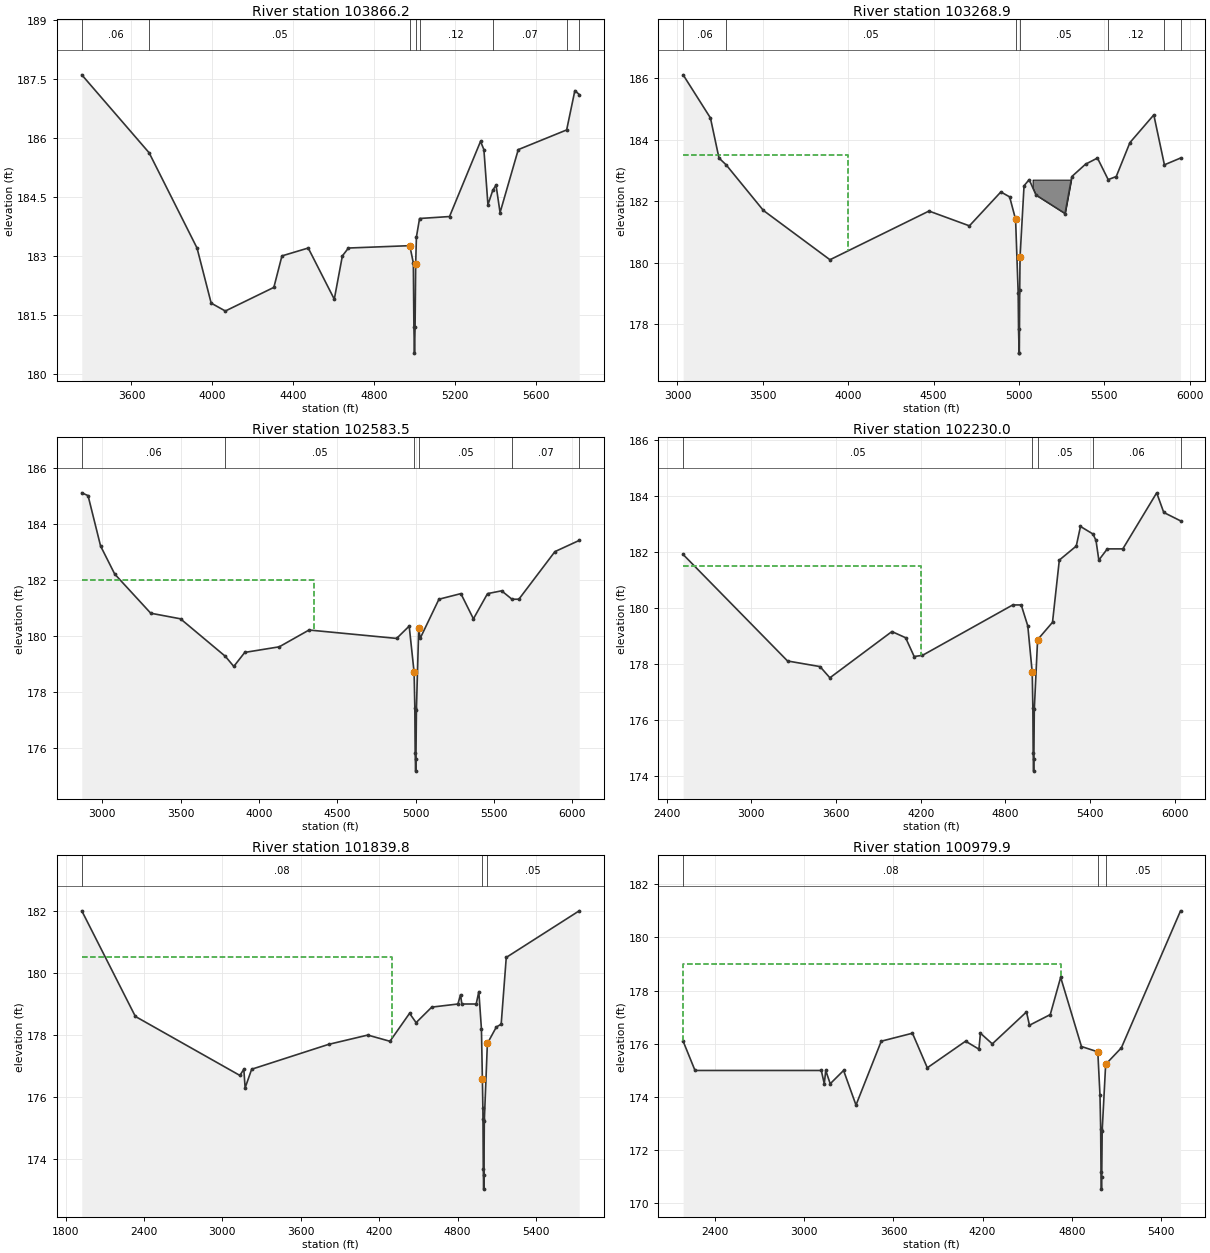
Type RM Length L Ch R = 1 ,103866.2,519.17,597.3,618.5
BEGIN DESCRIPTION:
Cross Section XS52
Cross Section 103866.2
Cross Section M100-00-00-X52
Located At: 2ND US JUERGEN
END DESCRIPTION:
XS GIS Cut Line= 3
      3009320.14      13945789.9       3008812.5      13944648.9
      3007850.74      13943912.2
#Sta/Elev= 30
  3354.4   187.6  3687.4  185.62  3924.4   183.2  3994.4   181.8  4064.4   181.6
  4304.4   182.2  4344.4     183  4474.4   183.2  4603.3   181.9  4643.3     183
  4673.3   183.2  4976.8  183.26  4994.3  182.82  4997.1  181.19    5000  180.53
  5002.9  181.19  5005.9  182.79  5009.5  183.48  5025.1  183.95  5173.3     184
  5326.7  185.91  5343.3   185.7  5363.3   184.3  5387.5  184.67  5403.3   184.8
  5423.3   184.1  5513.3   185.7  5752.6   186.2  5793.3   187.2  5814.7   187.1
#Mann= 8 ,-1 , 0
  3354.4     .06       0  3687.4     .05       0  4976.8     .08       0
  5005.9     .05       0  5025.1     .12       0  5387.5     .07       0
  5752.6     .12       0  5814.7      .2       0
Bank Sta=4976.8,5005.9
XS Rating Curve= 0
Exp/Cntr=.3,.1

Type RM Length L Ch R = 1 ,103268.9,442.32,685.4,579.22
BEGIN DESCRIPTION:
Cross Section XS51
Cross Section 103268.9
Cross Section M100-00-00-X51
Located At: 2ND US JUERGEN
END DESCRIPTION:
XS GIS Cut Line= 3
      3009507.04      13945749.6      3009268.56      13944403.8
      3008227.94      13943259.8
#Sta/Elev= 30
  3033.2   186.1  3193.2   184.7  3243.2   183.4  3285.1  183.18  3503.2   181.7
  3893.2   180.1  4473.2  181.68  4709.9   181.2  4894.1   182.3  4945.5  182.14
  4980.4  181.41  4995.5  179.02  4997.7  177.84  5001.3  177.07  5002.3  177.08
  5004.5  179.11  5006.6   180.2  5029.9   182.5  5059.9   182.7  5099.9   182.2
  5269.9   181.6  5309.9   182.8  5389.9   183.2  5459.9   183.4  5522.7   182.7
  5569.9   182.8  5649.9   183.9  5789.9   184.8    5852  183.18  5946.5   183.4
#Mann= 7 ,-1 , 0
  3033.2     .06       0  3285.1     .05       0  4980.4     .08       0
  5006.6     .05       0  5522.7     .12       0    5852     .07       0
  5946.5      .2       0
#XS Ineff= 2 , 0
       0    4000   183.5               0
Permanent Ineff=
       F       F
#Block Obstruct= 1 ,-1
    5080    5350   182.7
Bank Sta=4980.4,5006.6
XS Rating Curve= 0
Exp/Cntr=.3,.1

Type RM Length L Ch R = 1 ,102583.5,369.85,353.5,340.35
BEGIN DESCRIPTION:
Cross Section XS50.5
END DESCRIPTION:
XS GIS Cut Line= 3
      3009872.99      13945885.1      3009816.65      13944427.2
      3008858.82      13943004.6
#Sta/Elev= 30
  2869.8   185.1  2909.8     185  2989.8   183.2  3079.8   182.2  3309.8   180.8
  3499.8   180.6  3785.9  179.26  3839.8   178.9  3909.8   179.4  4129.8   179.6
  4319.8   180.2  4878.8   179.9    4959  180.34  4990.3  178.69  4994.9  177.43
  4997.1  175.82  5000.2  175.16  5002.1   175.6  5005.1  177.36  5019.8  180.26
  5028.8   179.9  5148.8   181.3  5288.8   181.5  5368.8   180.6  5458.8   181.5
  5548.8   181.6  5614.7   181.3  5658.8   181.3  5888.8     183  6043.8   183.4
#Mann= 6 ,-1 , 0
  2869.8     .06       0  3785.9     .05       0  4990.3     .08       0
  5019.8     .05       0  5614.7     .07       0  6043.8      .2       0
#XS Ineff= 2 , 0
       0    4350     182               0
Permanent Ineff=
       F       F
#Block Obstruct= 2 , 0
       0                    5335       0   181.1
Bank Sta=4990.3,5019.8
XS Rating Curve= 0
Exp/Cntr=.3,.1

Type RM Length L Ch R = 1 ,102230.0,410.11,390.2,377.72
BEGIN DESCRIPTION:
Cross Section XS50
Cross Section 102230.0
END DESCRIPTION:
XS GIS Cut Line= 3
      3010280.98      13945955.4      3010337.23      13944420.8
      3009063.88      13942892.8
#Sta/Elev= 30
  2516.7   181.9  3256.7   178.1  3486.7   177.9  3556.7   177.5  3996.1  179.15
  4093.2  178.93  4153.8  178.26  4212.4   178.3  4852.4   180.1  4912.4   180.1
    4959  179.35  4990.3   177.7  4994.9  176.44  4997.1  174.83  5000.2  174.17
  5002.1  174.61  5005.1  176.37  5028.5  178.86  5134.1  179.48  5182.4   181.7
  5302.4   182.2  5332.4   182.9  5420.9  182.63  5442.4   182.4  5462.4   181.7
  5522.4   182.1  5632.4   182.1  5872.4   184.1  5922.4   183.4  6041.4   183.1
#Mann= 5 ,-1 , 0
  2516.7     .05       0  4990.3     .08       0  5028.5     .05       0
  5420.9     .06       0  6041.4      .2       0
#XS Ineff= 2 , 0
       0    4200   181.5               0
Permanent Ineff=
       F       F
Bank Sta=4990.3,5028.5
XS Rating Curve= 0
Exp/Cntr=.3,.1

Type RM Length L Ch R = 1 ,101839.8,794.91,859.9,751.3
BEGIN DESCRIPTION:
Cross Section XS49.8
END DESCRIPTION:
XS GIS Cut Line= 3
      3010647.82     13946179.45      3010766.49     13944294.78
      3009500.13     13942854.01
#Sta/Elev= 30
  1924.6     182  2334.6   178.6  3134.6   176.7  3164.6   176.9  3174.6   176.3
  3224.6   176.9    3813   177.7    4113     178    4283   177.8    4433   178.7
    4483   178.4    4603   178.9    4803     179    4823   179.3    4833     179
    4943     179    4963   179.4    4983   178.2  4990.3  176.57    4994  175.65
  4994.9  175.31  4997.1   173.7  5000.2  173.04  5002.1  173.48  5005.1  175.24
  5028.5  177.73  5097.2  178.26  5134.1  178.35    5173   180.5  5731.2     182
#Mann= 3 ,-1 , 0
  1924.6     .08       0  4990.3     .08       0  5028.5     .05       0
#XS Ineff= 2 , 0
       0    4300   180.5               0
Permanent Ineff=
       F       F
Bank Sta=4990.3,5028.5
XS Rating Curve= 0
Exp/Cntr=.3,.1

Type RM Length L Ch R = 1 ,100979.9,180.3,180.4,192.83
BEGIN DESCRIPTION:
Cross Section XS49.7
END DESCRIPTION:
XS GIS Cut Line= 5
      3011463.99      13945033.6      3011565.54     13943914.68
      3011108.33     13943428.21      3010281.37      13942646.2
      3009872.39     13942556.31
#Sta/Elev= 30
  2184.5   176.1  2264.5     175  3114.5     175  3134.5   174.5  3144.5     175
  3174.5   174.5  3264.5     175    3348   173.7    3518   176.1    3728   176.4
    3828   175.1  4085.6   176.1  4175.6   175.8  4185.6   176.4  4265.6     176
  4495.6   177.2  4515.6   176.7  4655.6   177.1  4725.6   178.5  4865.6   175.9
  4975.6   175.7  4990.3  174.07  4994.9  172.81  4997.1   171.2  5000.2  170.54
  5002.1  170.98  5005.1  172.74  5028.5  175.23  5134.1  175.85  5532.5     181
#Mann= 3 ,-1 , 0
  2184.5     .08       0  4975.6     .08       0  5028.5     .05       0
#XS Ineff= 2 , 0
       0    4725     179               0
Permanent Ineff=
       F       F
Bank Sta=4975.6,5028.5
XS Rating Curve= 0
Exp/Cntr=.3,.1

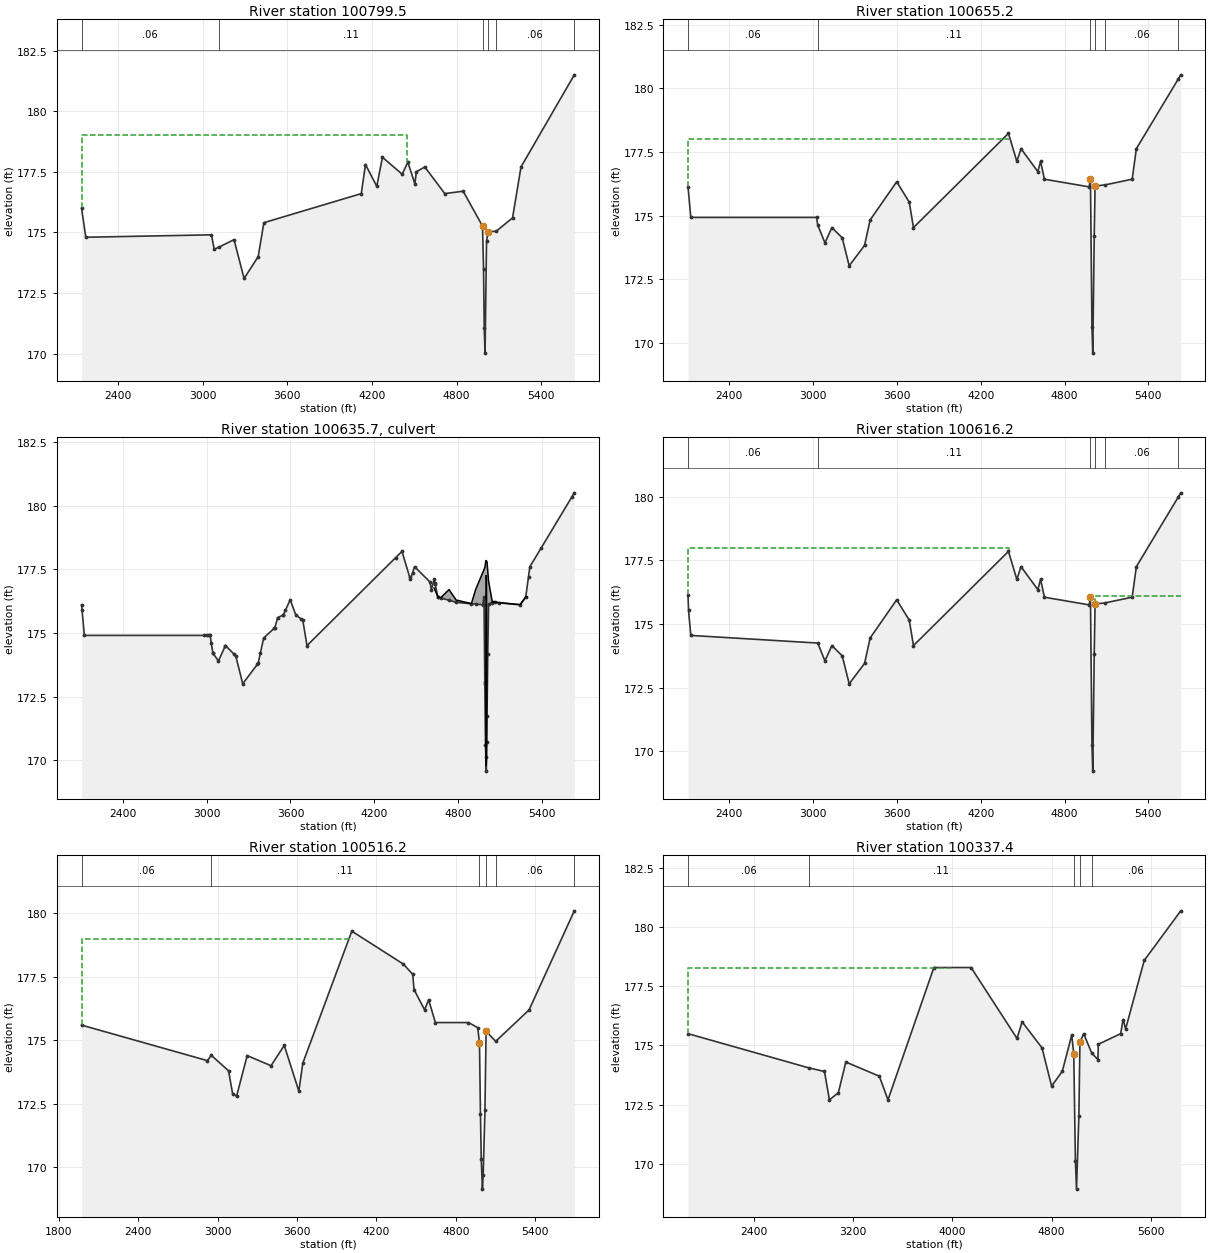
Type RM Length L Ch R = 1 ,100799.5,144.3,144.3,122
BEGIN DESCRIPTION:
Cross Section XS49.5
Cross Section 100799.5
END DESCRIPTION:
XS GIS Cut Line= 5
  3011517.00313113945024.3979087      3011622.97     13943897.93
      3010725.79     13942820.88      3010378.66     13942489.53
      3009905.29     13942426.41
#Sta/Elev= 30
  2143.2     176  2173.2   174.8  3063.2   174.9  3083.2   174.3  3115.2  174.39
  3223.2   174.7  3294.6   173.1  3394.6     174  3434.6   175.4  4124.6   176.6
  4154.6   177.8  4234.6   176.9  4274.6   178.1  4414.6   177.4  4454.6   177.9
  4504.6     177  4514.6   177.5  4574.6   177.7  4716.4   176.6  4846.4   176.7
  4983.7  175.26  4990.9  173.51  4995.8  171.04  5001.6  170.02  5012.1  174.63
  5022.1  175.02  5081.1  175.05  5196.3   175.6  5256.3   177.7  5633.9   181.5
#Mann= 6 ,-1 , 0
  2143.2     .06       0  3115.2     .11       0  4983.7     .08       0
  5022.1     .11       0  5081.1     .06       0  5633.9      .2       0
#XS Ineff= 2 , 0
       0    4450     179               0
Permanent Ineff=
       F       F
Bank Sta=4983.7,5022.1
XS Rating Curve= 0
Exp/Cntr=.5,.3

Type RM Length L Ch R = 1 ,100655.2,39,39,39
BEGIN DESCRIPTION:
Upstream Section of Bridge/Culvert/Weir
END DESCRIPTION:
XS GIS Cut Line= 6
 3011552.771453913944994.3424958     3011659.373   13943893.5478
    3010815.5556   13942730.2754     3010540.305   13942444.8304
    3010366.9991   13942363.2746    3009979.6094   13942342.8857
#Sta/Elev= 30
  2104.5  176.13  2124.5  174.93  3024.5  174.93  3033.1  174.63  3084.5  173.93
  3134.3  174.53  3208.1  174.13  3258.1  173.03  3368.1  173.83  3408.1  174.83
  3598.1  176.33  3688.1  175.53  3718.1  174.53  4398.1  178.23  4458.1  177.13
  4488.1  177.63  4608.1  176.73  4628.1  177.13  4655.5  176.43  4975.5  176.13
    4985  176.43  4995.8  170.62  5001.6   169.6  5012.1  174.21  5018.1  176.16
  5091.6  176.21  5283.6  176.43  5313.6  177.63    5613  180.36  5631.5  180.53
#Mann= 6 ,-1 , 0
  2104.5     .06       0  3033.1     .11       0    4985     .08       0
  5018.1     .11       0  5091.6     .06       0    5613      .2       0
#XS Ineff= 3 ,-1
  2104.5    4400     178    4400    4985  173.61  5018.1  5631.5  176.11
Permanent Ineff=
       F       F       F
Bank Sta=4985,5018.1
XS Rating Curve= 0
Exp/Cntr=.5,.3

Type RM Length L Ch R = 2 ,100635.7,,,
BEGIN DESCRIPTION:
PRIVATE ACCESS US JUERGEN
Structure ID: M100-00-00-20
END DESCRIPTION:
Node Name=Private Access
Bridge Culvert--1,0,-1,-1, 0
Deck Dist Width WeirC Skew NumUp NumDn MinLoCord MaxHiCord MaxSubmerge Is_Ogee
10,19,3,0, 26, 26, , , .95, 0, 1,1,,
    4628    4655  4655.5    4675    4735  4785.5    4895    4925  4975.5    4985
  4990.9    4991  4995.8  4998.4  5001.6  5004.2  5006.5  5012.1  5018.1    5045
  5052.1  5060.4  5091.6  5243.6  5283.6    5295
  176.76  176.42  176.41  176.38   176.7  176.29  176.15   176.7  177.36  177.48
  177.56  177.56  177.74  177.84  177.82  177.81   177.8  177.42  177.02   176.2
  176.21  176.21  176.19  176.11  176.41  176.41
          176.41   176.4  176.37  176.28   176.2  176.14  176.13   176.1   176.4
  173.06  173.01  170.59  170.13  169.57  170.71  171.72  174.18  176.13  176.19
   176.2   176.2  176.18   176.1   176.4
    4628    4655  4655.5    4675    4735  4785.5    4895    4925  4975.5    4985
  4990.9    4991  4995.8  4998.4  5001.6  5004.2  5006.5  5012.1  5018.1    5045
  5052.1  5060.4  5091.6  5243.6  5283.6    5295
 176.758  176.42  176.41  176.38   176.7  176.29  176.15   176.7  177.36  177.48
  177.56  177.56  177.74  177.84  177.82  177.81   177.8  177.42  177.02   176.2
  176.21  176.21  176.19  176.11  176.41  176.41
          176.07  176.06  176.03  175.94  175.86   175.8  175.79  175.76  176.06
  172.72  172.67  170.25  169.79  169.23  170.37  171.38  173.84  175.79  175.85
  175.86  175.86  175.84  175.76  176.06
BR Coef= 1 , 0 , 0 ,1.25, 0 ,,,.8,-1,2,1,
WSPro=,,,, 1 ,,,, 0 ,,,, 0 ,,,,-1 ,-1 ,-1 , 0 , 0 , 0 , 0 , 0
Culvert=1,7.5,,19,.02,.5,1,1,3,169.77,5001.5,169.43,5001.5,Culvert #1  , 0 ,10
Culvert Bottom n=.02
BR U #Sta/Elev= 71
  2104.5   176.1  2108.2  175.88  2124.5   174.9  2984.3   174.9  3004.3   174.9
  3014.3   174.9  3024.5   174.9  3033.1   174.6  3044.3  174.21  3044.5   174.2
  3084.5   173.9  3134.3   174.5  3134.5   174.5  3193.6  174.18  3208.1   174.1
  3258.1     173  3363.6  173.77  3368.1   173.8  3383.6  174.19  3408.1   174.8
  3483.6  175.18  3488.1   175.2  3508.1   175.6  3543.6  175.69  3548.1   175.7
  3563.6  175.89  3598.1   176.3  3638.1   175.7  3673.6  175.56  3688.1   175.5
  3718.1   174.5  4353.6  177.96  4398.1   178.2  4453.6  177.18  4458.1   177.1
  4473.6  177.36  4488.1   177.6  4598.1     177  4608.1   176.7  4628.1   177.1
  4633.6  176.96    4635  176.92    4655  176.41  4655.5   176.4    4675  176.37
    4735  176.28  4785.5   176.2    4895  176.14    4925  176.13  4975.5   176.1
    4985   176.4  4990.9  173.06    4991  173.01  4995.8  170.59  4998.4  170.13
  5001.6  169.57  5004.2  170.71  5006.5  171.72  5012.1  174.18  5018.1  176.13
    5045  176.19  5052.1   176.2  5060.4   176.2  5091.6  176.18  5243.6   176.1
  5283.6   176.4  5303.8  177.21  5313.6   177.6  5393.8  178.33    5613  180.33
  5631.5   180.5
BR U #Mann= 6
  2104.5     .06  3033.1     .11    4985     .08  5018.1     .11  5091.6     .06
    5613      .2
BR U Banks=4985,5018.1
BR D #Sta/Elev= 71
  2104.5   176.1  2108.2  175.54  2124.5  174.56  2984.3  174.56  3004.3  174.56
  3014.3  174.56  3024.5  174.56  3033.1  174.26  3044.3  173.87  3044.5  173.86
  3084.5  173.56  3134.3  174.16  3134.5  174.16  3193.6  173.84  3208.1  173.76
  3258.1  172.66  3363.6  173.43  3368.1  173.46  3383.6  173.85  3408.1  174.46
  3483.6  174.84  3488.1  174.86  3508.1  175.26  3543.6  175.35  3548.1  175.36
  3563.6  175.55  3598.1  175.96  3638.1  175.36  3673.6  175.22  3688.1  175.16
  3718.1  174.16  4353.6  177.62  4398.1  177.86  4453.6  176.84  4458.1  176.76
  4473.6  177.02  4488.1  177.26  4598.1  176.66  4608.1  176.36  4628.1  176.76
  4633.6  176.62    4635  176.58    4655  176.07  4655.5  176.06    4675  176.03
    4735  175.94  4785.5  175.86    4895   175.8    4925  175.79  4975.5  175.76
    4985  176.06  4990.9  172.72    4991  172.67  4995.8  170.25  4998.4  169.79
  5001.6  169.23  5004.2  170.37  5006.5  171.38  5012.1  173.84  5018.1  175.79
    5045  175.85  5052.1  175.86  5060.4  175.86  5091.6  175.84  5243.6  175.76
  5283.6  176.06  5303.8  176.87  5313.6  177.26  5393.8  177.99    5613  179.99
  5631.5  180.16
BR D #Mann= 6
  2104.5     .06  3033.1     .11    4985     .08  5018.1     .11  5091.6     .06
    5613      .2
BR D Banks=4985,5018.1
BC Design=,, 0 ,, 0 ,,,,,,
BC HTab HWMax=180.53

Type RM Length L Ch R = 1 ,100616.2,100,100,100
BEGIN DESCRIPTION:
Downstream Section of Bridge/Culvert/Weir
END DESCRIPTION:
XS GIS Cut Line= 6
 3011585.914001613944994.3761181    3011698.9618   13943903.4313
    3010852.4116   13942713.7081    3010556.7721   13942407.8741
    3010373.2717   13942346.7073    3010016.4654   13942305.9294
#Sta/Elev= 30
  2104.5  176.13  2108.2  175.53  2124.5  174.55  3033.1  174.25  3084.5  173.55
  3134.3  174.15  3208.1  173.75  3258.1  172.65  3368.1  173.45  3408.1  174.45
  3598.1  175.95  3688.1  175.15  3718.1  174.15  4398.1  177.85  4458.1  176.75
  4488.1  177.25  4608.1  176.35  4628.1  176.75  4655.5  176.05  4975.5  175.75
    4985  176.05  4995.8  170.24  5001.6  169.22  5012.1  173.83  5018.1  175.78
  5091.6  175.83  5283.6  176.05  5313.6  177.25    5613  179.98  5631.5  180.15
#Mann= 6 ,-1 , 0
  2104.5     .06       0  3033.1     .11       0    4985     .08       0
  5018.1     .11       0  5091.6     .06       0    5613      .2       0
#XS Ineff= 3 ,-1
  2104.5    4400     178    4400    4985   173.7  5018.1  5631.5  176.11
Permanent Ineff=
       F       F       F
Bank Sta=4985,5018.1
XS Rating Curve= 0
Exp/Cntr=.5,.3

Type RM Length L Ch R = 1 ,100516.2,163.95,178.8,127.42
BEGIN DESCRIPTION:
Cross Section XS49.4
Cross Section 100516.2
END DESCRIPTION:
XS GIS Cut Line= 6
       3011609.9     13945033.37      3011727.81     13943898.93
      3010925.01      13942595.1      3010589.19     13942312.59
      3010365.32     13942264.62      3009984.19     13942252.84
#Sta/Elev= 30
  1973.2   175.6  2923.2   174.2  2952.9  174.41  3083.2   173.8  3113.8   172.9
  3143.8   172.8  3223.8   174.4  3403.8     174  3503.8   174.8  3613.8     173
  3643.8   174.1  4013.8   179.3  4403.8     178  4473.8   177.6  4483.8     177
  4563.8   176.2  4593.8   176.6  4644.9   175.7  4894.9   175.7  4964.9   175.5
    4978  174.88  4985.3  172.09  4991.3  170.33  5000.2  169.14  5005.9  169.71
  5019.2  172.24  5027.8  175.36  5100.3  174.96  5352.7   176.2    5694   180.1
#Mann= 6 ,-1 , 0
  1973.2     .06       0  2952.9     .11       0    4978     .08       0
  5027.8     .11       0  5100.3     .06       0    5694      .2       0
#XS Ineff= 2 , 0
       0    4020     179               0
Permanent Ineff=
       F       F
Bank Sta=4978,5027.8
XS Rating Curve= 0
Exp/Cntr=.3,.1

Type RM Length L Ch R = 1 ,100337.4,243.72,100.7,100.7
BEGIN DESCRIPTION:
Cross Section XS49.3
Cross Section 100337.4
END DESCRIPTION:
XS GIS Cut Line= 5
      3011631.77     13945029.73      3011749.67     13943893.69
      3011031.15     13942541.15      3010809.93     13942214.89
      3009905.29     13942205.51
#Sta/Elev= 30
  1868.2   175.5  2843.7  174.05  2968.2   173.9  3008.2   172.7  3080.3     173
  3140.3   174.3  3410.3   173.7  3480.3   172.7  3850.3   178.3  4150.3   178.3
  4520.3   175.3  4561.9     176  4721.9   174.9  4799.5  173.28  4885.7  173.91
  4961.6  175.44    4978  174.66  4991.3  170.11  5000.2  168.92  5019.2  172.02
  5027.8  175.14  5057.8   175.5    5122  174.69  5173.1   174.4  5175.6  175.05
  5356.1   175.5  5376.1   176.1  5396.1   175.7  5546.1   178.6  5840.8   180.7
#Mann= 5 ,-1 , 0
  1868.2     .06       0  2843.7     .11       0    4978     .08       0
  5027.8     .11       0    5122     .06       0
#XS Ineff= 2 , 0
       0    4000   178.3               0
Permanent Ineff=
       F       F
Bank Sta=4978,5027.8
XS Rating Curve= 0
Exp/Cntr=.5,.3