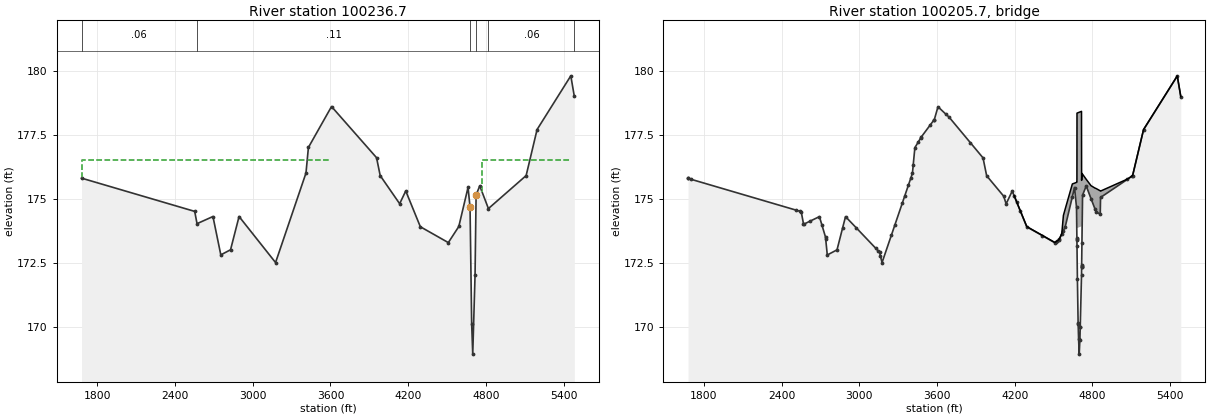
HEC-RAS study M100-00-00.prj: M100-00-00

--- M100-00-00.g01 (geometry) --- (continued)

Type RM Length L Ch R = 1 ,100236.7,62,62,62
BEGIN DESCRIPTION:
Upstream Section of Bridge/Culvert/Weir
END DESCRIPTION:
XS GIS Cut Line= 5
    3011649.9992    13945033.373    3011762.6397   13943894.3331
    3010922.9469   13942140.3684    3010870.2775   13942137.5293
    3009990.4859   13942102.8163
#Sta/Elev= 30
1677.257  175.812551.171  174.51 2569.12  174.032692.125  174.31 2752.83  172.81
2828.005  173.012893.783  174.313175.691  172.513410.614  176.013429.408  177.01
 3607.95  178.613955.636  176.613983.827  175.914134.178  174.814181.162  175.31
4293.925  173.914510.055  173.294591.057  173.924662.379  175.45 4677.79  174.67
4690.288  170.124698.651  168.934716.505  172.034724.586  175.154752.777  175.51
4819.684  174.625110.988  175.915195.561  177.715456.043  179.815483.106  179.01
#Mann= 6 ,-1 , 0
1677.257     .06       0 2569.12     .11       0 4677.79     .07       0
4724.586     .11       04819.684     .06       05483.106      .2       0
#XS Ineff= 4 ,-1
 1677.26    3600   176.5    3600 4668.39  173.85 4733.98    4770  175.06
    4770 5456.04   176.5
Permanent Ineff=
       F       F       F       F
Bank Sta=4677.79,4724.586
XS Rating Curve= 0
Skew Angle= 20
Exp/Cntr=.5,.3

Type RM Length L Ch R = 3 ,100205.7,,,
BEGIN DESCRIPTION:
JUERGEN
Structure ID: M100-00-00-19
END DESCRIPTION:
Node Name=Juergen
Bridge Culvert--1,0,-1,-1, 0
Deck Dist Width WeirC Skew NumUp NumDn MinLoCord MaxHiCord MaxSubmerge Is_Ogee
10,42,2.6,20, 39, 39, , , .95, 0, 1,1,,
 4196.86 4215.65 4243.84 4293.93 4412.99 4510.06 4516.35 4525.75 4543.04 4544.54
  4563.9 4576.68 4591.06 4645.75 4662.38 4677.79  4680.7 4680.81 4680.89 4681.46
 4716.51 4717.26 4717.34 4717.45 4717.54  4719.7 4724.59 4752.78 4790.08 4819.68
 4829.17 4861.12 4863.47 5071.33 5108.92 5110.99 5195.56 5456.04 5483.11
  175.12  174.88  174.53  173.91  173.57  173.29  173.31  173.34   173.4  173.42
  173.63  174.35  174.61  175.58  175.61  175.64  175.65  175.65  175.65  178.35
  178.42  175.72  175.72  175.72  175.73  175.99  175.96  175.76  175.51  175.42
   175.4  175.31   175.3  175.77   175.9  175.91  177.71  179.81     179
  175.11  174.87  174.52   173.9  173.56  173.28   173.3  173.33  173.39  173.41
  173.62  173.75  173.91  175.08  175.44  174.66  173.48  173.43  173.85  173.85
  173.92  173.92  173.92  172.38  172.42  173.25  175.14   175.5     175  174.61
  174.48   174.4  175.05  175.76  175.89   175.9   177.7   179.8     179
 4196.86 4215.65 4243.84 4293.93 4412.99 4510.06 4516.35 4525.75 4543.04 4544.54
  4563.9 4576.68 4591.06 4645.75 4662.38 4677.79  4680.7 4680.81 4680.89 4681.46
 4716.51 4717.26 4717.34 4717.45 4717.54  4719.7 4724.59 4752.78 4790.08 4819.68
 4829.17 4861.12 4863.47 5071.33 5108.92 5110.99 5195.56 5456.04 5483.11
  175.11  174.88  174.53  173.91  173.57  173.29  173.31  173.34   173.4  173.42
  173.63  174.35  174.61  175.58  175.61  175.64  175.65  175.65  175.65  178.35
  178.42  175.72  175.72  175.72  175.73  175.99  175.96  175.76  175.51  175.42
   175.4  175.31   175.3  175.77   175.9  175.91  177.71  179.81     179
  175.11  174.87  174.52   173.9  173.56  173.28   173.3  173.33  173.39  173.41
  173.62  173.75  173.91  175.08  175.44  174.66  173.48  173.43  173.85  173.85
  173.92  173.92  173.92  172.38  172.42  173.25  175.14   175.5     175  174.61
  174.48   174.4  175.05  175.76  175.89   175.9   177.7   179.8     179
Pier Skew= 20
Abutment Skew #Up #Dn= , 2 , 2
4680.7034690.288
  173.85   170.1
4680.7034690.288
  173.85   170.1
Abutment Skew #Up #Dn= , 2 , 2
4706.6394717.529
  169.99  173.92
4706.6394717.529
  169.99  173.92
BR Coef= 1 , 1 , 0 ,1.25, 0 ,,,.8,0,2,0,
WSPro=,,,, 1 ,,,, 0 ,,,, 0 ,,,,-1 ,-1 ,-1 , 0 , 0 , 0 , 0 , 0
BR U #Sta/Elev= 94
 1677.26   175.8 1678.39   175.8 1701.69  175.76 2514.71  174.55  2542.9  174.51
 2551.17   174.5 2569.12  174.02 2569.97     174 2618.08  174.12 2692.13   174.3
 2712.14  173.96 2739.11   173.5 2740.33  173.44 2752.83   172.8 2828.01     173
 2871.89  173.87 2893.78   174.3 2975.26  173.87 3125.61  173.07  3144.4  172.97
  3156.9   172.9 3163.19  172.77 3175.69   172.5 3247.77  173.57 3275.96  173.99
 3332.34  174.83 3351.13  175.11 3379.32  175.53 3398.12  175.81 3410.61     176
 3416.91  176.34 3429.41     177  3454.5  177.21 3473.29  177.37 3476.39   177.4
 3548.47  177.89 3576.66  178.08 3579.76   178.1 3607.95   178.6 3670.63   178.3
 3692.52   178.2 3858.57  177.19 3955.64   176.6 3983.83   175.9 4115.38   175.1
 4134.18   174.8 4181.16   175.3 4196.86  175.11 4215.65  174.87 4243.84  174.52
 4293.93   173.9 4412.99  173.56 4510.06  173.28 4516.35   173.3 4525.75  173.33
 4543.04  173.39 4544.54  173.41  4563.9  173.62 4576.68  173.75 4591.06  173.91
 4645.75  175.08 4662.38  175.44 4677.79  174.66  4680.7  173.48 4680.81  173.43
 4680.89   173.4 4681.46  173.17 4684.65  171.87 4690.19  170.14 4690.29  170.11
 4693.95  169.51 4698.65  168.92 4704.01  169.49 4706.54  169.97 4706.64  169.99
 4716.51  172.02 4717.26  172.31 4717.34  172.34 4717.45  172.38 4717.54  172.42
  4719.7  173.25 4724.59  175.14 4752.78   175.5 4790.08     175 4819.68  174.61
 4829.17  174.48 4861.12   174.4 4863.47  175.05 5071.33  175.76 5108.92  175.89
 5110.99   175.9 5195.56   177.7 5456.04   179.8 5483.11     179
BR U #Mann= 5
 1677.26     .06 2569.12     .11 4677.79     .06 4724.59     .11 4819.68     .06
BR U Banks=4677.79,4724.59
BR D #Sta/Elev= 94
 1677.26   175.8 1678.39   175.8 1701.69  175.76 2514.71  174.55  2542.9  174.51
 2551.17   174.5 2569.12  174.02 2569.97     174 2618.08  174.12 2692.13   174.3
 2712.14  173.96 2739.11   173.5 2740.33  173.44 2752.83   172.8 2828.01     173
 2871.89  173.87 2893.78   174.3 2975.26  173.87 3125.61  173.07  3144.4  172.97
  3156.9   172.9 3163.19  172.77 3175.69   172.5 3247.77  173.57 3275.96  173.99
 3332.34  174.83 3351.13  175.11 3379.32  175.53 3398.12  175.81 3410.61     176
 3416.91  176.34 3429.41     177  3454.5  177.21 3473.29  177.37 3476.39   177.4
 3548.47  177.89 3576.66  178.08 3579.76   178.1 3607.95   178.6 3670.63   178.3
 3692.52   178.2 3858.57  177.19 3955.64   176.6 3983.83   175.9 4115.38   175.1
 4134.18   174.8 4181.16   175.3 4196.86  175.11 4215.65  174.87 4243.84  174.52
 4293.93   173.9 4412.99  173.56 4510.06  173.28 4516.35   173.3 4525.75  173.33
 4543.04  173.39 4544.54  173.41  4563.9  173.62 4576.68  173.75 4591.06  173.91
 4645.75  175.08 4662.38  175.44 4677.79  174.66  4680.7  173.48 4680.81  173.43
 4680.89   173.4 4681.46  173.17 4684.65  171.87 4690.19  170.14 4690.29  170.11
 4693.95  169.51 4698.65  168.92 4704.01  169.49 4706.54  169.97 4706.64  169.99
 4716.51  172.02 4717.26  172.31 4717.34  172.34 4717.45  172.38 4717.54  172.42
  4719.7  173.25 4724.59  175.14 4752.78   175.5 4790.08     175 4819.68  174.61
 4829.17  174.48 4861.12   174.4 4863.47  175.05 5071.33  175.76 5108.92  175.89
 5110.99   175.9 5195.56   177.7 5456.04   179.8 5483.11     179
BR D #Mann= 5
 1677.26     .06 2569.12     .11 4677.79     .06 4724.59     .11 4819.68     .06
BR D Banks=4677.79,4724.59
BC Design=,, 0 ,, 0 ,,,,,,
BC HTab HWMax=179.81