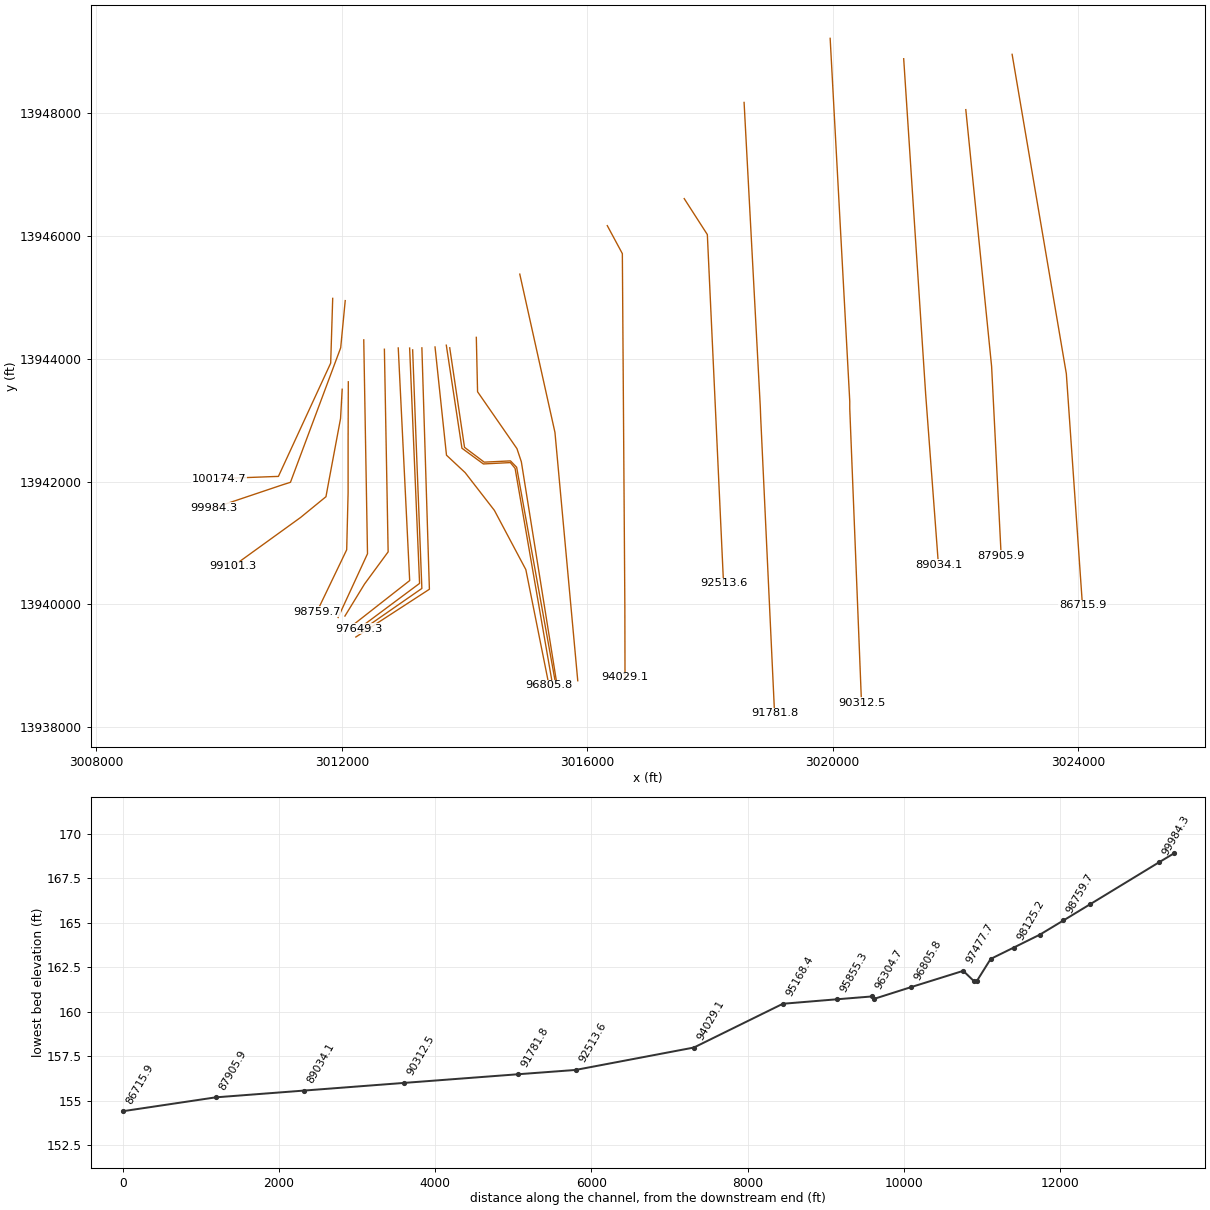
HEC-RAS study M100-00-00.prj: M100-00-00

--- M100-00-00.g01 (geometry) --- (continued)

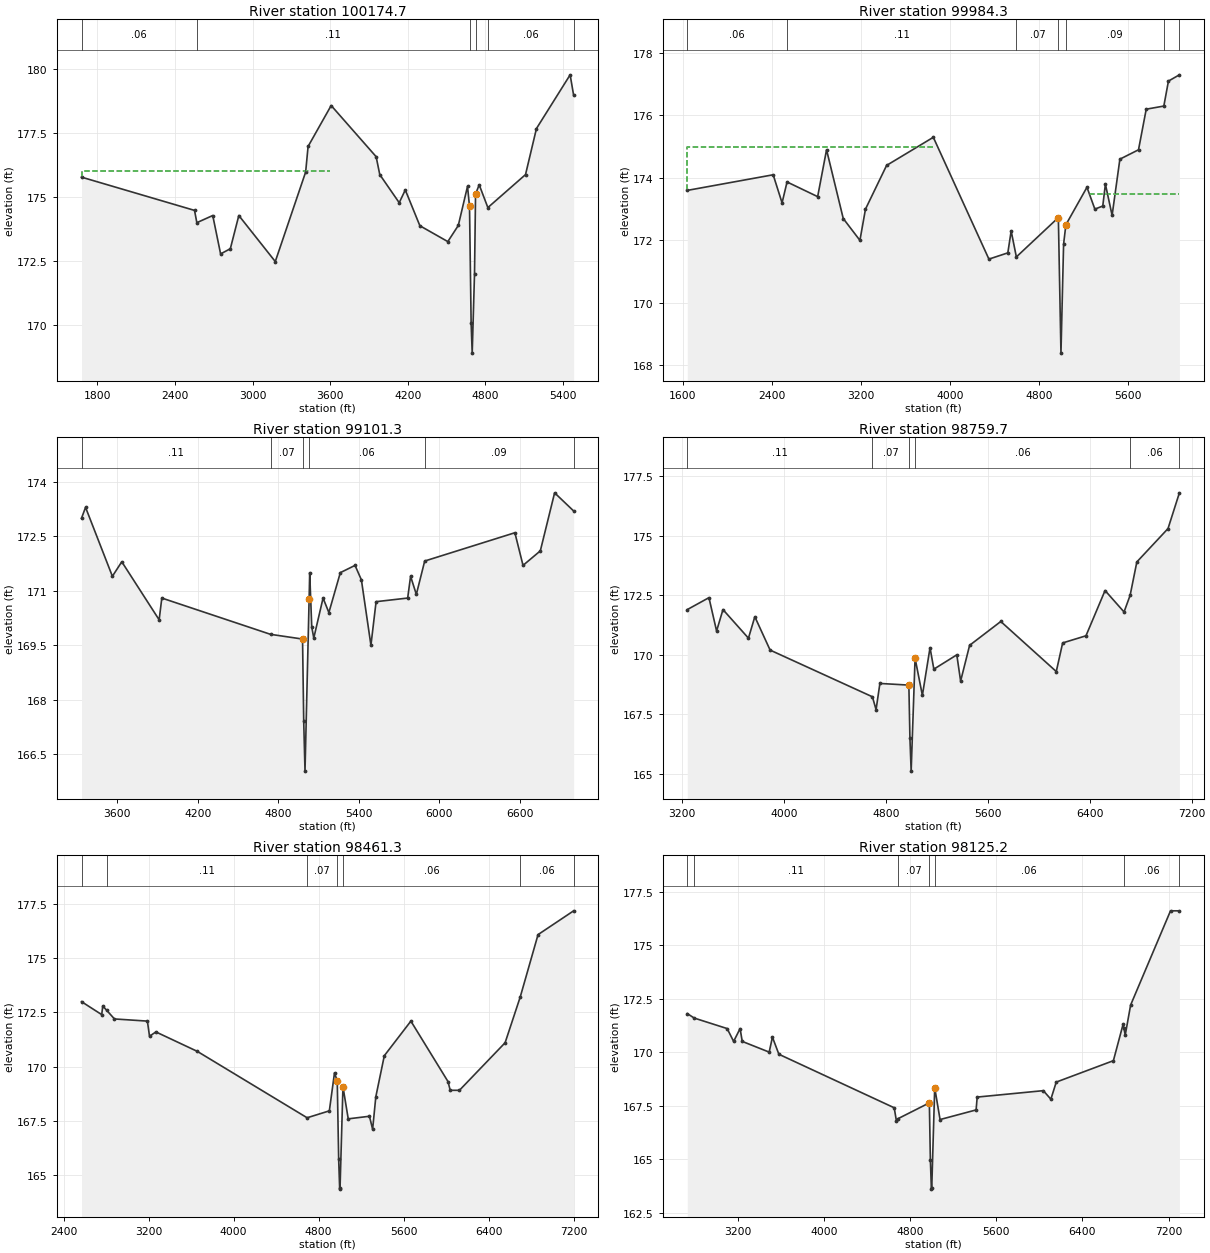
Type RM Length L Ch R = 1 ,100174.7,63,190.4,221
BEGIN DESCRIPTION:
Downstream Section of Bridge/Culvert/Weir
END DESCRIPTION:
XS GIS Cut Line= 5
    3011850.4871   13944985.9849    3011817.6807   13943930.5491
     3010965.358   13942083.6876    3010895.2523   13942081.6317
    3009994.2408   13942047.9865
#Sta/Elev= 30
1677.257  175.772551.171  174.47 2569.12  173.992692.125  174.27 2752.83  172.77
2828.005  172.972893.783  174.273175.691  172.473410.614  175.973429.408  176.97
 3607.95  178.573955.636  176.573983.827  175.874134.178  174.774181.162  175.27
4293.925  173.874510.055  173.254591.057  173.884662.379  175.41 4677.79  174.63
4690.288  170.084698.651  168.894716.505  171.994724.586  175.114752.777  175.47
4819.684  174.585110.988  175.875195.561  177.675456.043  179.775483.106  178.97
#Mann= 6 ,-1 , 0
1677.257     .06       0 2569.12     .11       0 4677.79     .07       0
4724.586     .11       04819.684     .06       05483.106      .2       0
#XS Ineff= 3 ,-1
 1677.26    3600     176    3600 4671.52   173.3 4730.85 5483.11  175.06
Permanent Ineff=
       F       F       F
Bank Sta=4677.79,4724.586
XS Rating Curve= 0
Skew Angle= 20
Exp/Cntr=.5,.3

Type RM Length L Ch R = 1 ,99984.3 ,617.49,883,867.71
BEGIN DESCRIPTION:
Cross Section XS49.2
Cross Section 99984.3
END DESCRIPTION:
XS GIS Cut Line= 5
      3012054.62     13944949.53      3011980.76     13944180.75
      3011161.89     13941987.99      3011026.28     13941944.79
      3009917.57     13941571.67
#Sta/Elev= 30
  1638.4   173.6  2410.7   174.1  2490.7   173.2  2535.5  173.87  2810.7   173.4
  2890.7   174.9  3040.7   172.7  3190.7     172  3240.7     173  3430.7   174.4
  3850.7   175.3  4350.7   171.4  4520.7   171.6  4550.7   172.3  4597.5  171.47
 4975.06  172.73  4998.5  168.39 5022.18  171.88  5042.8   172.5  5232.3   173.7
  5303.4     173  5374.4   173.1  5398.1   173.8  5458.4   172.8  5528.3   174.6
  5695.8   174.9  5765.2   176.2  5923.5   176.3  5964.9   177.1  6063.5   177.3
#Mann= 7 ,-1 , 0
  1638.4     .06       0  2535.5     .11       0  4597.5     .07       0
 4975.06     .07       0  5042.8     .09       0  5923.5     .06       0
  6063.5      .2       0
#XS Ineff= 2 , 0
       0    3850     175    5255       0   173.5
Permanent Ineff=
       F       F
Bank Sta=4975.06,5042.8
XS Rating Curve= 0
Exp/Cntr=.3,.1

Type RM Length L Ch R = 1 ,99101.3 ,299.13,341.6,436.42
BEGIN DESCRIPTION:
Cross Section XS49.1
Cross Section 99101.3
END DESCRIPTION:
XS GIS Cut Line= 6
      3012005.28     13943504.92      3011978.38      13943027.3
      3011788.99     13942014.96      3011740.55      13941752.9
      3011327.06     13941414.62      3010226.06     13940619.45
#Sta/Elev= 30
  3333.2     173  3363.2   173.3  3563.2   171.4  3633.2   171.8  3911.6   170.2
  3931.6   170.8  4741.6   169.8 4980.15  169.67  4988.9  167.41  4998.5  166.03
  5029.2  170.77  5033.5   171.5  5048.8     170    5064   169.7  5133.1   170.8
  5176.4   170.4  5261.7   171.5  5371.4   171.7  5418.8   171.3  5489.8   169.5
  5528.2   170.7  5763.6   170.8  5785.3   171.4  5828.1   170.9  5890.4  171.82
  6562.4   172.6  6623.1   171.7    6752   172.1  6858.5   173.7  7000.3   173.2
#Mann= 6 ,-1 , 0
  3333.2     .11       0  4741.6     .07       0 4980.15     .07       0
  5029.2     .06       0  5890.4     .09       0  7000.3      .2       0
Bank Sta=4980.15,5029.2
XS Rating Curve= 0
Exp/Cntr=.3,.1

Type RM Length L Ch R = 1 ,98759.7 ,294.17,298.4,304.15
BEGIN DESCRIPTION:
Cross Section XS49.05
END DESCRIPTION:
XS GIS Cut Line= 6
      3012104.99     13943625.99      3012101.61     13942664.51
      3012101.53     13941911.97      3012101.53     13941814.98
      3012078.59     13940887.64      3011592.45     13939875.19
#Sta/Elev= 30
  3241.7   171.9  3411.7   172.4  3471.7     171  3521.7   171.9  3721.7   170.7
  3771.7   171.6  3891.7   170.2  4694.4  168.24  4723.2   167.7  4753.2   168.8
 4980.52  168.73  4988.9   166.5  4998.5  165.12  5029.2  169.86  5086.6   168.3
  5146.6   170.3  5176.6   169.4  5356.7     170  5386.7   168.9  5457.2   170.4
  5701.8   171.4  6137.3   169.3  6187.3   170.5  6370.3   170.8  6520.1   172.7
  6669.1   171.8  6716.9   172.5  6769.6   173.9  7014.2   175.3  7103.5   176.8
#Mann= 6 ,-1 , 0
  3241.7     .11       0  4694.4     .07       0 4980.52     .07       0
  5029.2     .06       0  6716.9     .06       0  7103.5      .2       0
Bank Sta=4980.52,5029.2
XS Rating Curve= 0
Exp/Cntr=.3,.1

Type RM Length L Ch R = 1 ,98461.3 ,335.64,336.1,347.34
BEGIN DESCRIPTION:
Cross Section 98461.3
Cross Section XS49
Cross Section M100-00-00-X49
Located At: US CYPRESS-ROSE HILL
END DESCRIPTION:
XS GIS Cut Line= 3
       3012356.7      13944309.8      3012417.86      13940823.3
      3011938.72      13939783.5
#Sta/Elev= 30
  2568.5     173  2758.5   172.4  2768.5   172.8  2805.2   172.6  2878.5   172.2
  3188.5   172.1  3208.5   171.4  3268.5   171.6  3658.5   170.7  4691.8  167.63
  4901.1  167.95  4949.7  169.71  4975.5  169.33  4988.9  165.71  4998.5  164.33
  5001.8  164.38  5029.2  169.07  5078.9  167.58  5278.5   167.7  5308.5   167.1
  5338.5   168.6  5418.5   170.5  5668.5   172.1  6018.5   169.3  6038.5   168.9
  6125.5   168.9  6555.5   171.1  6698.1  173.22  6865.5   176.1  7200.5   177.2
#Mann= 7 ,-1 , 0
  2568.5     .05       0  2805.2     .11       0  4691.8     .07       0
  4975.5     .07       0  5029.2     .06       0  6698.1     .06       0
  7200.5      .2       0
Bank Sta=4975.5,5029.2
XS Rating Curve= 0
Exp/Cntr=.3,.1

Type RM Length L Ch R = 1 ,98125.2 ,288.06,296.3,312.49
BEGIN DESCRIPTION:
Cross Section 98125.2
Cross Section XS48.7
END DESCRIPTION:
XS GIS Cut Line= 4
      3012693.11      13944156.9      3012754.28      13940853.9
      3012369.53      13940329.6      3012049.71      13939807.3
#Sta/Elev= 30
  2733.4   171.8  2798.1  171.59  3103.4   171.1  3163.4   170.5  3223.4   171.1
  3243.4   170.5  3493.4     170  3523.4   170.7  3583.4   169.9  4653.4   167.4
  4673.4   166.8  4688.3  166.89 4979.51  167.63  4988.9  164.98  4998.5   163.6
  5001.8  163.65  5029.2  168.34  5078.9  166.85  5413.4   167.3  5423.4   167.9
    6037   168.2    6107   167.8    6157   168.6  6687.2   169.6  6777.2   171.3
  6784.5  171.12  6797.2   170.8  6847.2   172.2  7217.2   176.6  7299.7   176.6
#Mann= 7 ,-1 , 0
  2733.4      .2       0  2798.1     .11       0  4688.3     .07       0
 4979.51     .07       0  5029.2     .06       0  6784.5     .06       0
  7299.7      .2       0
Bank Sta=4979.51,5029.2
XS Rating Curve= 0
Exp/Cntr=.3,.1

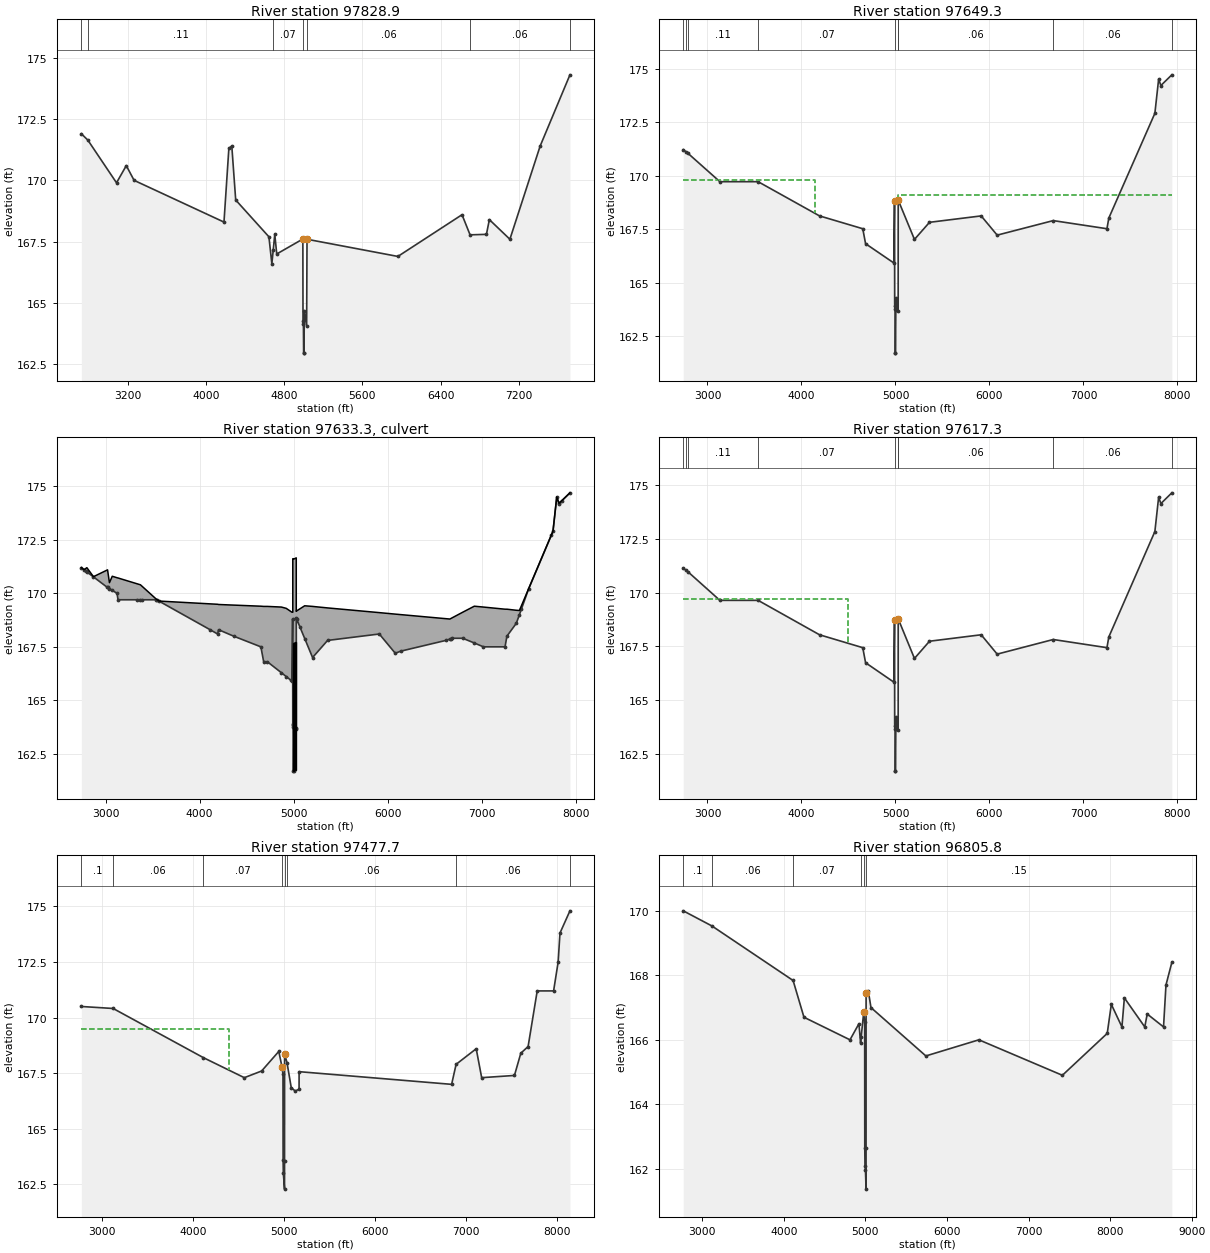
Type RM Length L Ch R = 1 ,97828.9 ,179.6,179.6,179.6
BEGIN DESCRIPTION:
Cross Section 97828.9
Cross Section XS48.6
END DESCRIPTION:
XS GIS Cut Line= 3
      3012919.05      13944177.8      3013105.32      13940385.9
       3012157.1      13939642.6
#Sta/Elev= 30
  2722.8   171.9  2789.2  171.64  3082.8   169.9  3182.8   170.6  3262.8     170
  4182.8   168.3  4232.8   171.3  4262.8   171.4  4302.8   169.2  4642.8   167.7
  4672.8   166.6  4687.4  167.18  4702.8   167.8  4722.8     167 4990.24  167.61
  4991.8  164.28  4995.9  164.15  4998.2  162.96  5000.3  162.96  5006.7  164.68
  5028.9  164.08  5032.8   167.6  5962.8   166.9  6619.3   168.6  6701.8  167.78
  6869.3   167.8  6899.3   168.4  7109.3   167.6  7419.3   171.4  7724.1   174.3
#Mann= 7 ,-1 , 0
  2722.8      .2       0  2789.2     .11       0  4687.4     .07       0
 4990.24     .07       0  5032.8     .06       0  6701.8     .06       0
  7724.1      .2       0
#XS Ineff= 2 , 0
       0    4235     171               0
Permanent Ineff=
       F       F
Bank Sta=4990.24,5032.8
XS Rating Curve= 0
Exp/Cntr=.5,.3

Type RM Length L Ch R = 1 ,97649.3 ,32,32,32
BEGIN DESCRIPTION:
Upstream Section of Bridge/Culvert/Weir
END DESCRIPTION:
XS GIS Cut Line= 3
     3013104.641       13944176.      3013266.57      13940339.7
      3012275.49       13939602.
#Sta/Elev= 30
  2742.2  171.22  2771.1  171.12  2789.5  171.06  3132.2  169.72  3539.2  169.72
  4192.2  168.12  4652.2  167.52  4682.2  166.82  4982.2  165.92  4990.1  168.82
  4991.8  163.89  4995.9  163.76  4998.2   161.7  5000.3   161.7    5004  163.72
  5006.7  164.29  5028.9  163.69  5029.3  168.86  5032.2  168.83  5202.2  167.02
  5362.2  167.82  5912.2  168.12  6082.2  167.22  6678.8   167.9  7250.2  167.52
  7270.2  168.02  7760.2  172.92  7800.2  174.52  7823.9  174.22  7940.6  174.72
#Mann= 9 ,-1 , 0
  2742.2      .2       0  2771.1      .1       0  2789.5     .11       0
  3539.2     .07       0  4990.1     .06       0  5029.3     .07       0
  5032.2     .06       0  6678.8     .06       0  7940.6      .2       0
#XS Ineff= 2 , 0
       0    4140   169.8  5029.3       0  169.12
Permanent Ineff=
       F       F
Bank Sta=4990.1,5029.3
XS Rating Curve= 0
Exp/Cntr=.5,.3

Type RM Length L Ch R = 2 ,97633.3 ,,,
BEGIN DESCRIPTION:
CYPRESS-ROSE HILL
Structure ID: M100-00-00-18
END DESCRIPTION:
Node Name=Cypress-Rose Hil
Bridge Culvert--1,0,-1,-1, 0
Deck Dist Width WeirC Skew NumUp NumDn MinLoCord MaxHiCord MaxSubmerge Is_Ogee
10,12,3,0, 49, 49, , , .95, 0, 1,1,,
  2742.2  2771.1  2801.1  2871.1  3021.1  3041.1  3071.1  3122.2  3132.2  3371.1
  3542.2  3571.1  4192.2  4202.2  4652.2  4682.2  4722.2  4870.6  4921.9  4982.2
  4990.1  4991.8  4991.9  4995.9  4998.2  5000.3    5004  5006.7  5028.8  5028.9
  5029.3  5118.5  5202.2  5362.2  5912.2  6082.2    6663  6800.2    6923  7020.2
  7250.2  7270.2  7370.2    7403  7500.2  7760.2  7800.2  7823.9  7940.6
   171.2  171.11   171.2  170.78   171.1   170.5   170.8  170.73  170.72   170.4
  169.72  169.64  169.49  169.48   169.4  169.39  169.39  169.36   169.3  169.12
  169.12  169.12  171.62  171.62  171.62  171.62  171.61  171.61  171.66  169.16
  169.17  169.42  169.39  169.32   169.1  169.03   168.8  169.12   169.4  169.36
  169.26  169.26  169.21   169.2  170.21  172.91  174.51  174.21   174.7
   171.2   171.1     171  170.77  170.28  170.22  170.14     170   169.7   169.7
   169.7  169.63   168.1   168.3   167.5   166.8   166.8  166.29  166.11   165.9
   168.8  163.87  163.85  163.74  162.55  162.55   163.7  164.27  163.67  163.67
  168.84  167.89     167   167.8   168.1   167.2  167.86   167.9  167.68   167.5
   167.5     168   168.6     169   170.2   172.9   174.5   174.2   174.7
  2742.2  2771.1  2801.1  2871.1  3021.1  3041.1  3071.1  3122.2  3132.2  3371.1
  3542.2  3571.1  4192.2  4202.2  4652.2  4682.2  4722.2  4870.6  4921.9  4982.2
  4990.1  4991.8  4991.9  4995.9  4998.2  5000.3    5004  5006.7  5028.8  5028.9
  5029.3  5118.5  5202.2  5362.2  5912.2  6082.2    6663  6800.2    6923  7020.2
  7250.2  7270.2  7370.2    7403  7500.2  7760.2  7800.2  7823.9  7940.6
   171.2  171.11   171.2  170.78   171.1   170.5   170.8  170.73  170.72   170.4
  169.72  169.64  169.49  169.48   169.4  169.39  169.39  169.36   169.3  169.12
  169.12  169.12  171.62  171.62  171.62  171.62  171.61  171.61  171.66  169.16
  169.17  169.42  169.39  169.32   169.1  169.03   168.8  169.12   169.4  169.36
  169.26  169.26  169.21   169.2  170.21  172.91  174.51  174.21   174.7
  171.15  171.05  170.95  170.72  170.23  170.17  170.09  169.95  169.65  169.65
  169.65  169.58  168.05  168.25  167.45  166.75  166.75  166.24  166.06  165.85
  168.75  163.82   163.8  163.69   162.5   162.5  163.65  164.22  163.62  163.62
  168.79  167.84  166.95  167.75  168.05  167.15  167.81  167.85  167.63  167.45
  167.45  167.95  168.55  168.95  170.15  172.85  174.45  174.15  174.65
BR Coef= 1 , 0 , 0 ,1.25, 0 ,,,.8,-1,2,1,
WSPro=,,,, 1 ,,,, 0 ,,,, 0 ,,,,-1 ,-1 ,-1 , 0 , 0 , 0 , 0 , 0
Culvert=2,6,8,12,.02,.4,1,8,1,161.69,4996.2,161.7,4996.2,Culvert #1  , 0 ,10
Culvert Bottom n=.02
Culvert=2,6,8,12,.02,.4,1,8,1,161.72,5005.4,161.72,5005.4,Culvert #2  , 0 ,10
Culvert Bottom n=.02
Culvert=2,6,8,12,.02,.4,1,8,1,161.72,5014.4,161.7,5014.4,Culvert #3  , 0 ,10
Culvert Bottom n=.02
Culvert=2,6,8,12,.02,.4,1,8,1,161.74,5023.5,161.71,5023.5,Culvert #4  , 0 ,10
Culvert Bottom n=.02
BR U #Sta/Elev= 68
  2742.2   171.2  2771.1   171.1  2789.5  171.04  2801.1     171  2871.1  170.77
  3012.2   170.3  3021.1  170.28  3041.1  170.22  3071.1  170.14  3122.2     170
  3132.2   169.7  3332.2   169.7  3371.1   169.7  3382.2   169.7  3539.2   169.7
  3542.2   169.7  3571.1  169.63  4112.2   168.3  4192.2   168.1  4202.2   168.3
  4362.2     168  4652.2   167.5  4682.2   166.8  4722.2   166.8  4870.6  166.29
  4921.9  166.11  4970.9  165.94  4982.2   165.9  4990.1   168.8  4991.8  163.87
  4992.3  163.85  4995.9  163.74  4998.2   161.7  5000.3   161.7    5004   163.7
  5006.7  164.27  5009.7  164.19  5027.6  163.71  5028.9  163.67  5029.3  168.84
  5032.2  168.81  5067.4  168.43  5118.5  167.89  5202.2     167  5362.2   167.8
  5912.2   168.1  6082.2   167.2  6142.2   167.3  6620.2   167.8    6663  167.86
  6678.8  167.88  6690.2   167.9  6800.2   167.9    6923  167.68  7020.2   167.5
  7250.2   167.5  7270.2     168  7370.2   168.6    7403     169    7423  169.25
  7500.2   170.2    7743  172.72  7760.2   172.9  7800.2   174.5    7823  174.21
  7823.9   174.2    7853  174.32  7940.6   174.7
BR U #Mann= 8
  2742.2      .2  2771.1      .1  2789.5     .11  3539.2     .07  4990.1     .06
  5029.3     .07  5032.2     .06  6678.8     .06
BR U Banks=4990.1,5029.3
BR D #Sta/Elev= 68
  2742.2  171.15  2771.1  171.05  2789.5  170.99  2801.1  170.95  2871.1  170.72
  3012.2  170.25  3021.1  170.23  3041.1  170.17  3071.1  170.09  3122.2  169.95
  3132.2  169.65  3332.2  169.65  3371.1  169.65  3382.2  169.65  3539.2  169.65
  3542.2  169.65  3571.1  169.58  4112.2  168.25  4192.2  168.05  4202.2  168.25
  4362.2  167.95  4652.2  167.45  4682.2  166.75  4722.2  166.75  4870.6  166.24
  4921.9  166.06  4970.9  165.89  4982.2  165.85  4990.1  168.75  4991.8  163.82
  4992.3   163.8  4995.9  163.69  4998.2   161.7  5000.3   161.7    5004  163.65
  5006.7  164.22  5009.7  164.14  5027.6  163.66  5028.9  163.62  5029.3  168.79
  5032.2  168.76  5067.4  168.38  5118.5  167.84  5202.2  166.95  5362.2  167.75
  5912.2  168.05  6082.2  167.15  6142.2  167.25  6620.2  167.75    6663  167.81
  6678.8  167.83  6690.2  167.85  6800.2  167.85    6923  167.63  7020.2  167.45
  7250.2  167.45  7270.2  167.95  7370.2  168.55    7403  168.95    7423   169.2
  7500.2  170.15    7743  172.67  7760.2  172.85  7800.2  174.45    7823  174.16
  7823.9  174.15    7853  174.27  7940.6  174.65
BR D #Mann= 8
  2742.2      .2  2771.1      .1  2789.5     .11  3539.2     .07  4990.1     .06
  5029.3     .07  5032.2     .06  6678.8     .06
BR D Banks=4990.1,5029.3
BC Design=,, 0 ,, 0 ,,,,,,
BC HTab HWMax=174.72

Type RM Length L Ch R = 1 ,97617.3 ,139.6,139.6,139.6
BEGIN DESCRIPTION:
Downstream Section of Bridge/Culvert/Weir
END DESCRIPTION:
XS GIS Cut Line= 5
       3013153.8      13944146.6       3013216.8      13942483.3
      3013262.36      13941321.6      3013304.01      13940257.4
      3012254.65      13939528.6
#Sta/Elev= 30
  2742.2  171.14  2771.1  171.04  2789.5  170.98  3132.2  169.64  3539.2  169.64
  4192.2  168.04  4652.2  167.44  4682.2  166.74  4982.2  165.84  4990.1  168.74
  4991.8  163.81  4995.9  163.68  4998.2   161.7  5000.3   161.7    5004  163.64
  5006.7  164.21  5028.9  163.61  5029.3  168.78  5032.2  168.75  5202.2  166.94
  5362.2  167.74  5912.2  168.04  6082.2  167.14  6678.8  167.82  7250.2  167.44
  7270.2  167.94  7760.2  172.84  7800.2  174.44  7823.9  174.14  7940.6  174.64
#Mann= 9 ,-1 , 0
  2742.2      .2       0  2771.1      .1       0  2789.5     .11       0
  3539.2     .07       0  4990.1     .06       0  5029.3     .07       0
  5032.2     .06       0  6678.8     .06       0  7940.6      .2       0
#XS Ineff= 2 , 0
       0    4500   169.7  5029.3       0   167.5
Permanent Ineff=
       F       F
Bank Sta=4990.1,5029.3
XS Rating Curve= 0
Exp/Cntr=.5,.3

Type RM Length L Ch R = 1 ,97477.7 ,446.49,671.9,905.83
BEGIN DESCRIPTION:
Cross Section 97477.7
Cross Section XS48.5
END DESCRIPTION:
XS GIS Cut Line= 3
      3013304.26      13944179.2       3013426.8      13940244.3
      3012227.85      13939465.8
#Sta/Elev= 30
  2776.2   170.5  3125.7  170.41  4116.7   168.2  4566.2   167.3  4756.2   167.6
  4944.7  168.48  4979.8  167.79  4990.8  167.46  4992.1  163.58  4994.7  163.01
  5007.8  162.29  5007.9  163.57  5008.4  168.36  5035.3  167.97  5081.6  166.85
    5125   166.7  5167.5  166.78  5167.8  167.57    6843     167  6892.2   167.9
    7113   168.6    7173   167.3    7533   167.4    7603   168.4    7683   168.7
    7783   171.2    7963   171.2    8013   172.5    8033   173.8  8142.5   174.8
#Mann= 8 ,-1 , 0
  2776.2      .1       0  3125.7     .06       0  4116.7     .07       0
  4979.8     .06       0  5008.4     .07       0  5035.3     .06       0
  6892.2     .06       0  8142.5      .2       0
#XS Ineff= 2 , 0
       0    4400   169.5               0
Permanent Ineff=
       F       F
Bank Sta=4979.8,5008.4
XS Rating Curve= 0
Exp/Cntr=.3,.1

Type RM Length L Ch R = 1 ,96805.8 ,277.5,466.1,706.3
BEGIN DESCRIPTION:
Cross Section 96805.8
Cross Section XS48.3
Extended to Drainage Area Divide Right
END DESCRIPTION:
XS GIS Cut Line= 6
      3013518.65     13944193.64      3013705.39      13942429.5
      3014009.16     13942145.98      3014486.51     13941529.77
      3014999.21     13940564.04    3015376.1023   13938679.5872
#Sta/Elev= 30
  2766.7     170  3118.9  169.53  4113.4  167.84  4246.7   166.7  4810.7     166
  4920.7   166.5  4940.7   165.9  4947.9  166.09  4979.8  166.87  4990.8  166.54
  4992.1  162.66  4994.7  162.09  5000.2  161.97  5007.8  161.37  5007.9  162.65
  5008.4  167.44  5036.2   167.5    5068     167  5741.1   165.5  6391.1     166
  7414.4   164.9  7964.4   166.2  8014.4   167.1  8144.4   166.4  8174.4   167.3
  8424.4   166.4  8454.4   166.8  8654.4   166.4  8684.4   167.7  8756.2   168.4
#Mann= 6 ,-1 , 0
  2766.7      .1       0  3118.9     .06       0  4113.4     .07       0
  4947.9     .15       0  4979.8     .06       0  5008.4     .15       0
Bank Sta=4979.8,5008.4
XS Rating Curve= 0
Exp/Cntr=.5,.3

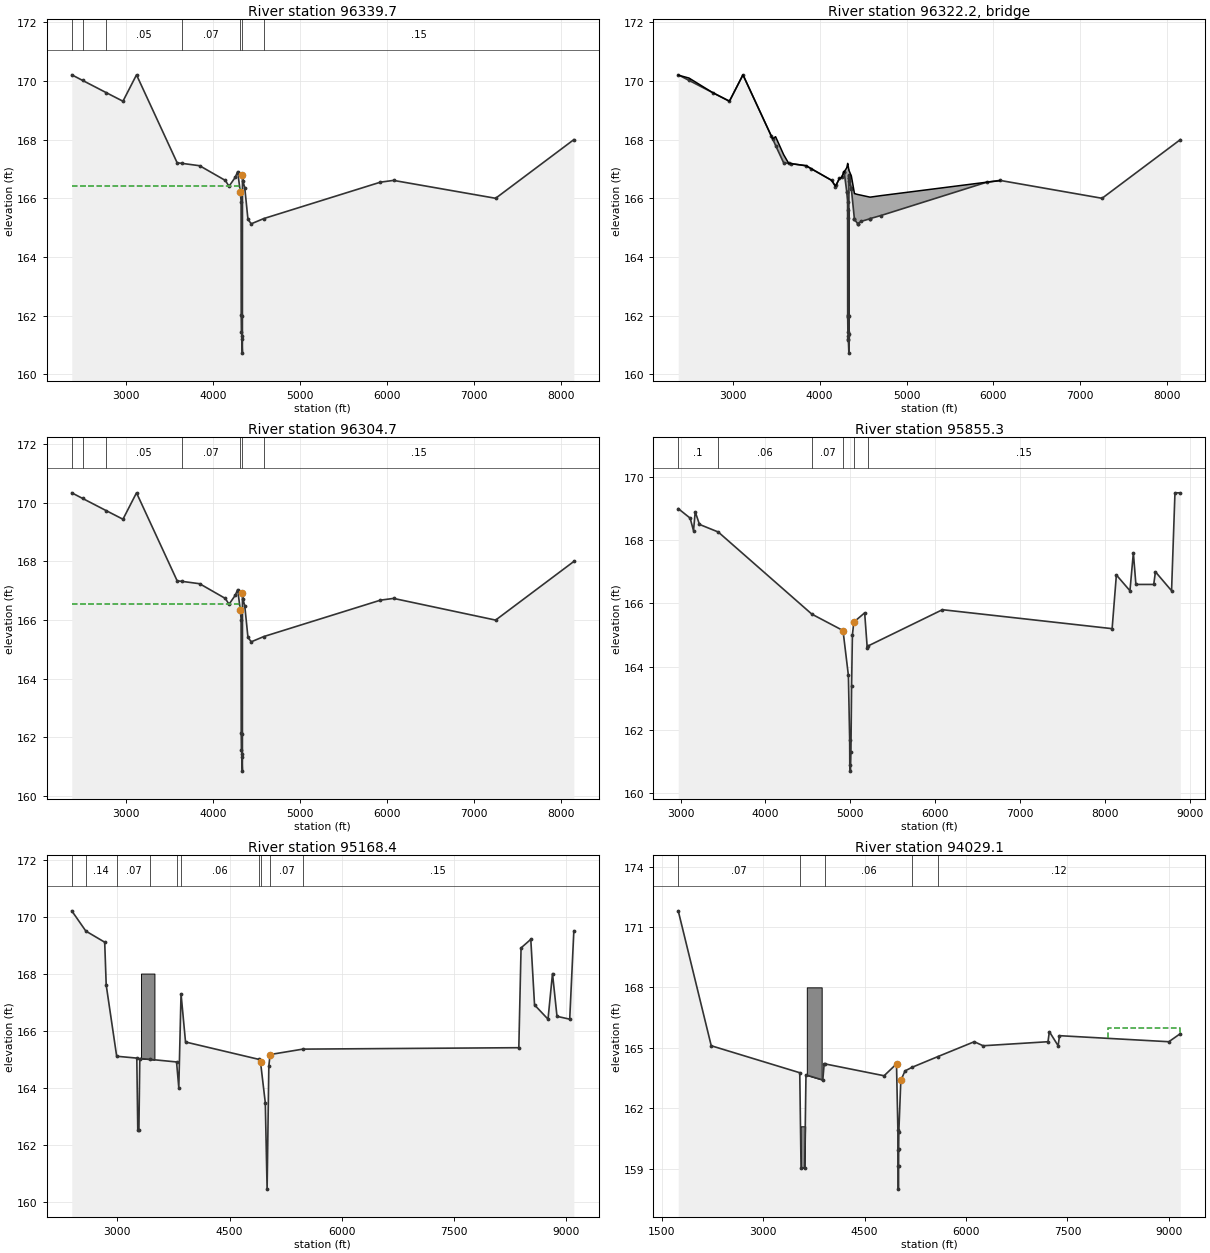
Type RM Length L Ch R = 1 ,96339.7 ,35,35,35
BEGIN DESCRIPTION:
Upstream Section of Bridge/Culvert/Weir
END DESCRIPTION:
XS GIS Cut Line= 6
      3013702.37      13944223.1      3013957.35      13942543.2
      3014306.95      13942286.9      3014746.54      13942309.2
      3014823.76      13942214.8       3015435.4      13938683.7
#Sta/Elev= 30
2373.776  170.212497.877  170.022771.801   169.62962.673  169.313118.557  170.21
3586.211  167.213644.755  167.19 3845.24  167.114139.688  166.614182.989  166.41
4253.311  166.714282.236  166.914312.633  166.224322.073  165.894323.286  162.01
4325.537  161.44  4330.3  161.324330.473  161.214336.795  160.724336.968     162
4337.401  166.794342.511  166.594363.989  166.364400.795  165.284438.727  165.13
4584.219  165.315925.172  166.556075.428  166.61    7250     166    8150     168
#Mann= 7 ,-1 , 0
2373.776      .2       02497.877      .1       02771.801     .05       0
3644.755     .07       04312.633     .06       04337.401     .07       0
4584.219     .15       0
#XS Ineff= 2 , 0
       0 4312.81  166.41 4345.72       0  166.04
Permanent Ineff=
       F       F
Bank Sta=4312.633,4337.401
XS Rating Curve= 0
Skew Angle= 30
Exp/Cntr=.5,.3

Type RM Length L Ch R = 3 ,96322.2 ,,,
BEGIN DESCRIPTION:
SCHROEDER
Structure ID: M100-00-00-17
END DESCRIPTION:
Node Name=Schroeder
Bridge Culvert--1,0,-1,-1, 0
Deck Dist Width WeirC Skew NumUp NumDn MinLoCord MaxHiCord MaxSubmerge Is_Ogee
10,15,2.6,30, 42, 42, , , .95, 0, 1,1,,
 2373.78 2497.88  2771.8 2962.67 3118.56 3441.85 3459.17 3493.81 3586.21 3644.76
 3675.67 3845.24 3902.74 4139.69 4182.99 4188.53 4228.54 4253.31 4282.24  4282.5
 4312.55 4312.63 4322.07 4322.17 4322.25 4323.29 4323.37 4323.55  4336.8 4336.88
 4336.97 4363.99 4365.46  4400.8 4401.23 4438.38 4438.73 4579.02 4584.22 4704.08
 5925.17 6075.43
   170.2   170.1   169.6  169.31  170.21  168.14  168.03   168.1  167.49  167.19
  167.18  167.11  167.01  166.61  166.41  166.44  166.68  166.71  166.91   166.9
  167.04  167.04  167.17  167.17  167.17  167.19  167.19  167.19  166.97  166.96
  166.96  166.77  166.76  166.17  166.16  166.13  166.13  166.04  166.04  166.09
  166.55   166.6
                                                                                
                                                                   166.9  166.89
  166.21  166.21  165.88  165.58  165.77  165.79  165.79  165.79  165.57  165.56
  165.56  166.35  166.31  165.27  165.27  165.12  165.12
  166.54   166.6
 2373.78 2497.88  2771.8 2962.67 3118.56 3441.85 3459.17 3493.81 3586.21 3644.76
 3675.67 3845.24 3902.74 4139.69 4182.99 4188.53 4228.54 4253.31 4282.24  4282.5
 4312.55 4312.63 4322.07 4322.17 4322.25 4323.29 4323.37 4323.55  4336.8 4336.88
 4336.97 4363.99 4365.46  4400.8 4401.23 4438.38 4438.73 4579.02 4584.22 4704.08
 5925.17 6075.43
  170.34  170.15  169.73  169.44  170.34  168.27  168.16   168.1  167.49  167.32
  167.31  167.24  167.14  166.74  166.54  166.57  166.81  166.84  167.04  167.03
  167.04  167.04  167.17  167.17  167.17  167.19  167.19  167.19  166.97  166.96
  166.96  166.77  166.76  166.17  166.16  166.13  166.13  166.17  166.17  166.22
  166.68  166.74
                                                                                
                                                                  167.04  167.03
  166.35  166.35  166.02  165.72  165.91  165.93  165.93  165.93  165.71   165.7
   165.7  166.49  166.45  165.41  165.41  165.26  165.26
  166.68  166.74
Pier Skew= 30
Pier Skew, UpSta & Num, DnSta & Num=  ,4330.473, 2 ,4330.473, 2 , 0 , 0 , 0 ,,
    8.37    8.37
  160.17  167.03
    8.37    8.37
  160.31  167.17
Abutment Skew #Up #Dn= , 2 , 2
4322.0734323.372
  165.77  161.98
4322.0734323.372
  165.91  162.12
Abutment Skew #Up #Dn= , 2 , 2
4336.968 4340.25
  161.99  166.68
4336.968 4340.25
  162.13  166.82
BR Coef= 1 , 1 , 1 ,1.25, 0 ,,,.8,0,2,0,
WSPro=,,,, 1 ,,,, 0 ,,,, 0 ,,,,-1 ,-1 ,-1 , 0 , 0 , 0 , 0 , 0
BR U #Sta/Elev= 54
 2373.78  170.21 2497.88  170.02  2771.8   169.6 2962.67  169.31 3118.56  170.21
 3441.85  168.14 3459.17  168.03 3493.81   167.8 3586.21  167.21 3644.76  167.19
 3675.67  167.18 3845.24  167.11 3902.74  167.01 4139.69  166.61 4182.99   166.4
 4188.53  166.44 4228.54  166.68 4253.31  166.71 4282.24   166.9  4282.5   166.9
 4312.55  166.22 4312.63  166.22 4322.07  165.89 4322.17  165.59 4322.25  165.34
 4323.29  162.01 4323.37  161.99 4323.55  161.94 4325.54  161.44  4330.3  161.32
 4330.47  161.21 4330.91  161.18  4336.8  160.72 4336.88  161.36 4336.97     162
  4337.4  166.79 4337.83  166.77 4340.08  166.69 4340.17  166.68 4342.51  166.59
 4363.99  166.36 4365.46  166.32  4400.8  165.28 4401.23  165.28 4438.38  165.13
 4438.73  165.13 4475.19  165.21 4579.02   165.3 4584.22  165.31 4704.08  165.41
 5925.17  166.55 6075.43  166.61    7250     166    8150     168
BR U #Mann= 7
 2373.78      .2 2497.88      .1  2771.8     .05 3644.76     .07 4312.63     .05
  4337.4     .07 4584.22     .15
BR U Banks=4312.63,4337.4
BR D #Sta/Elev= 54
 2373.78  170.34 2497.88  170.15  2771.8  169.73 2962.67  169.44 3118.56  170.34
 3441.85  168.27 3459.17  168.16 3493.81  167.93 3586.21  167.34 3644.76  167.32
 3675.67  167.31 3845.24  167.24 3902.74  167.14 4139.69  166.74 4182.99  166.53
 4188.53  166.57 4228.54  166.81 4253.31  166.84 4282.24  167.03  4282.5  167.03
 4312.55  166.35 4312.63  166.35 4322.07  166.02 4322.17  165.72 4322.25  165.47
 4323.29  162.14 4323.37  162.12 4323.55  162.07 4325.54  161.57  4330.3  161.45
 4330.47  161.34 4330.91  161.31  4336.8  160.85 4336.88  161.49 4336.97  162.13
  4337.4  166.92 4337.83   166.9 4340.08  166.82 4340.17  166.81 4342.51  166.72
 4363.99  166.49 4365.46  166.45  4400.8  165.41 4401.23  165.41 4438.38  165.26
 4438.73  165.26 4475.19  165.34 4579.02  165.43 4584.22  165.44 4704.08  165.54
 5925.17  166.68 6075.43  166.74    7250     166    8150     168
BR D #Mann= 7
 2373.78      .2 2497.88      .1  2771.8     .05 3644.76     .07 4312.63     .05
  4337.4     .07 4584.22     .15
BR D Banks=4312.63,4337.4
BC Design=,, 0 ,, 0 ,,,,,,
BC HTab HWMax=170.21

Type RM Length L Ch R = 1 ,96304.7 ,672.9,449.4,101.6
BEGIN DESCRIPTION:
Downstream Section of Bridge/Culvert/Weir
END DESCRIPTION:
XS GIS Cut Line= 6
      3013758.25      13944180.3       3013999.5      13942557.5
      3014319.94      13942316.4      3014748.59      13942336.8
      3014849.06      13942233.2      3015486.22       13938693.
#Sta/Elev= 30
2373.776  170.342497.877  170.152771.801  169.732962.673  169.443118.557  170.34
3586.211  167.343644.755  167.32 3845.24  167.244139.688  166.744182.989  166.54
4253.311  166.844282.236  167.044312.633  166.354322.073  166.024323.286  162.14
4325.537  161.57  4330.3  161.454330.473  161.344336.795  160.854336.968  162.13
4337.401  166.924342.511  166.724363.989  166.494400.795  165.414438.727  165.26
4584.219  165.445925.172  166.686075.428  166.74    7250     166    8150     168
#Mann= 7 ,-1 , 0
2373.776      .2       02497.877      .1       02771.801     .05       0
3644.755     .07       04312.633     .06       04337.401     .07       0
4584.219     .15       0
#XS Ineff= 2 , 0
       0 4312.81  166.54 4345.72       0  166.17
Permanent Ineff=
       F       F
Bank Sta=4312.633,4337.401
XS Rating Curve= 0
Skew Angle= 30
Exp/Cntr=.5,.3

Type RM Length L Ch R = 1 ,95855.3 ,967.94,686.9,649.94
BEGIN DESCRIPTION:
Cross Section 95855.3
Cross Section XS48.1
Extended to Drainage Area Divide Right
END DESCRIPTION:
XS GIS Cut Line= 5
      3014191.71     13944350.62      3014212.09      13943463.7
      3014854.35     13942536.01      3014925.71     13942321.92
    3015503.4509   13938707.8748
#Sta/Elev= 30
  2972.8     169  3112.8   168.7  3152.8   168.3  3172.8   168.9  3222.8   168.5
  3443.8  168.26  4546.2  165.66  4913.3  165.14  4976.7  163.72  4991.9  161.66
  4993.1  160.87  5000.9  160.69  5006.7  161.31  5014.3  163.38    5024  165.01
  5041.2  165.41  5168.3   165.7  5198.3   164.6  5206.7  164.65  6083.9   165.8
  8082.6   165.2  8132.6   166.9  8292.6   166.4  8332.6   167.6  8362.6   166.6
  8572.6   166.6  8592.6     167  8782.6   166.4  8822.6   169.5  8885.6   169.5
#Mann= 6 ,-1 , 0
  2972.8      .1       0  3443.8     .06       0  4546.2     .07       0
  4913.3     .06       0  5041.2     .07       0  5206.7     .15       0
Bank Sta=4913.3,5041.2
XS Rating Curve= 0
Exp/Cntr=.3,.1

Type RM Length L Ch R = 1 ,95168.4 ,1323.37,1139.3,1107.5
BEGIN DESCRIPTION:
Cross Section 95168.4
Cross Section XS48
Extended to Drainage Area Divide Right
END DESCRIPTION:
XS GIS Cut Line= 4
    3014900.1882   13945381.3007    3015466.1511   13942834.4679
    3015473.4676   13942801.5436     3015845.255   13938753.0068
#Sta/Elev= 30
    2391   170.2  2579.1  169.49    2831   169.1    2851   167.6    2991   165.1
    3260 165.035    3273  162.53    3288  162.53    3300  165.02 3439.48  164.99
    3791   164.9    3821     164  3850.9  167.29    3911   165.6  4892.2  164.99
  4913.3  164.89  4976.7  163.47  5000.9  160.44    5024  164.76  5041.2  165.16
  5478.3  165.35  8364.1   165.4  8394.1   168.9  8524.1   169.2  8574.1   166.9
  8754.1   166.4  8814.1     168  8874.1   166.5  9044.1   166.4  9099.3   169.5
#Mann= 10 ,-1 , 0
    2391     .06       0  2579.1     .14       0    2991     .07       0
 3439.48     .14       0    3791     .14       0  3850.9     .06       0
  4892.2     .07       0  4913.3     .06       0  5041.2     .07       0
  5478.3     .15       0
#XS Ineff= 2 , 0
       0                    8500       0     169
Permanent Ineff=
       F       F
#Block Obstruct= 2 ,-1
 3315.97 3495.48     168    3250    3300   161.1
Bank Sta=4913.3,5041.2
XS Rating Curve= 0
Exp/Cntr=.3,.1

Type RM Length L Ch R = 1 ,94029.1 ,1483.62,1515.5,1518.76
BEGIN DESCRIPTION:
Cross Section 94029.1
Cross Section XS47
Cross Section M100-00-00-X47
Located At: 2270FT DS SCHROEDER
END DESCRIPTION:
XS GIS Cut Line= 4
      3016326.67      13946171.7      3016572.25      13945715.7
      3016612.94      13939978.7      3016615.56       13938809.
#Sta/Elev= 30
  1744.9   171.8  2232.9   165.1    3542  163.76    3561  159.04    3615  159.04
    3634  163.65  3882.9   163.4  3902.9   164.2  3912.9   164.2  4789.3  163.61
  4972.7   164.2  4993.1  160.91  4995.5  159.93  4996.7  159.13  5000.2  157.98
  5003.7  159.11  5004.6  159.99  5007.2  160.83  5036.6  163.38  5098.7  163.85
    5203  164.03    5583  164.56  6122.9   165.3  6252.9   165.1  7212.9   165.3
  7232.9   165.8  7362.9   165.1  7382.9   165.6    9000   165.3 9169.65   165.7
#Mann= 5 ,-1 , 0
  1744.9     .07       0    3542     .04       0  3912.9     .06       0
    5203     .15       0    5583     .12       0
#XS Ineff= 1 ,-1
 8101.72 9169.65     166
Permanent Ineff=
       F
#Block Obstruct= 2 ,-1
    3646    3866     168    3542    3635   161.1
Bank Sta=4972.7,5036.6
XS Rating Curve= 0
Exp/Cntr=.3,.1

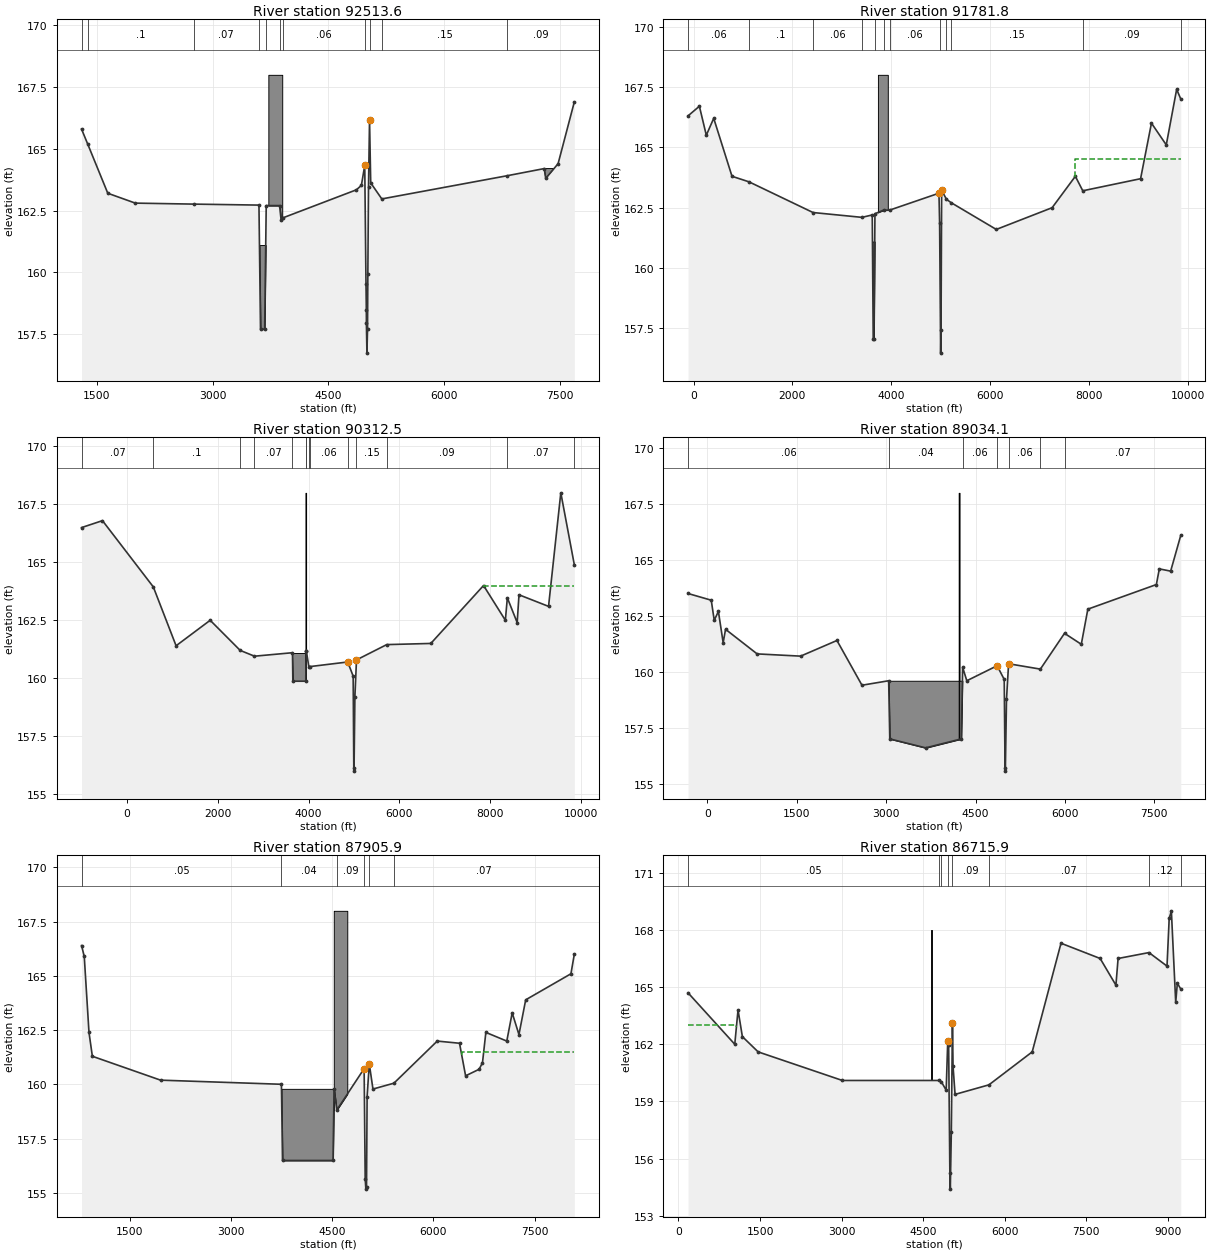
Type RM Length L Ch R = 1 ,92513.6 ,758.43,731.8,730.73
BEGIN DESCRIPTION:
Cross Section 92513.6
Cross Section XS46
END DESCRIPTION:
XS GIS Cut Line= 3
      3017580.65      13946612.3      3017957.67      13946026.2
      3018221.43      13940342.3
#Sta/Elev= 30
  1300.5   165.8  1379.5   165.2  1640.5   163.2  1997.4   162.8  2753.4  162.76
    3600  162.72    3620  157.69    3674  157.69  3694.1   162.7  3867.4   162.7
  3887.4   162.1    3916  162.21  4863.2  163.34  4927.6  163.52  4971.1  164.33
  4987.1  159.54  4991.6  158.48  4992.4  157.95  4999.4  156.72  5007.2  157.69
  5011.2  159.93  5019.8  163.46  5033.2  166.16  5048.5  163.62  5192.2  162.97
  6816.6  163.91  7297.4   164.2  7317.4   163.8  7477.4   164.4  7687.4   166.9
#Mann= 11 ,-1 , 0
  1300.5     .07       0  1379.5      .1       0  2753.4     .07       0
    3600     .04       0  3694.1     .05       0  3867.4     .05       0
    3916     .06       0  4971.1     .06       0  5033.2     .06       0
  5192.2     .15       0  6816.6     .09       0
#Block Obstruct= 3 ,-1
 3721.61 3901.59     168    7296  7687.4   164.2    3600    3694   161.1
Bank Sta=4971.1,5033.2
XS Rating Curve= 0
Exp/Cntr=.3,.1

Type RM Length L Ch R = 1 ,91781.8 ,1526.24,1469.3,1461.05
XS GIS Cut Line= 4
      3018556.75      13948180.3      3018821.14      13943213.6
       3018827.6      13943039.1      3019053.47      13938220.9
#Sta/Elev= 30
    -113   166.3     117   166.7     257   165.5     407   166.2     777   163.8
  1121.8  163.57    2417   162.3    3407   162.1    3615   162.2    3635  157.06
    3649  157.06  3669.9  162.25  3845.9   162.4    3967   162.4 4965.27   163.1
  4978.4  161.85  4999.4  156.48  5007.2  157.45  5019.8  163.22  5116.6  162.85
  5210.1  162.71  6125.4   161.6  7255.4   162.5  7725.4   163.8  7875.4   163.2
  9045.4   163.7  9265.4     166  9565.4   165.1  9775.4   167.4  9858.8     167
#Mann= 12 ,-1 , 0
    -113     .06       0  1121.8      .1       0    2417     .06       0
    3407     .05       0  3669.9     .06       0  3845.9     .05       0
    3967     .06       0  4978.4     .06       0  5116.6     .06       0
  5210.1     .15       0  7875.4     .09       0  9858.8      .2       0
#XS Ineff= 2 ,-1
                            7720  9858.8   164.5
Permanent Ineff=
       F       F
#Block Obstruct= 2 ,-1
  3729.9  3929.9     168    3615    3670   161.1
Bank Sta=4965.27,5019.8
XS Rating Curve= 0
Exp/Cntr=.3,.1

Type RM Length L Ch R = 1 ,90312.5 ,1273.02,1278.4,1271.98
BEGIN DESCRIPTION:
Cross Section Xs45.5
END DESCRIPTION:
XS GIS Cut Line= 4
      3019959.79      13949225.1      3020279.34      13943308.3
      3020279.34      13943189.1      3020470.61      13938395.8
#Sta/Elev= 30
  -994.3   166.5  -534.3   166.8   584.5  163.94  1085.7   161.4  1835.7   162.5
  2495.9   161.2  2810.6  160.95  3646.5   161.1  3654.5  159.87  3938.5  159.87
  3946.5  161.17 3952.54  161.16  4005.7   160.5  4024.5   160.5  4862.1   160.7
  4981.7  160.09  4995.5  156.13  5000.7  155.99  5019.9   159.2    5055  160.79
  5720.1  161.45  6690.4   161.5  7850.4     164  8330.4   162.5  8373.8  163.47
  8590.4   162.4  8630.4   163.6  9280.4   163.1  9550.4     168  9847.4   164.9
#Mann= 14 ,-1 , 0
  -994.3     .07       0   584.5      .1       0  2495.9     .06       0
  2810.6     .07       0  3646.5     .04       0  3946.5     .07       0
 3952.54     .05       0  4005.7     .07       0  4024.5     .06       0
  4862.1     .06       0    5055     .15       0  5720.1     .09       0
  8373.8     .07       0  9847.4      .2       0
#XS Ineff= 2 , 0
       0                    7845       0     164
Permanent Ineff=
       F       T
#Block Obstruct= 3 ,-1
  3931.5  3946.5     168  3646.5  3931.5   161.1  3941.5  3946.5   161.1
Bank Sta=4862.1,5055
XS Rating Curve= 0
Exp/Cntr=.3,.1

Type RM Length L Ch R = 1 ,89034.1 ,1052.66,1128.2,1092.84
BEGIN DESCRIPTION:
Cross Section 89034.1
Cross Section XS45
END DESCRIPTION:
XS GIS Cut Line= 3
      3021158.48      13948892.6      3021516.78      13943422.5
      3021725.08      13940640.3
#Sta/Elev= 30
  -326.3   163.5    63.7   163.2   113.7   162.3   183.7   162.7   263.7   161.3
   303.7   161.9   833.7   160.8  1563.7   160.7  2173.7   161.4  2593.7   159.4
  3042.1   159.6  3060.5     157  3662.1   156.6  4261.3     157  4283.7   160.2
  4353.7   159.6  4862.1  160.27  4981.7  159.66  4995.5   155.7  5000.7  155.56
  5019.9  158.77    5055  160.36  5588.5  160.12  5993.9  161.72  6275.5  161.23
  6385.5   162.8  7535.5   163.9  7585.5   164.6  7775.5   164.5  7945.5   166.1
#Mann= 7 ,-1 , 0
  -326.3     .06       0  3042.1     .04       0  4283.7     .06       0
  4862.1     .06       0    5055     .06       0  5588.5     .09       0
  5993.9     .07       0
#Block Obstruct= 3 ,-1
  4217.1  4232.1     168  3042.1  4217.1   159.6  4227.1  4282.1   159.6
Bank Sta=4862.1,5055
XS Rating Curve= 0
Exp/Cntr=.3,.1

Type RM Length L Ch R = 1 ,87905.9 ,1083.65,1190,1262.85
BEGIN DESCRIPTION:
Cross Section 87905.9
Cross Section XS44
Cross Section M100-00-00-X44
Located At: 2560FT US TELGE
END DESCRIPTION:
XS GIS Cut Line= 3
      3022171.04      13948062.8      3022591.68      13943876.4
      3022747.72      13940790.4
#Sta/Elev= 30
   789.6   166.4   829.6   165.9   899.6   162.4   949.6   161.3  1959.6   160.2
  3749.6  160.01  3765.6   156.5  4513.6   156.5  4529.6   159.8    4569  158.82
  4974.4  160.73    4990  155.66    5000  155.18  5009.7  155.27  5018.5  159.44
  5050.7  160.95  5105.1  159.79  5415.4  160.06    6057     162    6387   161.9
    6477   160.4    6677   160.7    6727     161    6777   162.4    7087     162
    7167   163.3    7267   162.3    7367   163.9    8037   165.1    8087     166
#Mann= 6 ,-1 , 0
   789.6     .05       0  3749.6     .04       0    4569     .09       0
  4974.4     .06       0  5050.7     .09       0  5415.4     .07       0
#XS Ineff= 1 ,-1
    6420    8087   161.5
Permanent Ineff=
       T
#Block Obstruct= 2 ,-1
  4524.8  4724.8     168  3749.6  4524.8   159.8
Bank Sta=4974.4,5050.7
XS Rating Curve= 0
Exp/Cntr=.3,.1

Type RM Length L Ch R = 1 ,86715.9 ,450.93,496.8,506.31
BEGIN DESCRIPTION:
Cross Section 86715.9
Cross Section XS43
END DESCRIPTION:
XS GIS Cut Line= 3
      3022926.09      13948964.2       3023809.9       13943757.
      3024072.65      13939982.9
#Sta/Elev= 30
   175.2   164.7  1035.2     162  1095.2   163.8  1175.2   162.4  1465.2   161.6
  3015.2   160.1  4795.2   160.1  4833.8  160.04  4924.4  159.59  4953.4  162.19
  4969.6  161.97    4992  155.27  5000.3   154.4  5019.1   157.4  5039.7  163.13
  5050.5  160.86  5087.8  159.37  5710.5  159.87    6507   161.6    7037   167.3
    7757   166.5    8047   165.1    8087   166.5    8655  166.81    8987   166.1
    9027   168.6    9067     169    9147   164.2    9177   165.2  9240.2   164.9
#Mann= 8 ,-1 , 0
   175.2     .05       0  4795.2     .05       0  4833.8     .09       0
  4953.4     .06       0  5039.7     .09       0  5710.5     .07       0
    8655     .12       0  9240.2      .2       0
#XS Ineff= 1 ,-1
   175.2    1065     163
Permanent Ineff=
       F
#Block Obstruct= 1 ,-1
  4645.9  4669.9     168
Bank Sta=4953.4,5039.7
XS Rating Curve= 0
Exp/Cntr=.3,.1