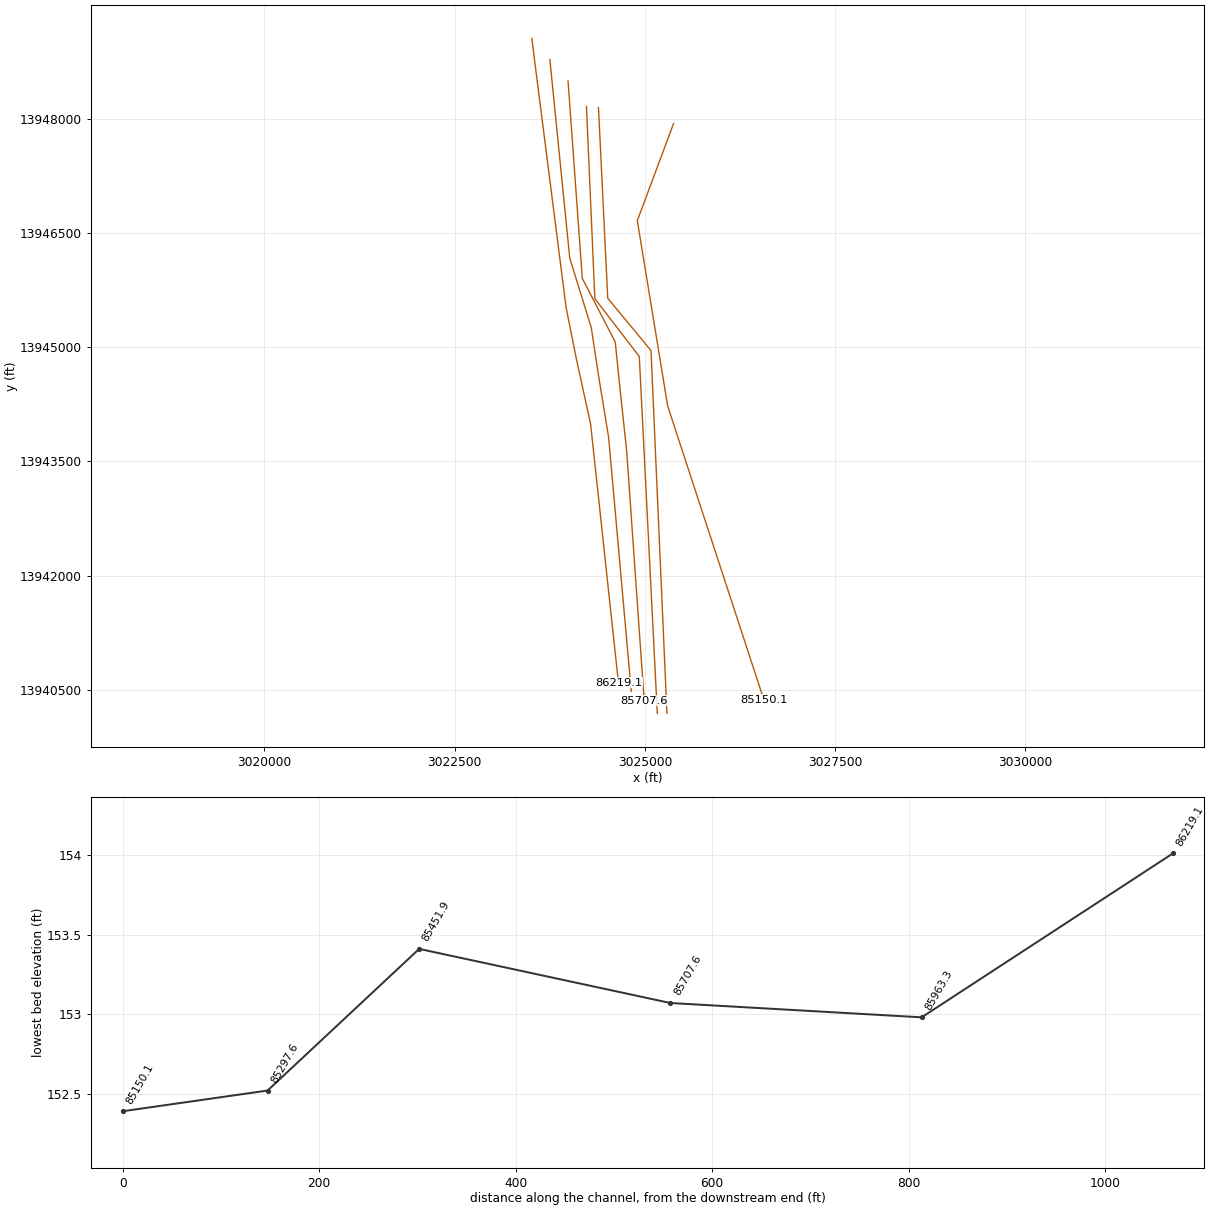
HEC-RAS study M100-00-00.prj: M100-00-00

--- M100-00-00.g01 (geometry) --- (continued)

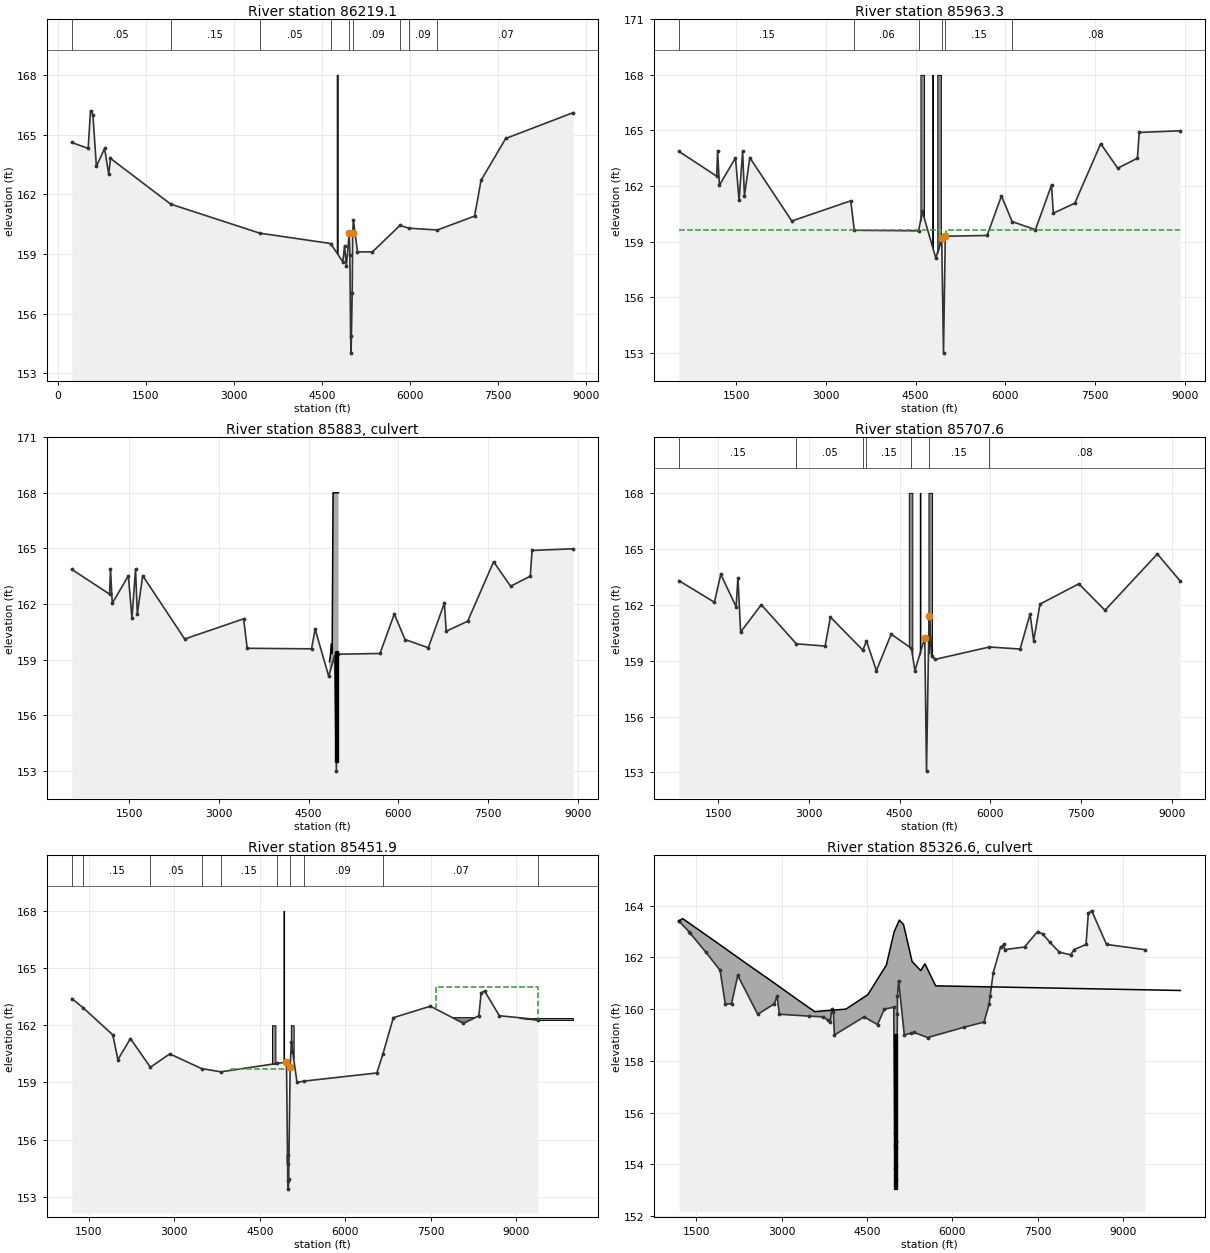
Type RM Length L Ch R = 1 ,86219.1 ,132.67,255.73,245.47
BEGIN DESCRIPTION:
Cross Section 86219.1
Cross Section XS42.7
END DESCRIPTION:
XS GIS Cut Line= 6
      3023513.63     13949054.08      3023638.23     13948075.51
        3023964.     13945523.69       3024104.9     13944819.16
      3024286.06     13943993.86      3024652.25      13940593.5
#Sta/Elev= 30
   241.9   164.6   521.9   164.3   561.9   166.2   601.9     166   661.9   163.4
   801.9   164.3   871.9     163   901.9   163.8  1927.9   161.5  3445.2  160.04
  4653.2  159.52  4859.4   158.6  4889.4   159.4  4919.4   158.4  4969.6  160.05
  4979.8  158.92    4992  154.88  5000.3  154.01  5019.1  157.01  5027.6  160.05
  5039.4   160.7  5109.4   159.1  5364.3   159.1  5832.8  160.43  5984.6  160.29
    6471   160.2  7104.3   160.9  7214.3   162.7  7634.3   164.8  8784.3   166.1
#Mann= 9 ,-1 , 0
   241.9     .05       0  1927.9     .15       0  3445.2     .05       0
  4653.2     .15       0  4969.6     .06       0  5027.6     .09       0
  5832.8     .07       0  5984.6     .09       0    6471     .07       0
#Block Obstruct= 1 ,-1
    4755    4773     168
Bank Sta=4969.6,5027.6
XS Rating Curve= 0
Exp/Cntr=.5,.3

Type RM Length L Ch R = 1 ,85963.3 ,132.67,255.73,245.47
BEGIN DESCRIPTION:
Added Cross Section XS85963.3
END DESCRIPTION:
XS GIS Cut Line= 6
      3023751.04     13948776.13     3024012.555     13946168.55
     3024295.249     13945255.94     3024388.908     13944635.72
     3024523.277     13943816.31     3024820.661     13940479.66
#Sta/Elev= 30
   541.6  163.87 1174.47  162.53 1189.41  163.89 1219.31  162.04 1488.37  163.52
 1548.16  161.22 1607.94  163.88 1637.84  161.46 1727.51  163.53 2429.94  160.11
  3415.2   161.2 3474.71  159.61 4550.84  159.58 4610.58  160.64  4837.8   158.1
  4935.8  159.21  4965.8  152.98  4995.8  159.29 5694.98  159.33 5934.26  161.46
 6113.72  160.08 6502.54  159.64 6771.73  162.05 6801.64  160.53 7160.55  161.07
 7594.24  164.28 7878.38  162.96 8207.39   163.5  8237.3  164.89 8925.22  164.98
#Mann= 6 ,-1 , 0
   541.6     .15       0 3474.71     .06       0 4550.84    .045       0
  4935.8     .06       0  4995.8     .15       0 6113.72     .08       0
#XS Ineff= 2 , 0
       0  4930.5   159.6  4999.5       0   159.6
Permanent Ineff=
       F       F
#Block Obstruct= 3 ,-1
    4580    4640     168    4862    4922     168    4775    4790     168
Bank Sta=4935.8,4995.8
XS Rating Curve= 0
Exp/Cntr=.5,.3

Type RM Length L Ch R = 2 ,85883   ,,,
BEGIN DESCRIPTION:
Grand Parkway South Frontage Road
END DESCRIPTION:
Bridge Culvert--1,0,-1,-1, 0
Deck Dist Width WeirC Skew NumUp NumDn MinLoCord MaxHiCord MaxSubmerge Is_Ogee
80,30,2.6,0, 11, 7, , , .95, 0, 0,0,,
 4850.47 4865.42 4880.37 4895.33 4910.28 4925.23 4940.19 4955.14 4970.09 4985.05
    5000
  158.88  159.21  159.85  159.32     168     168     168     168     168     168
     168
                                                                                
        
4915.187 4930.144945.0934960.046    49754989.9545004.907
     168     168     168     168     168     168     168
                                                        
BR Coef=-1 , 0 , 0 ,, 0 ,,,.8,-1,,0,
WSPro=,,,, 1 ,,,, 0 ,,,, 0 ,,,,-1 ,-1 ,-1 , 0 , 0 , 0 , 0 , 0
Multiple Barrel Culv=2,6,10,164.6,.015,.5,1,10,1,153.45,153.32, 4,Culvert #1  , 0 ,10
  4945.5  4923.8  4958.5  4936.8  4971.5  4949.8  4984.5  4962.8
Culvert Bottom n=.015
BC Design=,, 0 ,, 0 ,,,,,,
BC HTab HWMax=164.98

Type RM Length L Ch R = 1 ,85707.6 ,132.67,255.73,245.47
BEGIN DESCRIPTION:
Added Cross Section XS85707.6
END DESCRIPTION:
XS GIS Cut Line= 6
      3023989.92     13948493.29     3024177.432     13945902.23
      3024610.69     13945067.23     3024672.915     13944452.27
     3024760.494     13943638.75     3024990.177     13940360.89
#Sta/Elev= 30
   846.3  163.29 1434.85  162.13 1539.57  163.63  1793.9  161.89 1823.83  163.45
 1868.52  160.53 2210.39     162  2790.1   159.9 3265.76  159.78 3354.95  161.33
 3891.17  159.56 3950.78  160.06 4114.69  158.46 4359.38  160.42 4693.91  159.66
 4752.78  158.46  4915.1  160.23  4944.1  153.07  4986.1  161.38  5027.1  159.23
 5092.22  159.07 5985.48  159.73  6493.3  159.62  6657.6   161.5 6717.34  160.07
 6821.89  162.03 7464.14  163.12 7897.28   161.7 8763.56  164.72 9144.23  163.26
#Mann= 7 ,-1 , 0
   846.3     .15       0  2790.1     .05       0 3891.17     .06       0
 3950.78     .15       0 4693.91    .045       0  4986.1     .15       0
 5985.48     .08       0
#XS Ineff= 2 , 0
       0    4918  159.42  4977.8       0  159.42
Permanent Ineff=
       F       F
#Block Obstruct= 3 ,-1
    4650    4710     168    4976    5036     168    4832 4844.35     168
Bank Sta=4915.1,4986.1
XS Rating Curve= 0
Exp/Cntr=.5,.3

Type RM Length L Ch R = 1 ,85451.9 ,145.4,154.3,166.6
XS GIS Cut Line= 4
      3024231.86     13948160.53      3024342.31     13945635.91
      3024926.13     13944878.53      3025162.81     13940192.21
#Sta/Elev= 30
    1201   163.4  1396.6  162.93  1921.1   161.5  2011.1   160.2  2231.1   161.3
  2581.1   159.8  2921.1   160.5  3478.1  159.73  3820.3  159.56  4804.4     160
    4969  160.07  4988.2  154.73  4989.8  155.21  4990.7  153.84    5000  153.41
  5007.4  153.92  5033.1  159.83  5054.4   161.1  5154.4     159  5268.3  159.07
  6554.4   159.5  6662.5  160.51  6844.4   162.4  7494.4     163  8074.4   162.1
  8344.4   162.5  8384.4   163.7  8444.4   163.8  8704.4   162.5  9376.7   162.3
#Mann= 10 ,-1 , 0
    1201     .07       0  1396.6     .15       0  2581.1     .05       0
  3478.1    .045       0  3820.3     .15       0  4804.4     .05       0
  5033.1     .15       0  5268.3     .09       0  6662.5     .07       0
  9376.7      .2       0
#XS Ineff= 3 ,-1
    7600  9376.7     164    4000    4969   159.7  5032.5    5100   159.7
Permanent Ineff=
       T       F       F
#Block Obstruct= 4 ,-1
    4715    4775     162    5045    5095     162    7770   10000   162.4
    4915 4927.35     168
Bank Sta=4969,5033.1
XS Rating Curve= 0
Exp/Cntr=.5,.3

Type RM Length L Ch R = 2 ,85326.6 ,,,
BEGIN DESCRIPTION:
TELGE
Structure ID: M100-00-00-16
END DESCRIPTION:
Node Name=Telge Rd
Bridge Culvert--1,0,-1,-1, 0
Deck Dist Width WeirC Skew NumUp NumDn MinLoCord MaxHiCord MaxSubmerge Is_Ogee
10,65,2.6,0, 27, 27, , , .95, 0, 1,1,,
    1197  1262.5  1262.6  1426.2    2007    2197    2217    2237    2257    2307
    2487    2877    3297    3387  3583.4    3724  4129.6    4515    4839    4975
    5067    5141    5291    5442    5517    5705   10000
   163.4   163.5   163.5  163.25  162.35  162.05  162.02  161.99  161.96  161.88
   161.6     161  160.34   160.2   159.9  159.93     160  160.56   161.7  162.98
  163.44  163.27  161.84  161.49  161.75   160.9  160.72
                                                                                
                                                                                
                                                        
    1197  1262.5  1262.6  1426.2    2007    2197    2217    2237    2257    2307
    2487    2877    3297    3387  3583.4    3724  4129.6    4515    4839    4975
    5067    5141    5291    5442    5517    5705   10000
   163.4   163.5   163.5  163.25  162.35  162.05  162.02  161.99  161.96  161.88
   161.6     161  160.34   160.2   159.9  159.93     160  160.56   161.7  162.98
  163.44  163.27  161.84  161.49  161.75   160.9  160.72
                                                                                
                                                                                
                                                        
Abutment Skew #Up #Dn= , 2 , 2
  4967.8  4969.1
  160.23  159.96
  4967.8  4969.1
  159.42  159.15
BR Coef= 1 , 1 , 1 ,1.25, 0 ,,,.8,0,2,0,
WSPro=,,,, 1 ,,,, 0 ,,,, 0 ,,,,-1 ,-1 ,-1 , 0 , 0 , 0 , 0 , 0
Multiple Barrel Culv=2,6,10,142,.015,.5,1,8,1,153.04,152.24, 4,Culvert #1  , 0 ,10
  4980.5  4980.5  4993.5  4993.5  5005.5  5005.5  5017.5  5017.5
Culvert Bottom n=.015
BR U #Sta/Elev= 60
    1201   163.4  1201.1   163.4  1371.1     163  1396.6  162.93  1671.1   162.2
  1921.1   161.5  2011.1   160.2  2121.1   160.2  2231.1   161.3  2581.1   159.8
  2871.1   160.2  2921.1   160.5  2961.1   159.8  3478.1  159.73  3728.1   159.7
  3820.3  159.56  3858.1   159.5  3878.1     160  3908.1   159.9  3928.1     159
  4448.1   159.7  4684.4   159.4  4804.4     160    4969  160.07  4988.2  154.73
    4989  154.64  4989.8  155.21  4990.7  153.84    5000  153.41  5007.4  153.92
    5011  154.66  5011.5  154.87  5012.3  154.92  5033.1  159.83  5034.4   160.5
  5054.4   161.1  5154.4     159  5268.3  159.07  5324.4   159.1  5564.4   158.9
  6204.4   159.3  6554.4   159.5  6644.4   160.2  6662.5  160.51  6714.4   161.4
  6844.4   162.4  6904.4   162.5  6914.4   162.3  7264.4   162.4  7494.4     163
  7584.4   162.9  7704.4   162.6  7874.4   162.2  8074.4   162.1  8134.4   162.3
  8344.4   162.5  8384.4   163.7  8444.4   163.8  8704.4   162.5  9376.7   162.3
BR U #Mann= 10
    1201     .07  1396.6     .15  2581.1     .05  3478.1    .045  3820.3     .15
  4804.4     .05  5033.1     .15  5268.3     .09  6662.5     .07  9376.7      .2
BR D #Sta/Elev= 71
    1197  163.41  1262.5  163.23  1262.6  163.23  1426.2  162.79    2007  161.21
    2237  160.01    2257  159.91    2307  159.61    2487  159.51    2877  159.91
    3297  159.81    3387  159.61  3583.4  159.67    3724  159.71  4129.6  159.44
  4169.6  159.41  4175.3  159.41  4215.3  159.51  4543.7   159.3  4683.8  159.21
  4743.7  159.21  4833.8  159.21  4848.2  159.25  4868.2  159.31  4903.9   160.8
  4904.5  160.83  4962.3   159.9  4967.5  159.82  4967.8  159.86 4967.91  159.87
    4968  159.88  4968.3  159.92    4969     160  4969.1  159.97  4988.2  154.66
    4989  154.57  4989.8  155.14  4990.7  153.77    4997  153.48    5000  152.52
  5007.4  153.85    5011  154.59  5011.5   154.8  5012.3  154.85  5032.9  159.74
    5033  159.76  5033.1  159.76 5033.69  159.78  5033.8  159.79  5033.9  159.79
  5037.2  159.91    5090  159.57  5163.8  159.21  5233.8  159.21  5309.9  159.31
  5573.8  159.01  6153.8  159.11  6154.1  159.11  6253.8  159.61  6653.8  159.91
  6690.1  159.89  6953.8  159.71  7073.8  160.61  7113.8  160.81  7233.8  161.21
  7253.8  161.61  7263.8  162.21  7393.8  163.01  7626.7  163.13  8393.8  163.51
  9411.8  162.91
BR D #Mann= 8
    1197     .07  1426.2     .15  4743.7    .045    4969     .08    5033     .45
  5309.9     .05  7253.8     .07  7626.7     .05
BC Design=,, 0 ,, 0 ,,,,,,
BC HTab HWMax=163.51

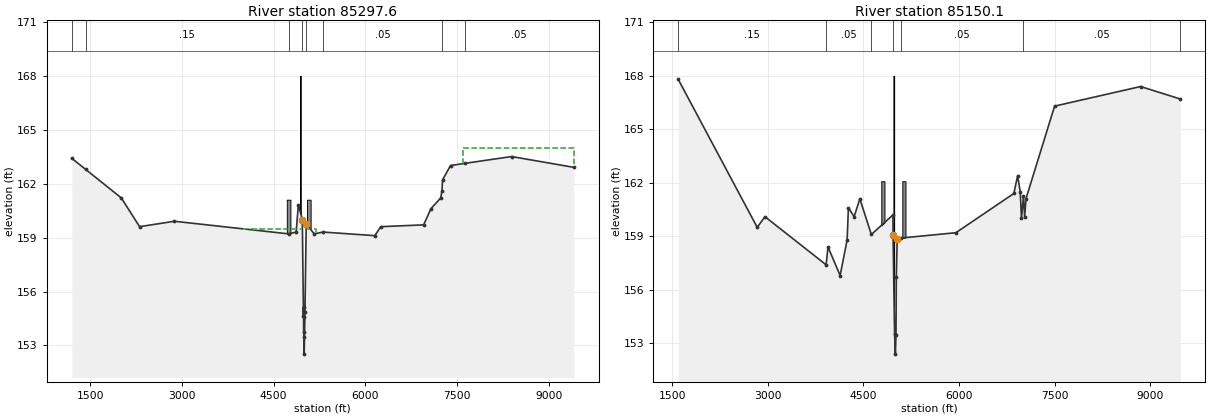
Type RM Length L Ch R = 1 ,85297.6 ,569.3,147.5,196.3
BEGIN DESCRIPTION:
Downstream Section of Bridge/Culvert/Weir
END DESCRIPTION:
XS GIS Cut Line= 4
      3024389.98      13948145.3      3024511.75       13945642.
       3025080.3       13944955.      3025289.37      13940192.7
#Sta/Elev= 30
    1197  163.41  1426.2  162.79    2007  161.21    2307  159.61    2877  159.91
  4743.7  159.21  4868.2  159.31  4904.5  160.83    4969     160  4988.2  154.66
    4989  154.57  4989.8  155.14  4990.7  153.77    4997  153.48    5000  152.52
  5012.3  154.85    5033  159.76  5163.8  159.21  5309.9  159.31  6154.1  159.11
  6253.8  159.61  6953.8  159.71  7073.8  160.61  7233.8  161.21  7253.8  161.61
  7263.8  162.21  7393.8  163.01  7626.7  163.13  8393.8  163.51  9411.8  162.91
#Mann= 8 ,-1 , 0
    1197     .07       0  1426.2     .15       0  4743.7    .045       0
    4969     .08       0    5033     .45       0  5309.9     .05       0
  7253.8     .07       0  7626.7     .05       0
#XS Ineff= 3 ,-1
    4000    4970   159.5  5032.5    5200   159.5    7600  9411.8     164
Permanent Ineff=
       F       F       F
#Block Obstruct= 3 ,-1
    4715    4775  161.11    5045    5105  161.11    4932 4944.35     168
Bank Sta=4969,5033
XS Rating Curve= 0
Exp/Cntr=.5,.3

Type RM Length L Ch R = 1 ,85150.1 ,677,679.5,679.7
BEGIN DESCRIPTION:
Cross Section 84470.6
END DESCRIPTION:
XS GIS Cut Line= 4
      3025376.98     13947936.01      3024900.32     13946660.62
      3025299.68     13944225.78      3026562.19     13940373.83
#Sta/Elev= 30
  1592.2   167.8  2832.2   159.5  2953.8   160.1  3913.8   157.4  3943.8   158.4
  4133.8   156.8  4243.8   158.8  4263.8   160.6  4353.8   160.1  4443.8   161.1
  4623.8   159.1  4963.8   160.2  4964.8  159.07  4988.8  153.53  5001.2  152.39
  5011.1  153.49  5016.4156.7415 5029.61  158.85  5083.8   158.9  5951.1   159.2
  6861.1   161.4  6921.1   162.4  6961.1   161.5  6981.1     160  7012.1  161.24
  7031.1   160.1  7051.1   161.1  7501.1   166.3  8851.1   167.4  9474.7   166.7
#Mann= 7 ,-1 , 0
  1592.2     .15       0  3913.8     .05       0  4623.8    .045       0
  4964.8     .04       0  5083.8     .05       0  7012.1     .05       0
  9474.7      .2       0
#XS Ineff= 2 , 0
       0    4250     159               0
Permanent Ineff=
       T       F
#Block Obstruct= 3 ,-1
    4780    4830  162.09    5110    5160  162.09    4970 4982.35     168
Bank Sta=4964.8,5029.61
XS Rating Curve= 0
Exp/Cntr=.5,.3