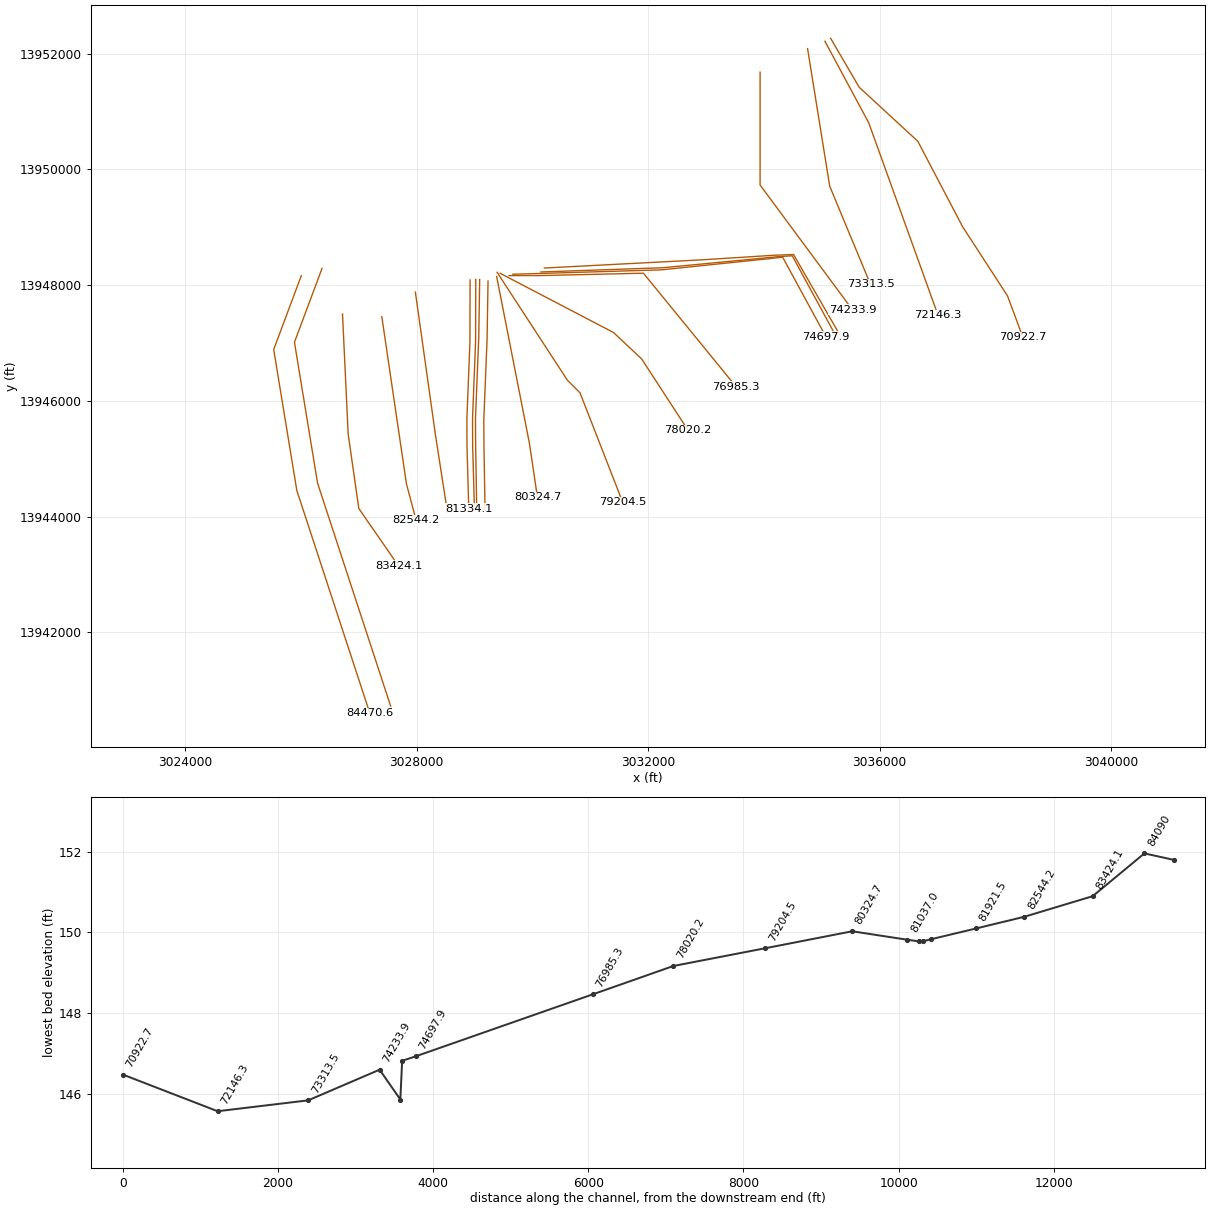
HEC-RAS study M100-00-00.prj: M100-00-00

--- M100-00-00.g01 (geometry) --- (continued)

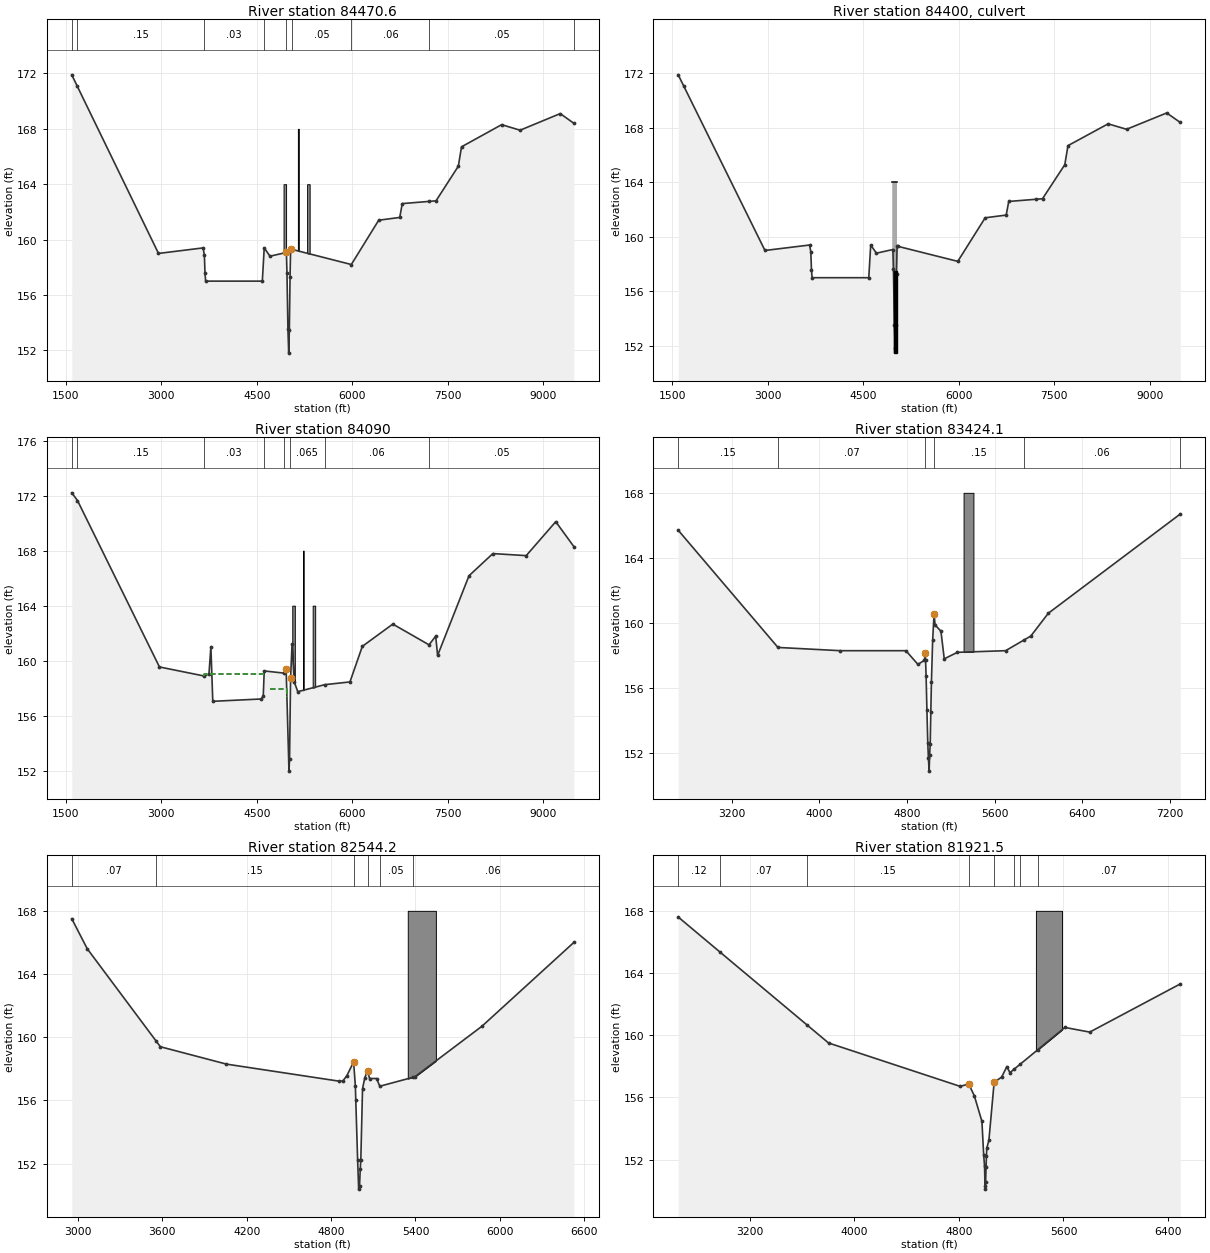
Type RM Length L Ch R = 1 ,84470.6 ,390.88,380,371.13
BEGIN DESCRIPTION:
Cross Section 84470.6
Cross Section XS42.5
END DESCRIPTION:
XS GIS Cut Line= 4
      3026008.32      13948163.8      3025531.66      13946888.4
      3025931.03      13944453.6      3027193.54      13940601.6
#Sta/Elev= 30
  1595.2   171.9  1680.2  171.09  2956.8     159  3656.8   159.4  3676.8   158.9
  3686.8   157.6  3696.8     157  4586.8     157  4616.8   159.4  4706.8   158.8
  4964.8  159.07  4973.6  157.62  4988.8  153.53  5001.2   151.8  5011.1  153.49
  5022.1   157.3 5031.41  159.32  5046.8   159.3  5984.1   158.2  6414.1   161.4
  6744.1   161.6  6784.1   162.6  7210.9  162.76  7314.1   162.8  7664.1   165.3
  7714.1   166.7  8344.1   168.3  8634.1   167.9  9264.1   169.1  9477.7   168.4
#Mann= 9 ,-1 , 0
  1595.2     .07       0  1680.2     .15       0  3676.8     .03       0
  4616.8    .045       0  4964.8     .04       0  5046.8     .05       0
  5984.1     .06       0  7210.9     .05       0  9477.7      .2       0
#XS Ineff= 3 ,-1
    3600  4616.8     159  4616.8    4970  158.11    5026    5600  158.11
Permanent Ineff=
       T       F       F
#Block Obstruct= 3 ,-1
    4920    4960     164    5290    5330     164    5145    5160     168
Bank Sta=4964.8,5031.41
XS Rating Curve= 0
Exp/Cntr=.5,.3

Type RM Length L Ch R = 2 ,84400   ,,,
BEGIN DESCRIPTION:
Grand Parkway North Frontage Road
END DESCRIPTION:
Bridge Culvert--1,0,-1,-1, 0
Deck Dist Width WeirC Skew NumUp NumDn MinLoCord MaxHiCord MaxSubmerge Is_Ogee
1,40,2.6,0, 6, 5, , , .95, 0, 0,0,,
 4955.15  4970.1 4985.05    5000 5014.95    5030
     164     164     164     164     164     164
                                                
  4970.1 4985.05    5000 5014.95  5029.9
     164     164     164     164     164
                                        
BR Coef=-1 , 0 , 0 ,, 0 ,,,.8,-1,,0,
WSPro=,,,, 1 ,,,, 0 ,,,, 0 ,,,,-1 ,-1 ,-1 , 0 , 0 , 0 , 0 , 0
Multiple Barrel Culv=2,6,10,207,.015,.5,1,10,1,151.46,151.31, 4,Culvert #1  , 0 ,10
  4980.5  4980.5  4993.5  4993.5  5005.5  5005.5  5017.5  5017.5
Culvert Bottom n=.015
BC Design=,, 0 ,, 0 ,,,,,,
BC HTab HWMax=171.9

Type RM Length L Ch R = 1 ,84090   ,685.58,666.5,650.94
BEGIN DESCRIPTION:
Added Cross Section XS84090
END DESCRIPTION:
XS GIS Cut Line= 4
      3026366.84     13948289.93     3025890.184     13947014.53
     3026289.554     13944579.73     3027552.064     13940727.73
#Sta/Elev= 30
  1595.2  172.21 1684.97  171.65 2971.72  159.54 3674.53  158.88  3749.3  159.03
 3779.21  161.01 3809.11  157.04 4571.75  157.21 4601.65  157.44 4616.61  159.25
 4930.63  159.09 4960.54  159.41  5005.4  151.96  5014.4  152.87  5030.4  158.72
  5053.4  161.18  5088.4  158.45  5143.4  157.74  5565.9  158.25 5962.59  158.45
 6157.04  161.04  6635.7  162.66  7204.1  161.15 7308.81  161.78 7338.72  160.38
 7832.34  166.18 8206.29  167.79 8729.82  167.64 9193.52  170.11  9477.7   168.3
#Mann= 8 ,-1 , 0
  1595.2     .07       0 1684.97     .15       0 3674.53     .03       0
 4616.61     .15       0 4930.63     .08       0  5014.4    .065       0
  5565.9     .06       0  7204.1     .05       0
#XS Ineff= 3 ,-1
 3674.53    4616     159    4700    4973  157.96    5029    5600  157.96
Permanent Ineff=
       T       F       F
#Block Obstruct= 3 ,-1
    5057    5097     164    5377    5417     164    5225    5237     168
Bank Sta=4960.54,5030.4
XS Rating Curve= 0
Exp/Cntr=.5,.3

Type RM Length L Ch R = 1 ,83424.1 ,835.25,879.9,933.34
BEGIN DESCRIPTION:
Cross Section 83424.1
Cross Section XS42
END DESCRIPTION:
XS GIS Cut Line= 4
      3026720.31     13947502.96      3026818.35     13945427.74
      3027002.12     13944141.32      3027687.91     13943150.95
#Sta/Elev= 28
  2711.6   165.7  3621.6   158.5  4191.6   158.3  4789.1   158.3  4898.8  157.46
  4958.7  157.71  4964.8  158.17  4968.6  157.73  4973.6  156.72  4980.9  154.64
  4988.8  152.63  4994.5   151.7  5001.2   150.9  5005.6  151.88  5011.1  152.59
  5016.4  154.51  5022.1   156.4  5033.2  158.93  5045.9  160.54  5055.7  159.88
  5108.8   159.5  5139.1   157.8  5259.1   158.2  5699.1   158.3  5864.9  158.95
  5929.1   159.2  6088.6   160.6  7293.2   166.7
#Mann= 6 ,-1 , 0
  2711.6     .15       0  3621.6     .07       0  4964.8     .06       0
  5045.9     .15       0  5864.9     .06       0  7293.2      .2       0
#Block Obstruct= 1 ,-1
 5315.21 5405.33     168
Bank Sta=4964.8,5045.9
XS Rating Curve= 0
Exp/Cntr=.3,.1

Type RM Length L Ch R = 1 ,82544.2 ,618.8,622.7,633.69
BEGIN DESCRIPTION:
Cross Section 82544.2
Cross Section XS41
END DESCRIPTION:
XS GIS Cut Line= 3
      3027399.66      13947455.2      3027824.79      13944569.5
      3027992.27      13943938.3
#Sta/Elev= 26
  2956.2   167.5  3066.2   165.6  3555.9  159.76  3586.2   159.4  4056.2   158.3
  4857.8  157.22  4882.9  157.23  4911.9  157.56  4960.1  158.44  4972.7  156.92
  4975.6  156.05  4988.7  152.26  4996.2  150.39  5002.4   150.6  5007.4  151.64
  5011.4  152.23  5023.7  156.75  5040.2  157.45    5059  157.87  5073.9  157.39
  5123.9  157.39  5146.2   156.9    5380  157.46  5396.2   157.5  5873.1   160.7
  6526.2     166
#Mann= 6 ,-1 , 0
  2956.2     .07       0  3555.9     .15       0  4960.1     .06       0
    5059     .15       0  5146.2     .05       0    5380     .06       0
#Block Obstruct= 1 ,-1
 5345.23 5545.23     168
Bank Sta=4960.1,5059
XS Rating Curve= 0
Exp/Cntr=.3,.1

Type RM Length L Ch R = 1 ,81921.5 ,664.4,587.4,540.9
BEGIN DESCRIPTION:
Cross Section 81921.5
Cross Section XS40.5
END DESCRIPTION:
XS GIS Cut Line= 3
      3027979.39      13947880.4      3028327.22      13945406.9
      3028533.35       13944080.
#Sta/Elev= 27
    2653   167.6  2969.3  165.37    3641  160.64    3803   159.5  4809.2  156.71
  4875.1  156.86  4917.7  156.11  4976.1  154.46  4989.4  152.32  4996.3  151.56
  4999.5  150.32  5002.4   150.1  5004.6  150.58  5007.6   151.5  5010.6  152.26
  5013.4  152.74  5029.4  153.24  5069.5  156.96  5126.8  157.31    5167  157.98
  5190.2  157.59  5220.4   157.8 5268.15158.1302 5404.02159.0699  5610.8   160.5
  5800.8   160.2  6493.7   163.3
#Mann= 8 ,-1 , 0
    2653     .12       0  2969.3     .07       0    3641     .15       0
  4875.1     .06       0  5069.5     .15       0  5220.4     .07       0
 5268.15     .05       0 5404.02     .07       0
#Block Obstruct= 1 ,-1
 5389.02 5589.02     168
Bank Sta=4875.1,5069.5
XS Rating Curve= 0
Exp/Cntr=.3,.1

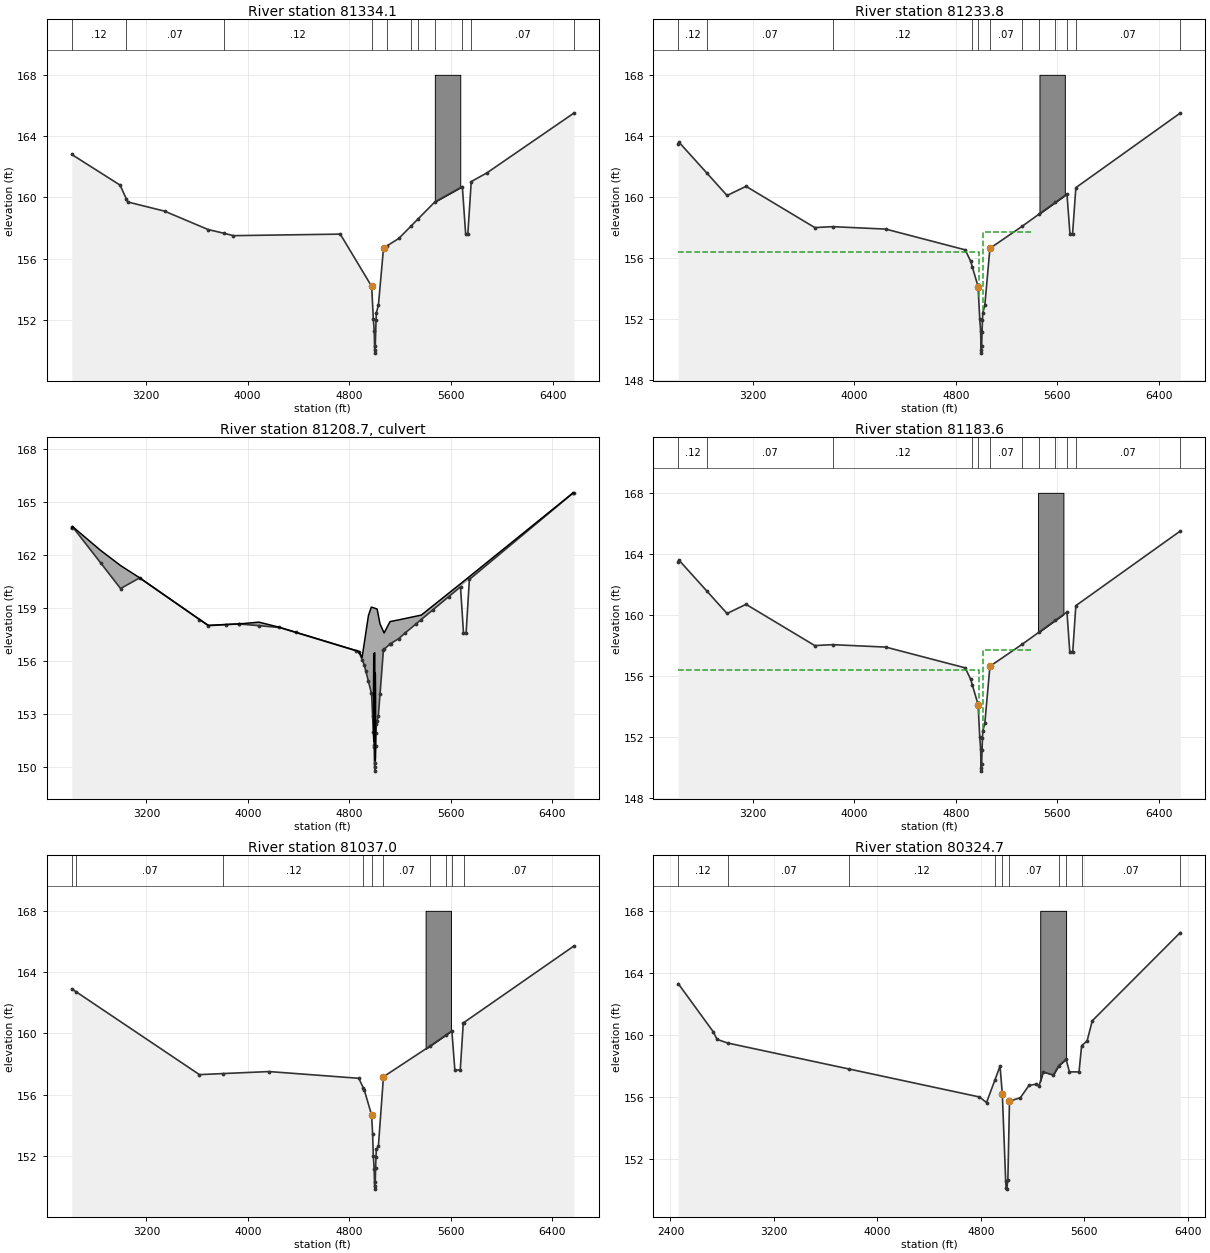
Type RM Length L Ch R = 1 ,81334.1 ,100.3,100.3,100.3
XS GIS Cut Line= 5
      3028924.83     13948089.42       3028922.1     13947017.21
      3028869.39     13945693.54       3028870.9     13945234.27
      3028901.51     13944141.23
#Sta/Elev= 30
    2617   162.8    2997   160.8  3046.1   159.9    3057   159.7    3347   159.1
  3689.2   157.9  3816.3  157.65  3889.2   157.5  4729.2   157.6  4976.1  154.19
  4989.4  152.05  4996.3  151.29  4999.5  150.05  5002.4  149.83  5004.6  150.31
  5010.6  151.99  5013.4  152.47  5029.4  152.97  5069.5  156.69  5100.2  156.85
  5190.2  157.32  5286.4  158.13 5337.65158.5607  5473.2   159.7 5689.56160.7026
 5715.64   157.6 5732.57   157.6 5759.56  161.03  5883.2   161.6  6566.7   165.5
#Mann= 11 ,-1 , 0
    2617     .12       0  3046.1     .07       0  3816.3     .12       0
  4976.1     .06       0  5100.2     .07       0  5286.4     .07       0
 5337.65     .05       0  5473.2     .07       0 5689.56     .05       0
 5759.56     .07       0  6566.7      .2       0
#Block Obstruct= 1 ,-1
 5473.19 5673.19     168
Bank Sta=4976.1,5069.5
XS Rating Curve= 0
Exp/Cntr=.5,.3

Type RM Length L Ch R = 1 ,81233.8 ,50.2,50.2,50.2
BEGIN DESCRIPTION:
Upstream Section of Bridge/Culvert/Weir
END DESCRIPTION:
XS GIS Cut Line= 5
      3029022.61      13948100.5      3029019.88      13947028.3
      3028967.17      13945704.6      3028968.68      13945245.4
      3028999.29      13944152.3
#Sta/Elev= 30
    2611   163.5  2615.9   163.6  2837.8  161.56  2995.9   160.1  3145.9   160.7
  3688.1     158  3828.7  158.06  4248.1   157.9  4875.1  156.54  4917.7  155.79
  4930.5  155.43  4976.1  154.14  4989.4     152  4996.3  151.24  4999.5     150
  5002.4  149.78  5004.6  150.26  5007.6  151.18  5010.6  151.94  5013.4  152.42
  5029.4  152.92  5069.5  156.64 5324.77158.0903 5457.16158.8813 5585.83159.6498
 5677.28 160.196 5700.74   157.6 5721.57   157.6 5747.28 160.614  6571.3   165.5
#Mann= 12 ,-1 , 0
    2611     .12       0  2837.8     .07       0  3828.7     .12       0
  4930.5     .07       0  4976.1     .06       0  5069.5     .07       0
 5324.77     .06       0 5457.16     .07       0 5585.83     .06       0
 5677.28     .05       0 5747.28     .07       0  6571.3      .2       0
#XS Ineff= 3 ,-1
                            2611    4981   156.4    5018    5400   157.7
Permanent Ineff=
       F       F       F
#Block Obstruct= 1 ,-1
 5460.26 5660.26     168
Bank Sta=4976.1,5069.5
XS Rating Curve= 0
Exp/Cntr=.5,.3

Type RM Length L Ch R = 2 ,81208.7 ,,,
BEGIN DESCRIPTION:
PASTURE BRIDGE @ M100-XS40
Structure ID: M100-00-00-15
END DESCRIPTION:
Node Name=Pasture Bridge
Bridge Culvert--1,0,-1,-1, 0
Deck Dist Width WeirC Skew NumUp NumDn MinLoCord MaxHiCord MaxSubmerge Is_Ogee
10,30.2,3,0, 44, 44, , , .95, 0, 1,1,,
    2611  2615.9  2837.8  2995.9  3145.9    3618  3688.1  3828.7    3928  3928.1
    4088  4248.1    4378  4856.3  4875.1  4901.2  4917.7  4930.5    4951  4973.7
  4976.1  4984.1  4989.4  4996.3  4996.6  4999.5  5002.4  5004.6  5007.6  5010.6
  5013.4  5019.6  5029.4  5042.6  5069.5  5074.7  5121.2  5126.8  5190.2  5242.8
  5368.2    5688  6565.5  6571.3
   163.5  163.61  162.26   161.4  160.71  158.36  158.02  158.07   158.1   158.1
   158.2  157.91  157.63  156.59  156.55  156.21  156.99   157.6  158.57  159.05
  159.04  159.03  159.02     159     159  158.99  158.98  158.98  158.97  158.96
  158.96  158.94  158.58   158.1  157.67  157.59  158.23  158.24  158.33  158.41
   158.6  160.43  165.51   165.5
   163.5   163.6  161.56   160.1   160.7  158.35     158  158.06   158.1   158.1
     158   157.9  157.62  156.58  156.54  156.08  155.79  155.43  154.85  154.21
  154.14  152.88     152  151.24  151.12     150  149.78  150.26  151.18  151.94
  152.42  152.61  152.92  154.14  156.64  156.67  156.96  156.99  157.27   157.6
  158.35  160.26   165.5   165.5
    2611  2615.9  2837.8  2995.9  3145.9    3618  3688.1  3828.7    3928  3928.1
    4088  4248.1    4378  4856.3  4875.1  4901.2  4917.7  4930.5    4951  4973.7
  4976.1  4984.1  4989.4  4996.3  4996.6  4999.5  5002.4  5004.6  5007.6  5010.6
  5013.4  5019.6  5029.4  5042.6  5069.5  5074.7  5121.2  5126.8  5190.2  5242.8
  5368.2    5688  6565.5  6571.3
   163.5  163.61  162.26   161.4  160.71  158.36  158.02  158.07   158.1   158.1
   158.2  157.91  157.63  156.59  156.55  156.21  156.99   157.6  158.57  159.05
  159.04  159.03  159.02     159     159  158.99  158.98  158.98  158.97  158.96
  158.96  158.94  158.58   158.1  157.67  157.59  158.23  158.24  158.33  158.41
   158.6  160.43  165.51   165.5
   163.5   163.6  161.56   160.1   160.7  158.35     158  158.06   158.1   158.1
     158   157.9  157.62  156.58  156.54  156.08  155.79  155.43  154.85  154.21
  154.14  152.88     152  151.24  151.12     150  149.78  150.26  151.18  151.94
  152.42  152.61  152.92  154.14  156.64  156.67  156.96  156.99  157.27   157.6
  158.35  160.26   165.5   165.5
BR Coef= 1 , 0 , 0 ,1.25, 0 ,,,.8,-1,2,1,
WSPro=,,,, 1 ,,,, 0 ,,,, 0 ,,,,-1 ,-1 ,-1 , 0 , 0 , 0 , 0 , 0
Culvert=1,5,,30.2,.024,.9,1,2,3,151.44,4993.5,149.97,4993.5,Culvert #1  , 0 ,10
Culvert Bottom n=.024
Culvert=1,5,,30.2,.024,.9,1,2,3,151.5,4999.6,149.78,4999.6,Culvert #2  , 0 ,10
Culvert Bottom n=.024
Culvert=1,5,,30.2,.024,.9,1,2,3,150.36,5005.4,150.36,5005.4,Culvert #3  , 0 ,10
Culvert Bottom n=.024
BR U #Sta/Elev= 50
    2611   163.5  2615.9   163.6  2837.8  161.56  2995.9   160.1  3145.9   160.7
    3618  158.35  3688.1     158  3828.7  158.06    3928   158.1  3928.1   158.1
    4088     158  4248.1   157.9    4378  157.62  4856.3  156.58  4875.1  156.54
  4901.2  156.08  4917.7  155.79  4930.5  155.43    4951  154.85  4973.7  154.21
  4976.1  154.14  4984.1  152.88  4989.4     152  4996.3  151.24  4996.6  151.12
  4999.5     150  5002.4  149.78  5004.6  150.26  5007.6  151.18  5010.6  151.94
  5013.4  152.42  5019.6  152.61  5029.4  152.92  5042.6  154.14  5069.5  156.64
  5074.7  156.67  5121.2  156.96  5126.8  156.99  5190.2  157.27  5242.8   157.6
 5324.77158.0903  5368.2  158.35 5457.16158.8813 5585.83159.6498 5677.28 160.196
 5700.74   157.6 5721.57   157.6 5747.28 160.614  6565.5   165.5  6571.3   165.5
BR U #Mann= 12
    2611     .12  2837.8     .07  3828.7     .12  4930.5     .07  4976.1     .06
  5069.5     .07 5324.77     .06 5457.16     .07 5585.83     .06 5677.28     .05
 5747.28     .07  6571.3      .2
BR D #Sta/Elev= 50
    2611   163.5  2615.9   163.6  2837.8  161.56  2995.9   160.1  3145.9   160.7
    3618  158.35  3688.1     158  3828.7  158.06    3928   158.1  3928.1   158.1
    4088     158  4248.1   157.9    4378  157.62  4856.3  156.58  4875.1  156.54
  4901.2  156.08  4917.7  155.79  4930.5  155.43    4951  154.85  4973.7  154.21
  4976.1  154.14  4984.1  152.88  4989.4     152  4996.3  151.24  4996.6  151.12
  4999.5     150  5002.4  149.78  5004.6  150.26  5007.6  151.18  5010.6  151.94
  5013.4  152.42  5019.6  152.61  5029.4  152.92  5042.6  154.14  5069.5  156.64
  5074.7  156.67  5121.2  156.96  5126.8  156.99  5190.2  157.27  5242.8   157.6
 5324.77158.0903  5368.2  158.35 5457.16158.8813 5585.83159.6498 5677.28 160.196
 5699.28   157.6    5723   157.6 5747.28 160.614  6565.5   165.5  6571.3   165.5
BR D #Mann= 12
    2611     .12  2837.8     .07  3828.7     .12  4930.5     .07  4976.1     .06
  5069.5     .07 5324.77     .06 5457.16     .07 5585.83     .06 5677.28     .05
 5747.28     .07  6571.3      .2
BC Design=,, 0 ,, 0 ,,,,,,
BC HTab HWMax=165.5

Type RM Length L Ch R = 1 ,81183.6 ,146.6,146.6,146.6
BEGIN DESCRIPTION:
Downstream Section of Bridge/Culvert/Weir
END DESCRIPTION:
XS GIS Cut Line= 5
      3029090.74      13948097.4      3029074.29      13947090.5
      3029017.83      13945701.5      3029020.39      13945241.5
      3029039.25      13944138.5
#Sta/Elev= 30
    2611   163.5  2615.9   163.6  2837.8  161.56  2995.9   160.1  3145.9   160.7
  3688.1     158  3828.7  158.06  4248.1   157.9  4875.1  156.54  4917.7  155.79
  4930.5  155.43  4976.1  154.14  4989.4     152  4996.3  151.24  4999.5     150
  5002.4  149.78  5004.6  150.26  5007.6  151.18  5010.6  151.94  5013.4  152.42
  5029.4  152.92  5069.5  156.64 5324.77158.0903 5457.16158.8813 5585.83159.6498
 5677.28 160.196 5699.28   157.6    5723   157.6 5747.28 160.614  6571.3   165.5
#Mann= 12 ,-1 , 0
    2611     .12       0  2837.8     .07       0  3828.7     .12       0
  4930.5     .07       0  4976.1     .06       0  5069.5     .07       0
 5324.77     .06       0 5457.16     .07       0 5585.83     .06       0
 5677.28     .05       0 5747.28     .07       0  6571.3      .2       0
#XS Ineff= 2 ,-1
    2611    4981   156.4    5018    5400   157.7
Permanent Ineff=
       F       F
#Block Obstruct= 1 ,-1
  5449.2  5649.2     168
Bank Sta=4976.1,5069.5
XS Rating Curve= 0
Exp/Cntr=.5,.3

Type RM Length L Ch R = 1 ,81037.0 ,564.4,712.3,748.2
XS GIS Cut Line= 5
      3029234.89     13948072.15      3029218.43     13947065.25
      3029161.98     13945676.27      3029164.53      13945216.3
      3029183.39     13944113.25
#Sta/Elev= 28
  2610.9   162.9  2647.2   162.7  3617.9   157.3  3806.5  157.37  4167.9   157.5
  4875.1  157.06  4911.8  156.41  4917.7  156.31  4976.1  154.66  4984.1   153.4
  4989.4     152  4996.3  151.12  4999.5     150  5002.4  149.82  5004.6  150.26
  5007.6  151.18  5010.6  151.94  5013.4  152.42  5029.4  152.61  5069.5  157.16
 5432.83159.1424  5561.3159.8821 5609.08160.1599 5632.73   157.6 5675.36   157.6
 5699.08160.6793 5703.42160.7003  6571.3   165.7
#Mann= 10 ,-1 , 0
  2610.9     .12       0  2647.2     .07       0  3806.5     .12       0
  4911.8     .07       0  4976.1     .06       0  5069.5     .07       0
 5432.83     .07       0  5561.3     .06       0 5609.08     .05       0
 5703.42     .07       0
#Block Obstruct= 1 ,-1
 5401.95 5601.95     168
Bank Sta=4976.1,5069.5
XS Rating Curve= 0
Exp/Cntr=.3,.1

Type RM Length L Ch R = 1 ,80324.7 ,851.97,1120.2,1099.73
BEGIN DESCRIPTION:
Cross Section 80324.7
Cross Section XS39.5
END DESCRIPTION:
XS GIS Cut Line= 3
      3029383.61      13948150.9      3029950.45      13945265.2
      3030088.57      13944334.7
#Sta/Elev= 29
  2460.1   163.3  2730.1   160.2  2760.1   159.7    2844  159.46  3778.5  157.79
    4789  155.98  4843.4  155.62  4907.1  157.05  4947.8  157.97  4965.5   156.2
  4991.6  150.56    4995   150.1  4999.8  150.03  5008.5  150.64    5021  155.71
  5104.8  155.93  5171.9  156.73  5229.3  156.81  5250.1   156.7  5280.1   157.6
  5360.1   157.4    5401     158 5458.58  158.41 5484.63   157.6 5558.63   157.6
 5578.58  159.29    5621   159.6    5661   160.9  6341.6   166.6
#Mann= 10 ,-1 , 0
  2460.1     .12       0    2844     .07       0  3778.5     .12       0
  4907.1     .07       0  4965.5     .06       0    5021     .07       0
    5401     .07       0 5458.58     .05       0 5578.58     .07       0
  6341.6      .2       0
#Block Obstruct= 1 ,-1
 5258.58 5458.58     168
Bank Sta=4965.5,5021
XS Rating Curve= 0
Exp/Cntr=.3,.1

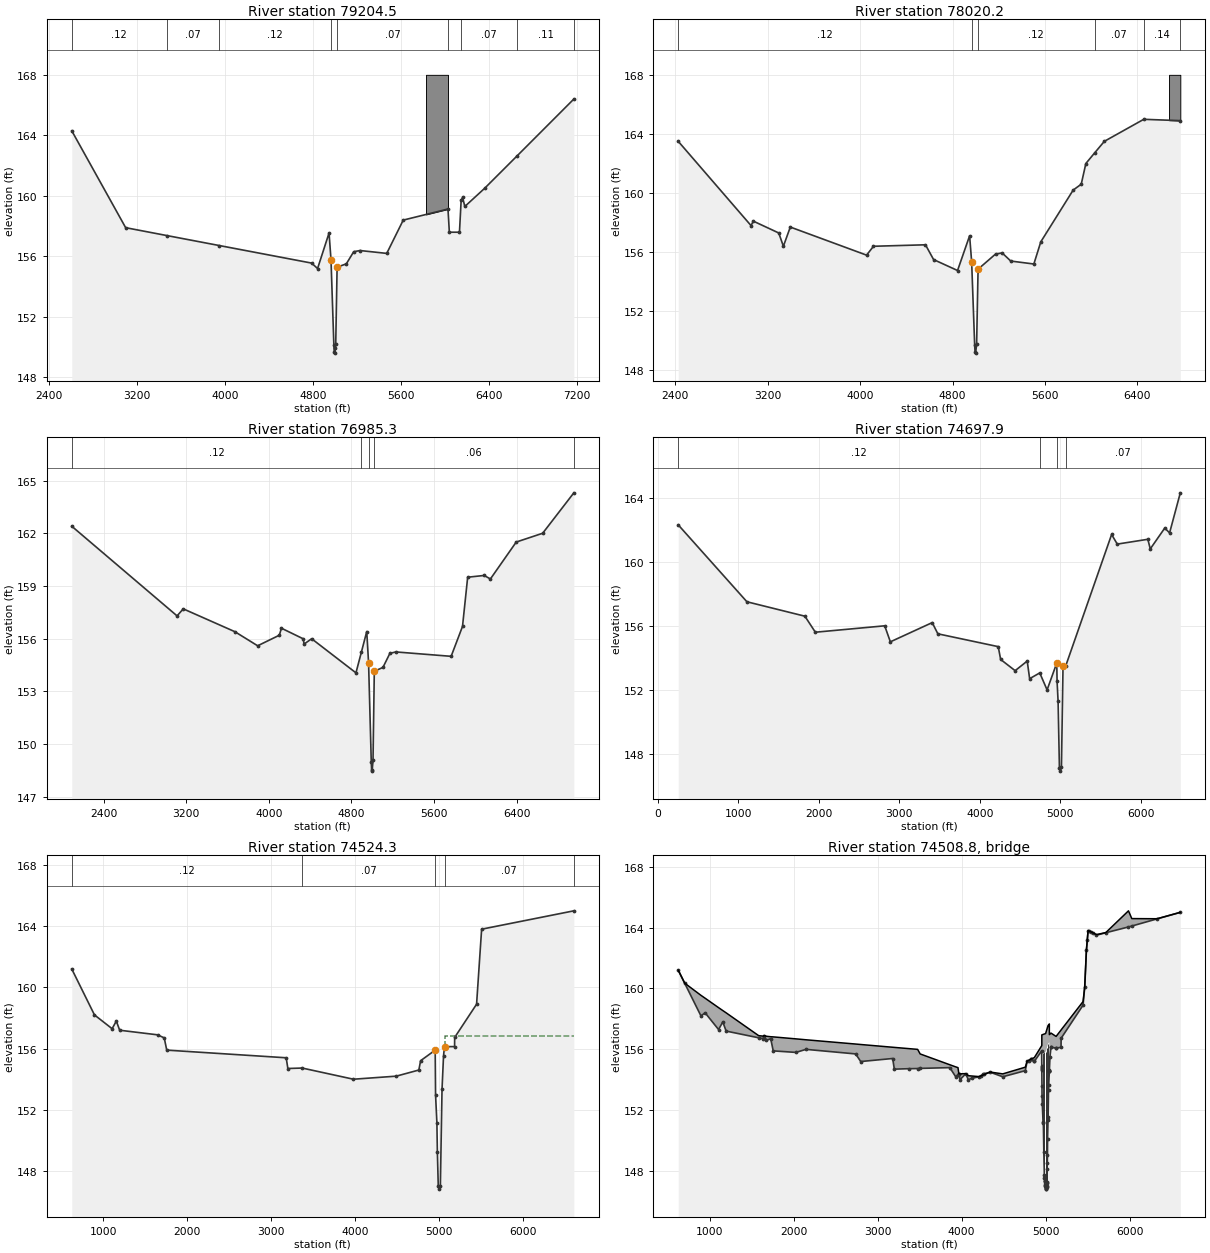
Type RM Length L Ch R = 1 ,79204.5 ,903.01,1184.3,1292.09
BEGIN DESCRIPTION:
Cross Section 79204.5
Cross Section XS38.5
END DESCRIPTION:
XS GIS Cut Line= 4
      3029390.77     13948223.09      3030605.32     13946359.18
      3030824.17     13946140.32      3031562.05      13944247.7
#Sta/Elev= 28
  2608.2   164.3  3098.2   157.9  3472.2  157.38  3949.3  156.72    4789  155.56
  4843.4   155.2  4947.8  157.55  4965.5  155.78  4991.6  150.14    4995  149.68
  4999.8  149.61    5005  149.93  5008.5  150.22    5021  155.29  5104.8  155.51
  5171.9  156.31  5229.3  156.39  5472.4   156.2  5622.4   158.4 6029.41159.1317
 6041.62   157.6 6133.69   157.6    6149159.6983  6162.4   159.9  6182.4   159.3
  6362.4   160.5  6658.6  162.65  7173.8   166.4
#Mann= 9 ,-1 , 0
  2608.2     .12       0  3472.2     .07       0  3949.3     .12       0
  4965.5     .06       0    5021     .07       0 6029.41     .05       0
    6149     .07       0  6658.6     .11       0  7173.8      .2       0
#Block Obstruct= 1 ,-1
 5829.41 6029.41     168
Bank Sta=4965.5,5021
XS Rating Curve= 0
Exp/Cntr=.3,.1

Type RM Length L Ch R = 1 ,78020.2 ,1045,1034.9,1025
BEGIN DESCRIPTION:
Cross Section 78020.2
Cross Section XS38
END DESCRIPTION:
XS GIS Cut Line= 4
      3029443.87     13948205.39      3031402.99      13947182.3
      3031889.56     13946724.92      3032689.76     13945494.76
#Sta/Elev= 30
  2425.9   163.5  3055.9   157.8  3075.9   158.1  3295.9   157.3  3335.9   156.4
  3395.9   157.7  4055.9   155.8  4115.9   156.4  4565.9   156.5  4636.1   155.5
  4843.4  154.76  4947.8  157.11  4965.5  155.34  4991.6   149.7    4995  149.24
  4999.8  149.17  5008.5  149.78    5021  154.85  5171.9  155.87  5229.3  155.95
  5303.9   155.4  5503.9   155.2  5563.9   156.7  5843.9   160.2  5913.9   160.6
  5953.9     162  6029.1  162.71  6113.9   163.5  6454.9  164.99  6771.4   164.9
#Mann= 6 ,-1 , 0
  2425.9     .12       0  4965.5     .06       0    5021     .12       0
  6029.1     .07       0  6454.9     .14       0  6771.4      .2       0
#Block Obstruct= 1 ,-1
 6673.99  6771.4     168
Bank Sta=4965.5,5021
XS Rating Curve= 0
Exp/Cntr=.3,.1

Type RM Length L Ch R = 1 ,76985.3 ,66.3,2287.4,2064.4
BEGIN DESCRIPTION:
Cross Section 76985.3
Cross Section XS36.5
END DESCRIPTION:
XS GIS Cut Line= 5
      3029597.96     13948165.65      3030127.18     13948165.76
      3031919.49     13948207.02      3033289.52     13946529.44
      3033523.68     13946240.71
#Sta/Elev= 30
  2092.7   162.4  3111.9   157.3  3171.9   157.7  3671.9   156.4  3891.9   155.6
  4101.9   156.2  4121.9   156.6  4331.9     156  4341.9   155.7  4414.7     156
  4843.4  154.06  4896.9  155.26  4947.8  156.41  4965.5  154.64  4991.6     149
    4995  148.54  4999.8  148.47  5008.5  149.08    5021  154.15  5104.8  154.37
  5171.9  155.17  5229.3  155.25  5764.7     155  5874.7   156.7  5924.7   159.5
  6084.7   159.6  6144.7   159.4  6394.7   161.5  6650.6     162  6952.4   164.3
#Mann= 5 ,-1 , 0
  2092.7     .12       0  4896.9     .06       0  4965.5     .06       0
    5021     .06       0  6952.4      .2       0
Bank Sta=4965.5,5021
XS Rating Curve= 0
Exp/Cntr=.3,.1

Type RM Length L Ch R = 1 ,74697.9 ,58.7,173.6,173.7
XS GIS Cut Line= 6
      3029664.55     13948188.95      3030067.46     13948200.76
      3032228.05     13948264.68      3034134.64     13948462.26
      3034324.81     13948484.52      3035071.76     13947111.27
#Sta/Elev= 30
   253.6   162.3  1106.7   157.5  1826.7   156.6  1956.7   155.6  2818.2     156
  2888.2     155  3408.2   156.2  3478.2   155.5  4228.2   154.7  4258.2   153.9
  4438.2   153.2  4588.2   153.8  4618.2   152.7  4743.8  153.06    4835     152
 4955.22  153.68 4959.12  152.54 4971.72  151.28 4988.22  147.11 4998.62  146.93
 5013.12  147.16 5032.92  153.47  5066.5   153.5  5636.5   161.7  5706.5   161.1
  6086.5   161.4  6116.5   160.8  6296.5   162.1  6356.5   161.8  6489.7   164.3
#Mann= 4 ,-1 , 0
   253.6     .12       0  4743.8     .07       0 4955.22     .06       0
  5066.5     .07       0
Bank Sta=4955.22,5032.92
XS Rating Curve= 0
Exp/Cntr=.5,.3

Type RM Length L Ch R = 1 ,74524.3 ,23.3,23.3,23.3
BEGIN DESCRIPTION:
Upstream Section of Bridge/Culvert/Weir
Bridge deck wide to account for pipe
END DESCRIPTION:
XS GIS Cut Line= 5
        3030147.      13948228.5      3032256.52      13948301.4
      3034266.63      13948494.4      3034491.05      13948507.4
      3035219.59      13947169.8
#Sta/Elev= 30
     628   161.2     898   158.2    1108   157.3    1158   157.8    1198   157.2
    1648   156.9    1728   156.7    1758   155.9  3178.8   155.4  3198.8   154.7
  3368.9  154.73  3978.8     154  4488.8   154.2  4756.9   154.6  4778.3  155.21
  4951.5   155.9    4956  152.96  4971.7  151.17  4977.3  149.27  4988.2     147
  4998.6  146.82  5013.1  147.05  5032.9  153.36  5050.8  155.53  5062.3  156.13
  5182.2  156.13  5183.3  156.73  5443.9   158.9  5503.9   163.8    6601     165
#Mann= 5 ,-1 , 0
     628     .12       0  3368.9     .07       0  4951.5     .06       0
  5062.3     .07       0    6601      .2       0
#XS Ineff= 2 , 0
       0  4941.5  154.21  5072.3       0  156.85
Permanent Ineff=
       F       F
Bank Sta=4951.5,5062.3
XS Rating Curve= 0
Exp/Cntr=.5,.3

Type RM Length L Ch R = 3 ,74508.8 ,,,
BEGIN DESCRIPTION:
FOOT BRIDGE
Structure ID: M100-00-00-14
END DESCRIPTION:
Node Name=Foot Bridge
Bridge Culvert--1,0,-1,-1, 0
Deck Dist Width WeirC Skew NumUp NumDn MinLoCord MaxHiCord MaxSubmerge Is_Ogee
9,12,2.6,0, 60, 60, , , .95, 0, 1,1,,
     628   705.1     898     948    1108    1158    1198  1585.1    1638    1648
    1678    1728    1758    2028    2148  2738.8  2798.8  3178.8  3198.8  3476.1
  3506.1  3858.8  3928.8  3956.1  3966.1  3968.8  3978.8  4048.8  4078.8  4208.8
  4338.8  4488.8  4756.9  4778.3  4820.7  4864.4  4953.2 4953.31  4953.4  4953.5
  4998.6  5027.3  5042.9 5042.99  5043.1  5050.8  5062.3  5123.3  5182.2  5183.3
  5443.9  5463.9  5483.9  5503.9  5603.9  5714.4  5984.4  6023.9  6324.4    6601
   161.2  160.35  159.55  159.36  158.74  158.55   158.4   156.9  156.87  156.91
  156.86  156.83  156.82  156.69  156.63  156.35  156.32  156.14  156.13     156
   155.7  154.99  154.85   154.8   154.4   154.4  154.39  154.41  154.27  154.21
  154.51  154.39  154.83  155.22  155.35  155.46  156.25  156.25  156.25  156.95
  157.04  157.56  157.67  156.97  156.97  157.01  157.07  156.85  157.27  157.28
  159.14  160.11  162.51  163.81  163.54  163.67   165.1  164.59  164.58     165
   161.2  160.34   158.2   158.4   157.3   157.8   157.2  156.76   156.7   156.9
   156.6   156.7   155.9   155.8     156   155.7   155.2   155.4   154.7  154.74
  154.75   154.8   154.2  154.34  154.39   154.4     154   154.4     154   154.2
   154.5   154.2   154.6  155.21  155.34  155.21  154.83  154.76  155.75  155.75
  155.84  156.36  156.47  156.47   154.6  155.53  156.13  156.09  156.13  156.73
   158.9   160.1   162.5   163.8   163.5  163.66  164.04   164.1  164.57     165
     628   705.1     898     948    1108    1158    1198  1585.1    1638    1648
    1678    1728    1758    2028    2148  2738.8  2798.8  3178.8  3198.8  3476.1
  3506.1  3858.8  3928.8  3956.1  3966.1  3968.8  3978.8  4048.8  4078.8  4208.8
  4338.8  4488.8  4756.9  4778.3  4820.7  4864.4  4953.2 4953.31  4953.4  4953.5
  4998.6  5027.3  5042.9 5042.99  5043.1  5050.8  5062.3  5123.3  5182.2  5183.3
  5443.9  5463.9  5483.9  5503.9  5603.9  5714.4  5984.4  6023.9  6324.4    6601
   161.2  160.35  159.55  159.36  158.74  158.55   158.4   156.9  156.87  156.91
  156.86  156.83  156.82  156.69  156.63  156.35  156.32  156.14  156.13     156
   155.7  154.99  154.85   154.8   154.4   154.4  154.39  154.41  154.27  154.21
  154.51  154.39  154.83  155.22  155.35  155.46  156.25  156.25  156.25  156.95
  157.04  157.56  157.67  156.97  156.97  157.01  157.07  156.85  157.27  157.28
  159.14  160.11  162.51  163.81  163.54  163.67   165.1  164.59  164.58     165
   161.2  160.34   158.2   158.4   157.3   157.8   157.2  156.76   156.7   156.9
   156.6   156.7   155.9   155.8     156   155.7   155.2   155.4   154.7  154.74
  154.75   154.8   154.2  154.34  154.39   154.4     154   154.4     154   154.2
   154.5   154.2   154.6  155.21  155.34  155.21  154.83  154.76  155.75  155.75
  155.84  156.36  156.47  156.47   154.6  155.53  156.13  156.09  156.13  156.73
   158.9   160.1   162.5   163.8   163.5  163.66  164.04   164.1  164.57     165
Pier Skew, UpSta & Num, DnSta & Num=  ,4968.2, 2 ,4968.2, 2 , 0 , 0 , 0 ,,
     1.5     1.5
  150.21  156.78
     1.5     1.5
  150.21  155.82
Pier Skew, UpSta & Num, DnSta & Num=  ,4983.7, 2 ,4983.7, 2 , 0 , 0 , 0 ,,
     1.5     1.5
  146.61  156.81
     1.5     1.5
  146.61  155.85
Pier Skew, UpSta & Num, DnSta & Num=  ,4998.6, 2 ,4998.6, 2 , 0 , 0 , 0 ,,
       1       1
  145.86  156.85
       1       1
  145.86  155.89
Pier Skew, UpSta & Num, DnSta & Num=  ,5013.1, 2 ,5013.1, 2 , 0 , 0 , 0 ,,
       1       1
  146.02  157.11
       1       1
  146.02  156.15
Pier Skew, UpSta & Num, DnSta & Num=  ,5028.4, 2 ,5028.4, 2 , 0 , 0 , 0 ,,
     1.5     1.5
  150.43  157.36
     1.5     1.5
  150.43   156.4
Abutment Skew #Up #Dn= , 2 , 2
  4953.2  4986.3
  155.75  147.37
  4953.2  4986.3
  154.79  146.41
Abutment Skew #Up #Dn= , 2 , 2
  5013.6 5043.19
   147.3  156.47
  5013.6 5043.19
  146.34  155.51
BR Coef= 1 , 1 , 1 ,1.25, 0 ,,,.8,0,2,0,
WSPro=,,,, 1 ,,,, 0 ,,,, 0 ,,,,-1 ,-1 ,-1 , 0 , 0 , 0 , 0 , 0
BR U #Sta/Elev= 103
     628   161.2   705.1  160.34     898   158.2     948   158.4    1108   157.3
    1158   157.8    1198   157.2  1585.1  156.76    1638   156.7    1648   156.9
    1678   156.6    1728   156.7    1758   155.9    2028   155.8    2148     156
  2738.8   155.7  2798.8   155.2  3178.8   155.4  3198.8   154.7  3368.9  154.73
  3476.1  154.74  3506.1  154.75  3858.8   154.8  3928.8   154.2  3956.1  154.34
  3966.1  154.39  3968.8   154.4  3978.8     154  4048.8   154.4  4078.8     154
  4118.8   154.1  4208.8   154.2  4226.1  154.26  4256.1  154.36  4268.8   154.4
  4338.8   154.5  4488.8   154.2  4756.9   154.6  4778.3  155.21  4796.1  155.26
  4820.7  155.34    4821  155.34  4864.1  155.21  4864.4  155.21  4951.5   155.9
  4953.1  154.89  4953.2  154.83 4953.31  154.76  4953.4   154.7  4953.5  154.64
  4955.2  153.57    4956  152.96  4959.1  152.43  4968.1  151.22  4971.7  151.17
  4977.3  149.27  4983.7  147.72  4984.9  147.55  4986.2  147.38  4986.3  147.37
  4988.2     147  4994.2  147.12  4998.5  146.83  4998.6  146.82    4999  146.89
    5011  146.94  5013.1  147.05  5013.5  147.25  5013.6   147.3  5015.4  148.13
  5018.2  148.52  5020.5  149.05  5021.8  150.12  5027.3  151.35  5028.4  151.59
  5032.9  153.36  5035.1  153.63  5042.9  154.57 5042.99  154.58  5043.1   154.6
  5043.2  154.61  5043.3  154.62  5050.8  155.53  5062.3  156.13  5062.9  156.13
  5123.1  156.09  5123.3  156.09  5182.2  156.13  5183.3  156.73  5443.9   158.9
  5463.9   160.1  5483.9   162.5  5494.4  163.18  5503.9   163.8  5514.4  163.77
  5534.4  163.71  5564.4  163.62  5603.9   163.5  5714.4  163.66  5984.4  164.04
  6023.9   164.1  6324.4  164.57    6601     165
BR U #Mann= 4
     628     .12  3368.9     .07  4951.5     .05  5062.3     .07
BR D #Sta/Elev= 103
     628   161.2   705.1  160.34     898   158.2     948   158.4    1108   157.3
    1158   157.8    1198   157.2  1585.1  156.76    1638   156.7    1648   156.9
    1678   156.6    1728   156.7    1758   155.9    2028   155.8    2148     156
  2738.8   155.7  2798.8   155.2  3178.8   155.4  3198.8   154.7  3368.9  154.73
  3476.1  154.74  3506.1  154.75  3858.8   154.8  3928.8   154.2  3956.1  154.34
  3966.1  154.39  3968.8   154.4  3978.8     154  4048.8   154.4  4078.8     154
  4118.8   154.1  4208.8   154.2  4226.1  154.26  4256.1  154.36  4268.8   154.4
  4338.8   154.5  4488.8   154.2  4756.9   154.6  4778.3  155.21  4796.1  155.26
  4820.7  155.34    4821  155.34  4864.1  155.21  4864.4  155.21  4951.5   155.9
  4953.1  154.89  4953.2  154.83 4953.31  154.76  4953.4   154.7  4953.5  154.64
  4955.2  153.57    4956  152.96  4959.1  152.43  4968.1  151.22  4971.7  151.17
  4977.3  149.27  4983.7  147.72  4984.9  147.55  4986.2  147.38  4986.3  147.37
  4988.2     147  4994.2  147.12  4998.5  146.83  4998.6  145.86    4999  146.89
    5011  146.94  5013.1  147.05  5013.5  147.25  5013.6   147.3  5015.4  148.13
  5018.2  148.52  5020.5  149.05  5021.8  150.12  5027.3  151.35  5028.4  151.59
  5032.9  153.36  5035.1  153.63  5042.9  154.57 5042.99  154.58  5043.1   154.6
  5043.2  154.61  5043.3  154.62  5050.8  155.53  5062.3  156.13  5062.9  156.13
  5123.1  156.09  5123.3  156.09  5182.2  156.13  5183.3  156.73  5443.9   158.9
  5463.9   160.1  5483.9   162.5  5494.4  163.18  5503.9   163.8  5514.4  163.77
  5534.4  163.71  5564.4  163.62  5603.9   163.5  5714.4  163.66  5984.4  164.04
  6023.9   164.1  6324.4  164.57    6601     165
BR D #Mann= 4
     628     .12  3368.9     .07  4951.5     .05  5062.3     .07
BC Design=,, 0 ,, 0 ,,,,,,
BC HTab HWMax=165

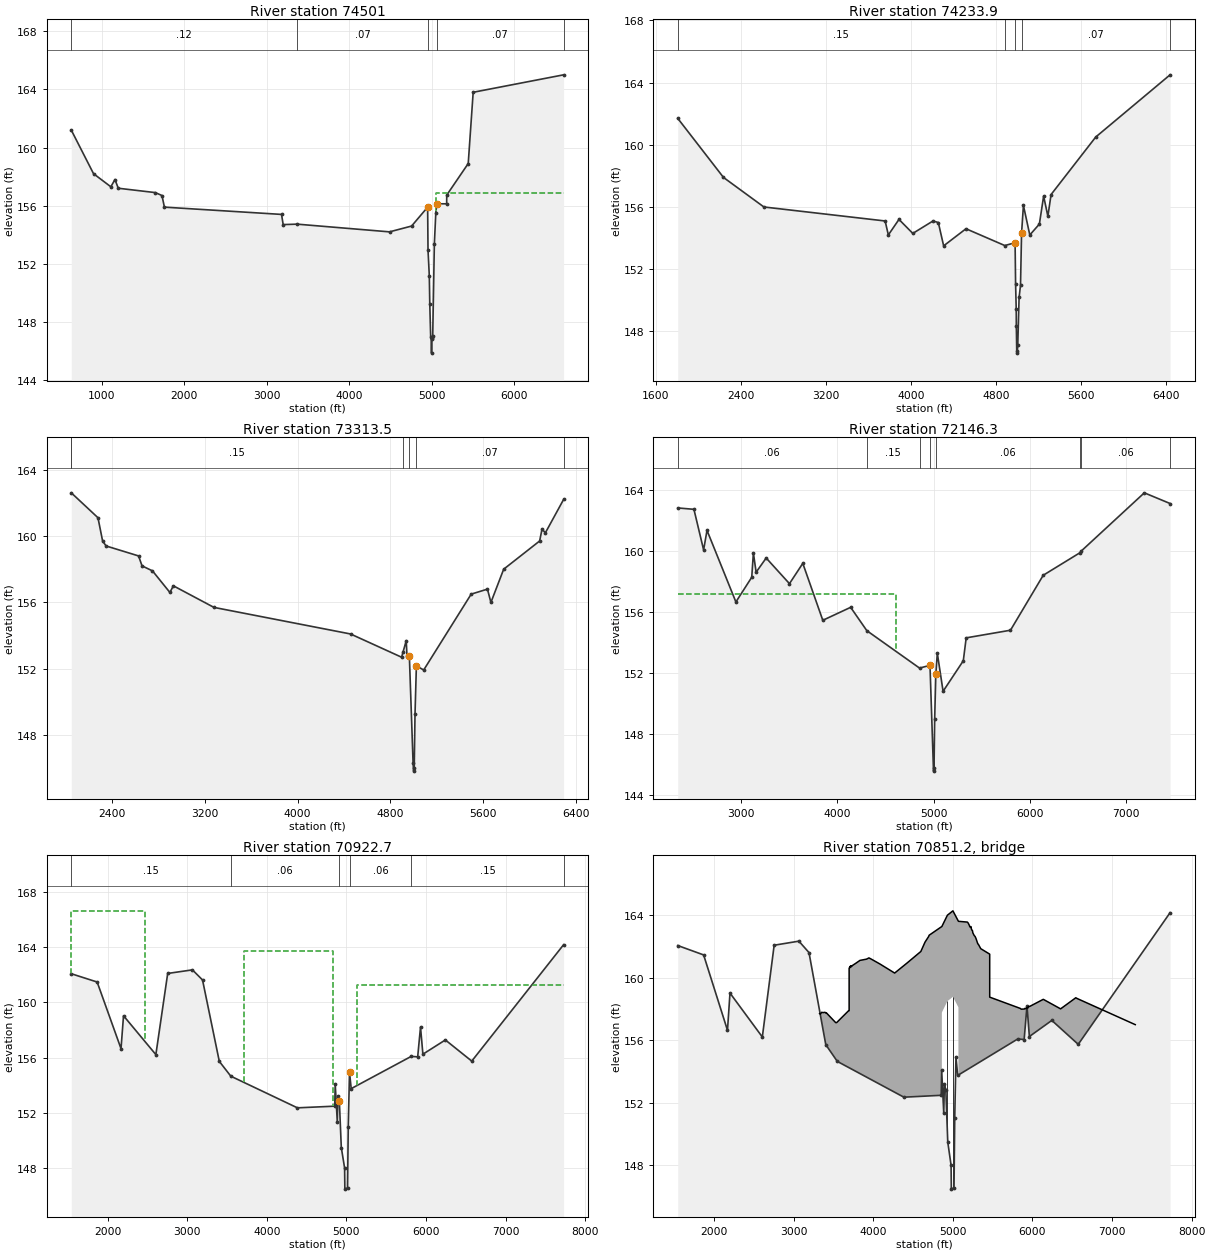
Type RM Length L Ch R = 1 ,74501   ,2311.9,267.1,294
BEGIN DESCRIPTION:
Downstream Section of Bridge/Culvert/Weir
END DESCRIPTION:
XS GIS Cut Line= 6
      3030208.81      13948296.4      3032208.11      13948400.4
      3032954.85      13948439.5      3034198.63      13948518.6
      3034513.39      13948529.6      3035305.35      13947154.8
#Sta/Elev= 30
     628   161.2     898   158.2    1108   157.3    1158   157.8    1198   157.2
    1648   156.9    1728   156.7    1758   155.9  3178.8   155.4  3198.8   154.7
  3368.9  154.73  4488.8   154.2  4756.9   154.6  4951.5   155.9    4956  152.96
  4971.7  151.17  4977.3  149.27  4988.2     147  4998.5  146.83  4998.6  145.86
    4999  146.89  5013.1  147.05  5032.9  153.36  5050.8  155.53  5062.3  156.13
  5182.2  156.13  5183.3  156.73  5443.9   158.9  5503.9   163.8    6601     165
#Mann= 5 ,-1 , 0
     628     .12       0  3368.9     .07       0  4951.5     .06       0
  5062.3     .07       0    6601      .2       0
#XS Ineff= 2 , 0
       0    4943  155.28    5053       0  156.85
Permanent Ineff=
       F       F
Bank Sta=4951.5,5062.3
XS Rating Curve= 0
Exp/Cntr=.5,.3

Type RM Length L Ch R = 1 ,74233.9 ,1138.5,920.4,783.6
BEGIN DESCRIPTION:
Cross Section XS36a
END DESCRIPTION:
XS GIS Cut Line= 3
      3033935.46     13951680.79      3033935.46     13949730.96
       3035528.9      13947577.8
#Sta/Elev= 30
  1807.8   161.7  2237.8   157.9  2617.8     156  3757.6   155.1  3787.6   154.2
  3887.6   155.2  4017.6   154.3  4207.6   155.1  4257.6     155  4307.6   153.5
  4517.6   154.6  4882.3  153.52  4979.3   153.7    4984  151.07  4989.9  149.43
  4990.9  148.35  4994.8  146.75  4998.7   146.6  5004.4   147.1  5016.9  150.18
  5030.2  150.96  5040.1   154.3  5057.6   156.1  5117.6   154.2  5207.6   154.9
  5247.6   156.7  5287.6   155.4  5317.6   156.8  5737.6   160.5  6436.3   164.5
#Mann= 5 ,-1 , 0
  1807.8     .15       0  4882.3     .07       0  4979.3     .06       0
  5040.1     .07       0  6436.3      .2       0
Bank Sta=4979.3,5040.1
XS Rating Curve= 0
Exp/Cntr=.3,.1

Type RM Length L Ch R = 1 ,73313.5 ,966.62,1167.2,969.38
BEGIN DESCRIPTION:
Cross Section 73313.5
Cross Section XS36
Cross Section M100-00-00-X36
Located At: US FM 249
END DESCRIPTION:
XS GIS Cut Line= 3
      3034755.95      13952087.4      3035138.14      13949710.7
       3035842.8      13948014.8
#Sta/Elev= 30
  2049.9   162.6  2279.9   161.1  2319.9   159.7  2349.9   159.4  2629.9   158.8
  2659.9   158.2  2749.9   157.9  2899.9   156.6  2929.9     157  3279.9   155.7
  4457.2   154.1  4897.2   152.7  4909.6  153.01  4937.2   153.7  4943.5  152.77
  4964.1  152.77  4996.2  146.34  5000.7  145.84  5006.1  146.03  5012.9  149.28
  5024.7  152.18  5087.7  151.93  5497.2   156.5  5637.2   156.8  5667.2     156
  5777.2     158  6087.2   159.7  6107.2   160.4  6137.2   160.2  6293.7   162.2
#Mann= 6 , 1 , 0
  2049.9      .2       0  2049.9     .15       0  4909.6     .07       0
  4964.1     .06       0  5024.7     .07       0  6293.7      .2       0
Bank Sta=4964.1,5024.7
XS Rating Curve= 0
Exp/Cntr=.3,.1

Type RM Length L Ch R = 1 ,72146.3 ,1041.59,1223.6,968.58
BEGIN DESCRIPTION:
Cross Section 72146.3
Cross Section XS35.5
END DESCRIPTION:
XS GIS Cut Line= 3
  3035055.61892913952214.4643445 3035812.500393313950806.1428646
 3037010.2000008       13947481.
#Sta/Elev= 30
  2343.7  162.81 2511.77  162.72  2612.3  160.06 2647.62  161.34 2947.62  156.65
 3112.24  158.27 3129.25  159.86 3157.65   158.6 3262.18  159.53 3503.91  157.85
 3642.46  159.18 3850.16  155.45  4139.4   156.3  4307.6  154.77  4854.9  152.32
  4963.4   152.5    5000  145.57  5005.4  145.76  5012.2  149.01    5024  151.91
  5039.4   153.3  5099.4   150.8  5309.4   152.8  5339.4   154.3  5799.4   154.8
  6139.4   158.4  6524.6  159.89  6531.7  159.97  7189.4   163.8  7456.8   163.1
#Mann= 8 ,-1 , 0
  2343.7     .06       0  4307.6     .15       0  4854.9     .06       0
  4963.4     .06       0    5024     .06       0  6524.6     .14       0
  6531.7     .06       0  7456.8      .2       0
#XS Ineff= 2 , 0
  2343.7  4608.7   157.2          2343.7
Permanent Ineff=
       F       F
Bank Sta=4963.4,5024
XS Rating Curve= 0
Exp/Cntr=.3,.1

Type RM Length L Ch R = 1 ,70922.7 ,112,112,112
XS GIS Cut Line= 6
  3035154.35838113952265.0185526 3035647.888719513951419.8109072
 3036659.563999313950487.4035491 3037437.819278313949005.0822093
 3038210.580109513947814.9530504 3038475.957055213947099.2196888
#Sta/Elev= 30
    1545  162.06  1869.9  161.46 2169.67  156.64 2201.16  159.02 2607.45  156.21
    2756  162.08 3066.46  162.34 3193.52  161.61  3404.3  155.72 3548.71  154.65
 4385.23  152.36 4854.14  152.48 4860.01  154.08 4886.29  151.34 4893.51   153.2
  4912.1  152.83 4936.59  149.49  4978.1  148.01 4981.29  146.48 5015.05  146.57
  5023.9     151 5039.62  154.94 5060.88  153.75 5814.42  156.08    5896  156.05
 5931.52   158.2 5961.48  156.24  6243.6  157.27 6575.17  155.74 7728.77  164.16
#Mann= 6 ,-1 , 0
    1545     .15       0 3548.71     .06       0  4912.1     .06       0
 5039.62     .06       0 5814.42     .15       0 7728.77      .2       0
#XS Ineff= 3 ,-1
    1545    2465  166.61    3709    4831  163.73    5128    8545  161.28
Permanent Ineff=
       F       F       F
Bank Sta=4912.1,5039.62
XS Rating Curve= 0
Exp/Cntr=.5,.3

Type RM Length L Ch R = 3 ,70851.2 ,,,
BEGIN DESCRIPTION:
SH 249 SBFR
END DESCRIPTION:
Bridge Culvert--1,0,-1,-1, 0
Deck Dist Width WeirC Skew NumUp NumDn MinLoCord MaxHiCord MaxSubmerge Is_Ogee
19,92,2.6,0, 69, 43, , , .95, 0, 0,0,,
 3326.88 3335.81    3353 3370.12 3394.21 3406.09 3410.92 3528.68 3540.61 3690.62
  3697.6  3697.6 3705.04 3708.59 3714.28 3719.26 3723.28 3730.22  3740.6 3779.73
 3833.59  3916.1 3946.33 3976.36 4084.58 4269.52 4427.03 4598.25 4650.95 4695.48
 4702.77  4862.6  4862.6 4931.88 5001.16 5070.45 5070.45 5183.29 5193.94 5209.54
 5213.24  5223.5 5228.03 5231.73 5239.12 5246.51 5251.81 5268.66 5279.93  5291.2
 5313.74 5320.97 5350.82 5463.32 5463.32 5846.84 5859.24 5898.41 5905.31 5920.24
 5925.36 5940.72 5946.66 5967.29 6136.29 6353.69 6544.64 6562.36 7291.41
  157.71  157.67  157.79  157.77  157.79  157.74  157.76  157.13  157.13  157.89
  157.89   160.6  160.68  160.65  160.75  160.68  160.75  160.73  160.79  160.92
  161.11  161.19  161.27  161.19  160.88   160.3  160.95  161.68  162.28  162.63
  162.72  163.28  163.28     164  164.28  163.61  163.61  163.56  163.49  163.33
  163.26  163.23  163.27  163.15  163.05  163.02  162.87   162.7  162.64  162.51
  162.17  162.14  161.86  161.51  158.76  158.04  157.99     158  158.04  158.02
  158.08  158.06  158.15  158.17  158.62  158.01  158.72  158.67     157
                                                                                
                                                                                
                                                                                
                  157.78   158.5  158.78  158.11
                                                                                
                                                                                
                                                                        
 2853.46 2875.21 2882.82 2910.13 2931.24  2937.6 2950.06  2966.7 2976.23 3034.08
 3104.16 3115.15 3204.28 3209.65 3224.52 3270.38 3286.54 3319.88 3328.81    3346
 3363.12 3387.21  3517.6 3926.64 4287.42 4536.27    4784    4784    4878    4878
  4947.8    5017 5085.85 5085.85    5148    5148 5176.29 5186.94 5756.21 5760.99
 5768.42 5777.38 5795.32
  158.23  158.24  158.21  158.18  158.14  158.09  158.07  157.93  157.89   157.8
  157.61  157.59  157.74  157.72  157.75  157.72  157.77  157.71  157.67  157.79
  157.77  157.79  157.17  158.61  157.59  158.59  160.28  163.03  163.28  163.28
     164  164.28  163.61  163.61  163.58  160.83  160.81  160.74  157.78  157.69
  157.66  157.77  157.77
                                                                                
                                                                                
                                                                          159.92
  160.27  160.01  159.22
                        
Pier Skew, UpSta & Num, DnSta & Num=  ,4931.88, 2 ,4947, 2 , 0 , 0 , 0 ,,
     2.5     2.5
     145   159.3
     2.5     2.5
     145   160.8
Pier Skew, UpSta & Num, DnSta & Num=  ,5001.16, 2 ,5016.7, 2 , 0 , 0 , 0 ,,
     2.5     2.5
     145   159.3
     2.5     2.5
     145     161
BR Coef=-1 , 0 , 0 ,, 0 ,,,.8,-1,,0,
WSPro=,,,, 1 ,,,, 0 ,,,, 0 ,,,,-1 ,-1 ,-1 , 0 , 0 , 0 , 0 , 0
BC Design=,, 0 ,, 0 ,,,,,,
BC HTab HWMax=164.25