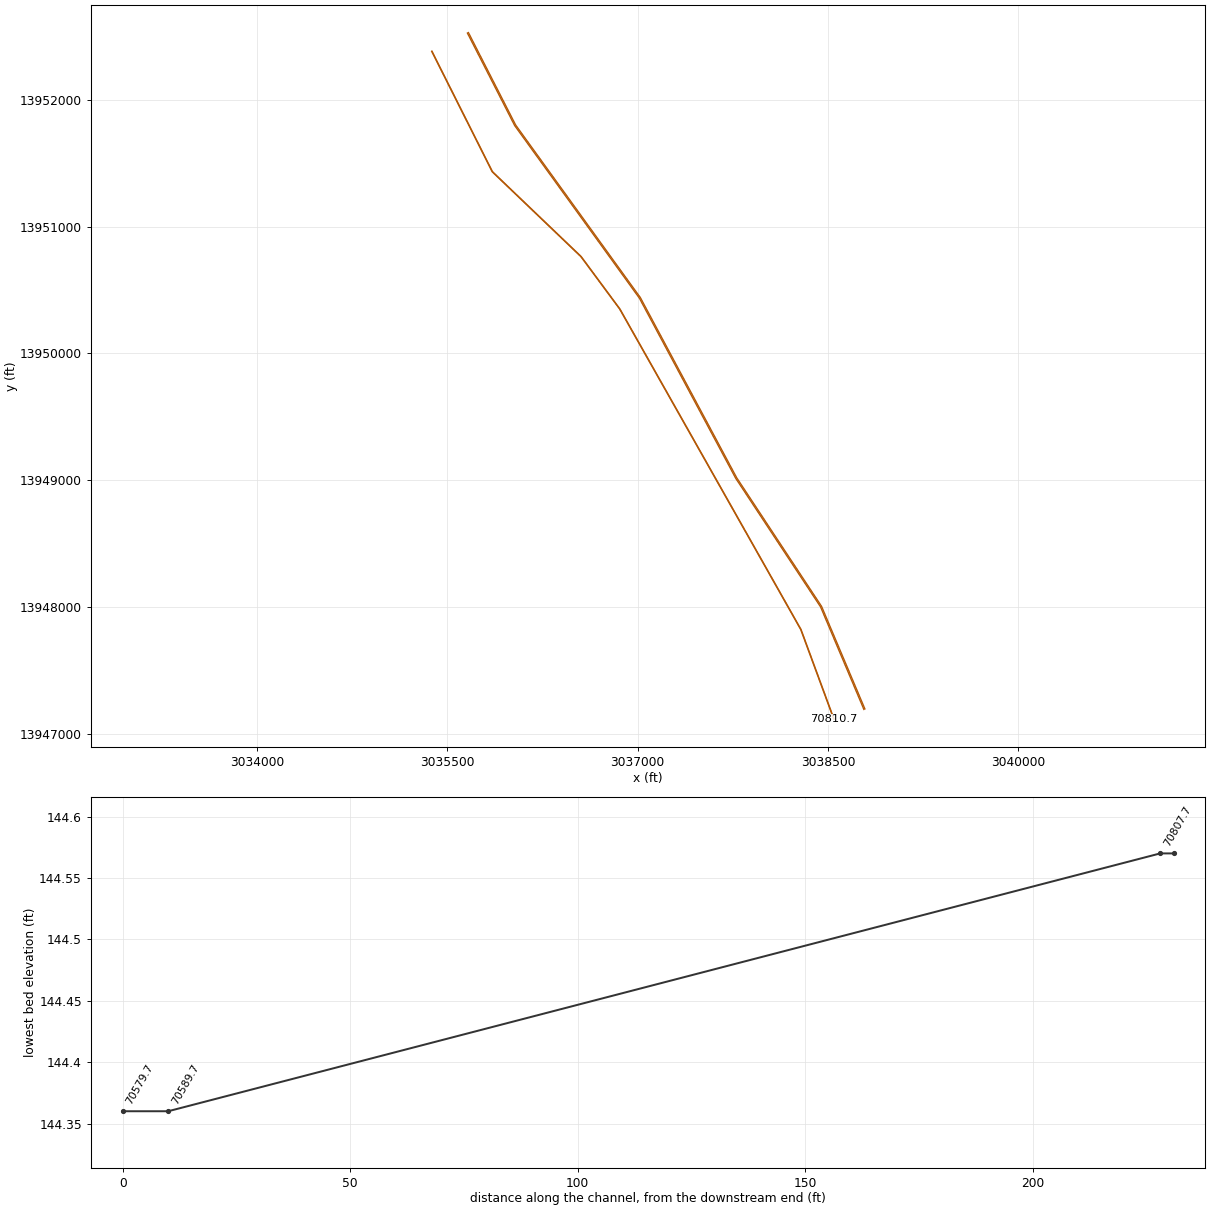
HEC-RAS study M100-00-00.prj: M100-00-00

--- M100-00-00.g01 (geometry) --- (continued)

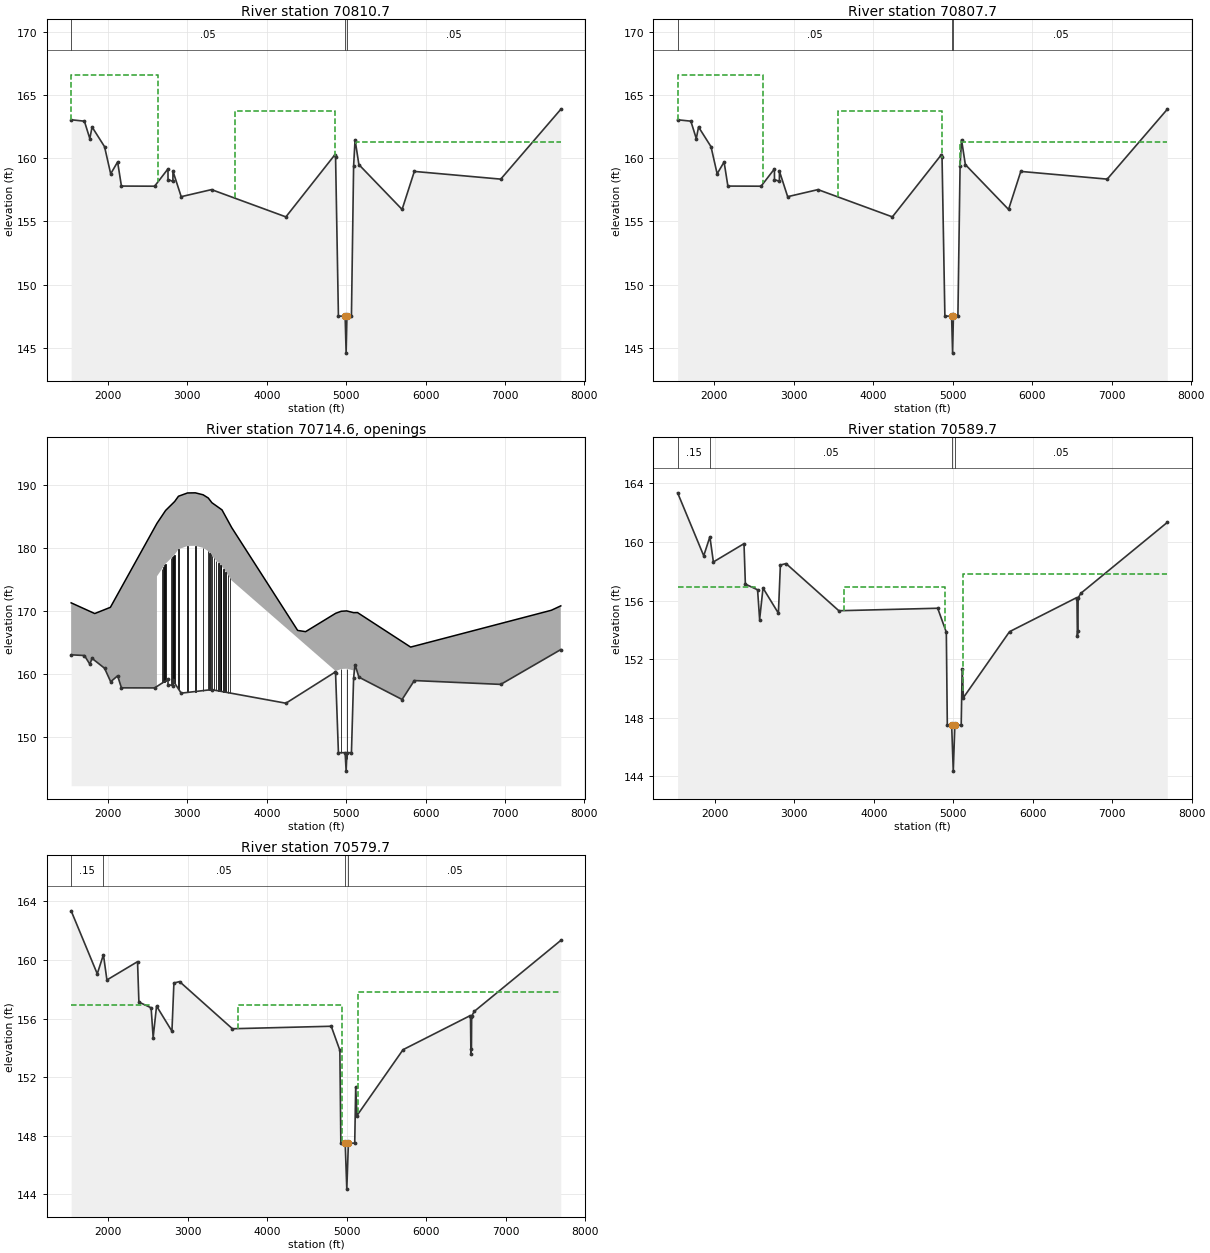
Type RM Length L Ch R = 1 ,70810.7 ,3,3,3
XS GIS Cut Line= 6
     3035377.841     13952379.37     3035854.422     13951430.73
     3036553.557     13950761.79      3036858.19     13950349.81
     3038285.089      13947824.5     3038544.907     13947119.12
#Sta/Elev= 30
    1538  163.05 1704.62  162.94 1773.01  161.56 1801.45  162.48 1958.32  160.92
 2035.71  158.77 2123.02  159.71 2170.82   157.8 2588.79  157.79 2756.87  159.16
  2757.4  158.32    2819  158.17 2819.63  158.98 2923.39  156.96 3305.03  157.52
 4241.38  155.36  4855.4  160.26 4866.69   160.1 4902.56   147.5 4987.14   147.5
 4999.62  144.57 5009.81   147.5 5066.45   147.5 5093.74  159.38 5112.06  161.47
 5160.21   159.5 5704.14  155.95 5858.19  158.96 6945.97  158.35 7701.94  163.88
#Mann= 3 , 0 , 0
    1538     .05       0 4987.14     .06       0 5009.81     .05       0
#XS Ineff= 3 ,-1
    1538    2634  166.61    3603    4864  163.73    5121    8538  161.28
Permanent Ineff=
       F       F       F
Bank Sta=4987.14,5009.81
XS Rating Curve= 0
Exp/Cntr=.5,.3

Type RM Length L Ch R = 1 ,70807.7 ,218,218,218
XS GIS Cut Line= 6
     3035380.522     13952380.72     3035856.878     13951432.52
     3036555.742     13950763.85     3036860.742     13950351.39
     3038287.742      13947825.9     3038547.809     13947119.88
#Sta/Elev= 30
    1538  163.05 1704.62  162.94 1773.01  161.56 1801.45  162.48 1958.32  160.92
 2035.71  158.77 2123.02  159.71 2170.82   157.8 2588.79  157.79 2756.87  159.16
  2757.4  158.32    2819  158.17 2819.63  158.98 2923.39  156.96 3305.03  157.52
 4241.38  155.36  4855.4  160.26 4866.69   160.1 4902.56   147.5 4987.14   147.5
 4999.62  144.57 5009.81   147.5 5066.45   147.5 5093.74  159.38 5112.06  161.47
 5160.21   159.5 5704.14  155.95 5858.19  158.96 6945.97  158.35 7701.94  163.88
#Mann= 3 , 0 , 0
    1538     .05       0 4987.14     .06       0 5009.81     .05       0
#XS Ineff= 3 ,-1
    1538    2617  166.61    3560    4867  163.73 5094.17 7701.94  161.28
Permanent Ineff=
       F       F       F
Bank Sta=4987.14,5009.81
XS Rating Curve= 0
Exp/Cntr=.5,.3

Type RM Length L Ch R = 4 ,70714.6 ,,,
BEGIN DESCRIPTION:
SH 249 MAINLANES
END DESCRIPTION:
Bridge Culvert--1,0,-1,-1, 0
Deck Dist Width WeirC Skew NumUp NumDn MinLoCord MaxHiCord MaxSubmerge Is_Ogee
1,216,2.6,0, 29, 29, , , .98, 0, 0,0,,
    1538    1835    2032    2618    2618    2727    2841    2889    3003    3101
    3199    3264    3310    3437    3559    3559  4389.2  4489.2    4868    4868
 4937.28 5006.56 5093.17 5093.17  5143.2  5143.2  5811.5  7582.7 7701.94
  171.31  169.61   170.6  183.94  183.94  185.99  187.41  188.25  188.77  188.79
  188.48  187.97  187.22  186.08  183.27  183.27  166.93  166.73  169.65  169.65
  169.97  170.03  169.75  169.75  169.76  169.76  164.28  170.13  170.83
                                  175.53  177.52  178.96  179.81  180.35  180.37
  180.05  179.53  178.76  177.07  174.86                                  160.47
  160.79  160.85  160.57
    1531    1828    2025    2511    2511    2631    2742    2843    2953    3051
    3147    3269    3386    3509    3624    3624  4382.2  4482.2    4898    4898
 4967.28 5036.56 5123.17 5123.17  5136.2  5136.2  5804.5  7575.7 7692.92
  171.31  169.61   170.6  183.94  183.94  185.99  187.41  188.25  188.77  188.79
  188.48  187.97  187.22  186.08  183.27  183.27  166.93  166.73  169.65  169.65
  169.97  170.03  169.75  169.75  169.76  169.76  164.28  170.13  170.83
                                  175.53  177.52  178.96  179.81  180.35  180.37
  180.05  179.53  178.76  177.07  174.86                                  160.47
  160.79  160.85  160.57
Pier Skew, UpSta & Num, DnSta & Num=  ,2683.9, 2 ,2631, 2 , 0 , 0 , 0 ,,
    5.11    5.11
     150     185
    5.11    5.11
     150     185
Pier Skew, UpSta & Num, DnSta & Num=  ,2698.2, 2 ,2645.4, 2 , 0 , 0 , 0 ,,
    5.11    5.11
     150     185
    5.11    5.11
     150     185
Pier Skew, UpSta & Num, DnSta & Num=  ,2712.6, 2 ,2659.8, 2 , 0 , 0 , 0 ,,
    5.11    5.11
     150     185
    5.11    5.11
     150     185
Pier Skew, UpSta & Num, DnSta & Num=  ,2727, 2 ,2674.7, 2 , 0 , 0 , 0 ,,
    5.11    5.11
     150     185
    5.11    5.11
     150     185
Pier Skew, UpSta & Num, DnSta & Num=  ,2797.9, 2 ,2742, 2 , 0 , 0 , 0 ,,
    5.11    5.11
     150     185
    5.11    5.11
     150     185
Pier Skew, UpSta & Num, DnSta & Num=  ,2812.2, 2 ,2756.4, 2 , 0 , 0 , 0 ,,
    5.11    5.11
     150     185
    5.11    5.11
     150     185
Pier Skew, UpSta & Num, DnSta & Num=  ,2826.6, 2 ,2770.8, 2 , 0 , 0 , 0 ,,
    5.11    5.11
     150     185
    5.11    5.11
     150     185
Pier Skew, UpSta & Num, DnSta & Num=  ,2841, 2 ,2785.1, 2 , 0 , 0 , 0 ,,
    5.11    5.11
     150     185
    5.11    5.11
     150     185
Pier Skew, UpSta & Num, DnSta & Num=  ,2889, 2 ,2843, 2 , 0 , 0 , 0 ,,
    5.25    5.25
     150     185
    5.25    5.25
     150     185
Pier Skew, UpSta & Num, DnSta & Num=  ,3003, 2 ,2953, 2 , 0 , 0 , 0 ,,
    5.25    5.25
     150     185
    5.25    5.25
     150     185
Pier Skew, UpSta & Num, DnSta & Num=  ,3101, 2 ,3051, 2 , 0 , 0 , 0 ,,
    5.25    5.25
     150     185
    5.25    5.25
     150     185
Pier Skew, UpSta & Num, DnSta & Num=  ,3199, 2 ,3147, 2 , 0 , 0 , 0 ,,
    5.25    5.25
     150     185
    5.25    5.25
     150     185
Pier Skew, UpSta & Num, DnSta & Num=  ,3264, 2 ,3221.9, 2 , 0 , 0 , 0 ,,
     5.1     5.1
     150     185
     5.1     5.1
     150     185
Pier Skew, UpSta & Num, DnSta & Num=  ,3279.7, 2 ,3237.6, 2 , 0 , 0 , 0 ,,
     5.1     5.1
     150     185
     5.1     5.1
     150     185
Pier Skew, UpSta & Num, DnSta & Num=  ,3295.4, 2 ,3253.3, 2 , 0 , 0 , 0 ,,
     5.1     5.1
     150     185
     5.1     5.1
     150     185
Pier Skew, UpSta & Num, DnSta & Num=  ,3310.675, 2 ,3276.8, 2 , 0 , 0 , 0 ,,
    5.95    5.95
     150     185
     4.6     4.6
     150     185
Pier Skew, UpSta & Num, DnSta & Num=  ,3337.3, 2 ,3304.1, 2 , 0 , 0 , 0 ,,
     4.6     4.6
     150     185
     4.6     4.6
     150     185
Pier Skew, UpSta & Num, DnSta & Num=  ,3364.6, 2 ,3331.4, 2 , 0 , 0 , 0 ,,
     4.6     4.6
     150     185
     4.6     4.6
     150     185
Pier Skew, UpSta & Num, DnSta & Num=  ,3391.9, 2 ,3358.7, 2 , 0 , 0 , 0 ,,
     4.6     4.6
     150     185
     4.6     4.6
     150     185
Pier Skew, UpSta & Num, DnSta & Num=  ,3419.2, 2 ,3386, 2 , 0 , 0 , 0 ,,
     4.6     4.6
     150     185
     4.6     4.6
     150     185
Pier Skew, UpSta & Num, DnSta & Num=  ,3427, 2 ,3399.8, 2 , 0 , 0 , 0 ,,
     4.6     4.6
     150     185
     4.6     4.6
     150     185
Pier Skew, UpSta & Num, DnSta & Num=  ,3454.3, 2 ,3427.1, 2 , 0 , 0 , 0 ,,
     4.6     4.6
     150     185
     4.6     4.6
     150     185
Pier Skew, UpSta & Num, DnSta & Num=  ,3481.6, 2 ,3454.4, 2 , 0 , 0 , 0 ,,
     4.6     4.6
     150     185
     4.6     4.6
     150     185
Pier Skew, UpSta & Num, DnSta & Num=  ,3508.9, 2 ,3481.7, 2 , 0 , 0 , 0 ,,
     4.6     4.6
     150     185
     4.6     4.6
     150     185
Pier Skew, UpSta & Num, DnSta & Num=  ,3536.2, 2 ,3509, 2 , 0 , 0 , 0 ,,
     4.6     4.6
     150     185
     4.6     4.6
     150     185
Pier Skew, UpSta & Num, DnSta & Num=  ,4937.28, 2 ,4967.28, 2 , 0 , 0 , 0 ,,
     2.5     2.5
     140  161.88
     2.5     2.5
     140  161.88
Pier Skew, UpSta & Num, DnSta & Num=  ,5006.56, 2 ,5036.56, 2 , 0 , 0 , 0 ,,
     2.5     2.5
     140     162
     2.5     2.5
     140     162
Pier Skew, UpSta & Num, DnSta & Num=  ,, 0 ,3269, 2 , 0 , 0 , 0 ,,
     5.1     5.1
     150     185
Abutment Skew #Up #Dn= , 2 , 2
    4868 4918.64
  159.88     143
    4898 4942.64
  159.88     145
Abutment Skew #Up #Dn= , 2 , 2
 5050.36 5093.17
     145  159.27
 5080.36 5123.17
     145  159.27
BR Coef=-1 , 0 , 0 ,, 0 ,,,.8,-1,,0,
WSPro=,,,, 1 ,,,, 0 ,,,, 0 ,,,,-1 ,-1 ,-1 , 0 , 0 , 0 , 0 , 0
BC Mult= 3 ,1538,4638,1531,4631
BC Mult= 3 ,3838,7701.94,3831,7694.94
BC Design=,, 0 ,, 0 ,,,,,,
BC HTab HWMax=163.88

Type RM Length L Ch R = 1 ,70589.7 ,10,10,10
XS GIS Cut Line= 6
     3035659.371     13952523.68     3036031.826      13951794.8
     3037013.955     13950435.74     3037773.223     13949015.98
     3038441.234     13948003.69     3038782.708      13947195.4
#Sta/Elev= 30
    1531  163.36 1859.61  159.06 1937.16  160.36 1981.15  158.64 2366.51  159.89
  2383.6  157.13 2537.36  156.74 2563.07  154.71  2605.7  156.86 2799.36  155.14
 2824.12  158.43 2895.32  158.53 3560.04  155.31 4804.04  155.48 4912.52  153.84
 4925.04   147.5 4979.68   147.5 4999.97  144.36    5020   147.5 5099.72   147.5
 5111.84  151.35 5127.85  149.38 5707.71  153.88 6550.74   156.2  6556.6  156.14
 6561.89  153.59 6568.47  153.96 6571.15  156.18  6605.2   156.5 7692.92  161.34
#Mann= 4 ,-1 , 0
    1531     .15       0 1937.16     .05       0 4979.68     .06       0
    5020     .05       0
#XS Ineff= 3 ,-1
    1531    2510   156.9    3625    4897   156.9 5124.17    8531   157.8
Permanent Ineff=
       F       F       F
Bank Sta=4979.68,5020
XS Rating Curve= 0
Exp/Cntr=.5,.3

Type RM Length L Ch R = 1 ,70579.7 ,95,95,95
XS GIS Cut Line= 6
       3035667.4     13952527.88      3036039.85       13951799.
      3037021.98     13950439.94      3037781.25     13949020.18
      3038449.26     13948007.88      3038790.74      13947199.6
#Sta/Elev= 30
    1531  163.36 1859.61  159.06 1937.16  160.36 1981.15  158.64 2366.51  159.89
  2383.6  157.13 2537.36  156.74 2563.07  154.71  2605.7  156.86 2799.36  155.14
 2824.12  158.43 2895.32  158.53 3560.04  155.31 4804.04  155.48 4912.52  153.84
 4925.04   147.5 4979.68   147.5 4999.97  144.36    5020   147.5 5099.72   147.5
 5111.84  151.35 5127.85  149.38 5707.71  153.88 6550.74   156.2  6556.6  156.14
 6561.89  153.59 6568.47  153.96 6571.15  156.18  6605.2   156.5 7692.92  161.34
#Mann= 4 ,-1 , 0
    1531     .15       0 1937.16     .05       0 4979.68     .06       0
    5020     .05       0
#XS Ineff= 3 ,-1
    1531    2510   156.9    3625    4937   156.9  5146.8    8531   157.8
Permanent Ineff=
       F       F       F
Bank Sta=4979.68,5020
XS Rating Curve= 0
Exp/Cntr=.5,.3