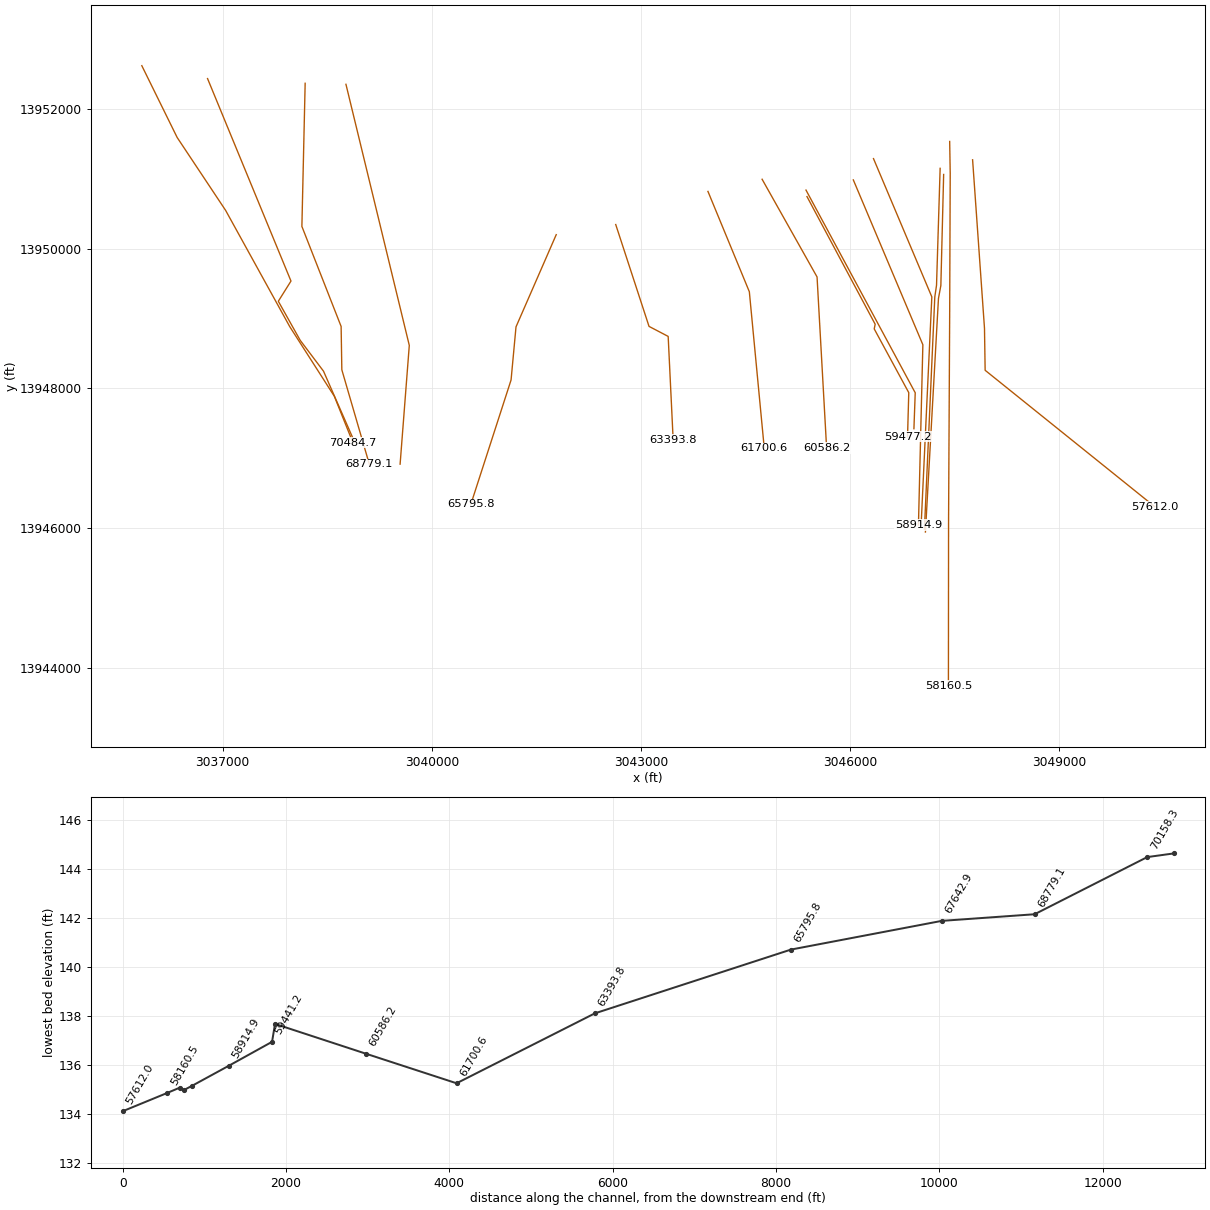
HEC-RAS study M100-00-00.prj: M100-00-00

--- M100-00-00.g01 (geometry) --- (continued)

Type RM Length L Ch R = 3 ,70561.3 ,,,
BEGIN DESCRIPTION:
SH 249 NBFR
END DESCRIPTION:
Bridge Culvert--1,0,-1,-1, 0
Deck Dist Width WeirC Skew NumUp NumDn MinLoCord MaxHiCord MaxSubmerge Is_Ogee
1,58,2.6,0, 68, 76, , , .98, 0, 0,0,,
    1531 2343.47 2612.04 3427.13 3456.81 3474.28 3483.45 3508.59 3523.99 3855.38
 3863.75 3874.96 4047.71 4267.93 4483.88 4761.42 4761.42 4775.59 4782.86 4807.71
  4815.3 4820.81 4849.07 4854.72 4860.38 4866.03 4874.33 4881.73    4938    4938
  4997.5  5067.5  5145.8  5145.8 5182.24 5204.07 5209.89 5219.29 5226.48 5232.01
 5253.09  5260.6 5281.78 5287.31 5298.37 5313.17 5332.81 5343.22 5354.48 5393.23
 5419.24  5424.6 5431.95 5444.78 5460.25  5468.7 5490.08 5505.44 5530.69 5534.84
 5542.05 5560.87 5560.87 5848.09 6151.99  6479.9 6798.12 6990.92
  164.46  158.43  158.21  156.42  156.23  156.25  156.18  156.24  156.21  158.07
  158.15  158.15  157.75  158.91  158.25  159.54  162.29  162.32  162.51  162.63
  162.63  162.73  163.03  163.17  163.17  163.32  163.34  163.45  164.41  164.41
  164.74  164.95  164.62  164.62  164.27  164.03  164.05   163.9  163.89  163.77
  163.69  163.55  163.44  163.34   163.3  163.09  162.91  162.93  162.72  162.39
  162.08   162.1  161.93   161.9   161.7  161.77  161.55  161.55   161.4  161.45
  161.34  161.38  158.63  157.74   158.8  157.76  158.55  158.05
                                                                                
                                                                                
                                                                          158.91
  159.24  159.45  159.12
                                                                                
                                                                                
                                                                
    1439 2211.22 2520.04 2763.77 3188.74 3233.31 3239.18 3264.19 3319.14 3335.13
 3364.81 3382.28 3391.45 3416.59 3431.99 3459.11 3461.87 3484.48 3493.84 3519.99
 3519.99 3813.63 3943.28 4175.93 4335.42 4391.88 4403.02 4408.49 4432.62 4432.62
 4582.47 4669.42 4669.42 4683.59 4690.86 4715.71  4723.3 4728.81 4757.07 4762.72
 4768.38 4774.03 4782.33 4789.73 4808.24  4824.9  4836.2 4847.51 4853.16 4864.47
  4880.8  4880.8 4950.43 5019.62 5088.65 5088.65 5127.29 5134.48 5140.01 5161.09
  5168.6 5189.78 5195.31 5206.37 5221.17 5240.81 5251.22 5262.48 5262.48 5749.83
 6059.99  6387.9 6716.64 6999.64 7021.14 7037.28
  164.46  158.38  158.21   156.8  156.77  156.84  156.82  156.87  156.61  156.42
  156.23  156.25  156.18  156.24  156.21  155.92  155.93   155.7  155.87  155.99
  158.74  160.94  160.44  161.66  160.97     161  160.94  161.04  161.04  158.39
   158.7  159.54  162.29  162.32  162.51  162.63  162.63  162.73  163.03  163.17
  163.17  163.32  163.34  163.45   163.6  163.85  163.87  164.04  164.04  164.23
  164.32  164.32  164.51  164.29   163.9   163.9   163.9  163.89  163.77  163.69
  163.55  163.44  163.34   163.3  163.09  162.91  162.93  162.72  159.97   157.8
   158.8  157.76  158.46   157.8  157.78  157.85
                                                                                
                                                                                
                                                                                
                                                                                
                                                                                
          158.27  158.46  158.24  157.85
                                                                                
                                                
Pier Skew, UpSta & Num, DnSta & Num=  ,5007.3, 2 ,4950.08, 2 , 0 , 0 , 0 ,,
     2.5     2.5
     140   159.5
     2.5     2.5
     140   159.5
Pier Skew, UpSta & Num, DnSta & Num=  ,5076.56, 2 ,5019.36, 2 , 0 , 0 , 0 ,,
     2.5     2.5
     140   159.5
     2.5     2.5
     140   159.5
BR Coef=-1 , 0 , 0 ,, 0 ,,,.8,-1,,0,
WSPro=,,,, 1 ,,,, 0 ,,,, 0 ,,,,-1 ,-1 ,-1 , 0 , 0 , 0 , 0 , 0
BC Design=,, 0 ,, 0 ,,,,,,
BC HTab HWMax=163.45

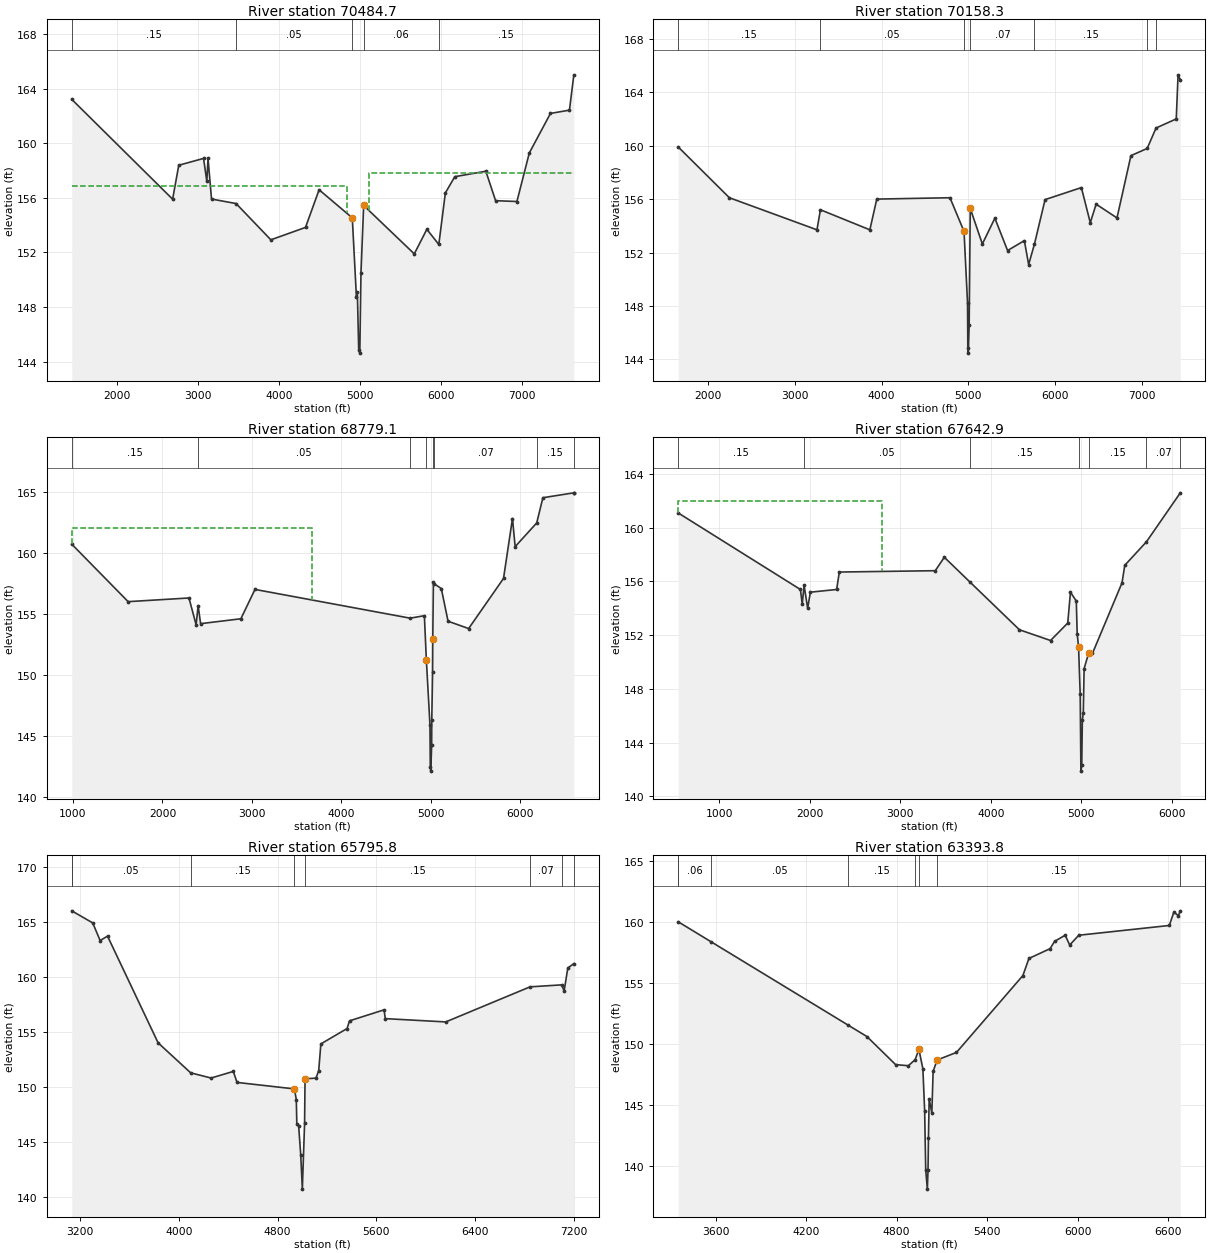
Type RM Length L Ch R = 1 ,70484.7 ,521.3,326.4,35.78
XS GIS Cut Line= 6
  3035839.63571813952615.8778344 3036346.492010113951589.2704345
 3037042.576983613950544.9424582 3037962.8756517 13948881.647904
 3038601.233663713947887.7254006  3038869.76072513947220.2322745
#Sta/Elev= 30
    1439  163.23 2685.97  155.91 2762.01   158.4 3068.42   158.9 3108.91  157.21
 3123.48  158.91 3166.96  155.92 3470.43  155.59 3900.52  152.93 4328.99  153.84
 4496.98   156.6 4907.38  154.54 4958.58  148.73 4969.83  149.12 4986.71  144.86
 5000.19  144.62 5014.83  150.53 5048.01  155.45 5673.67   151.9 5829.25   153.7
 5977.12  152.59 6058.08  156.37 6174.88  157.56 6558.69  157.96 6679.12   155.8
 6942.89  155.74 7096.01   159.3  7357.6   162.2 7592.29  162.44 7646.66  165.03
#Mann= 5 ,-1 , 0
    1439     .15       0 3470.43     .05       0 4907.38     .06       0
 5048.01     .06       0 5977.12     .15       0
#XS Ineff= 2 , 0
    1439    4843   156.9    5118    1439   157.8
Permanent Ineff=
       F       F
Bank Sta=4907.38,5048.01
XS Rating Curve= 0
Exp/Cntr=.5,.3

Type RM Length L Ch R = 1 ,70158.3 ,1111.64,1379.2,1428.3
BEGIN DESCRIPTION:
Cross Section XS35.4
Cross Section M100-00-00-X35
Located At: DS FM 249
END DESCRIPTION:
XS GIS Cut Line= 6
       3036782.713952431.4699994 3037979.569999713949534.9300003
 3037798.0399284 13949246.136131 3038111.835563213948687.6089157
 3038446.540669613948245.4912823 3038894.224165113947227.7496857
#Sta/Elev= 30
  1654.4   159.9  2244.4   156.1  3254.4   153.7  3294.4   155.2  3864.4   153.7
  3944.4     156  4788.5   156.1  4950.5  153.58    4991  148.23  4994.5  144.83
    5000  144.47  5009.8  146.57  5022.4   155.3  5161.9  152.64 5306.28  154.57
 5452.78  152.15 5646.44  152.89 5695.82   151.1 5763.17  152.64 5885.33  155.96
 6303.99  156.86 6406.88  154.23 6474.06  155.62  6714.8  154.59 6875.41  159.25
 7062.84  159.79 7165.29  161.32 7398.27     162 7419.19   165.3 7445.08  164.93
#Mann= 7 ,-1 , 0
  1654.4     .15       0  3294.4     .05       0  4950.5     .08       0
  5022.4     .07       0 5763.17     .15       0 7062.84     .07       0
 7165.29     .15       0
Bank Sta=4950.5,5022.4
XS Rating Curve= 0
Exp/Cntr=.3,.1

Type RM Length L Ch R = 1 ,68779.1 ,999.87,1136.2,969.65
BEGIN DESCRIPTION:
Cross Section 68779.1
Cross Section XS35
Cross Section M100-00-00-X35
Located At: DS FM 249
END DESCRIPTION:
XS GIS Cut Line= 5
      3038183.03     13952364.12      3038136.11     13950316.72
      3038698.97     13948885.51       3038709.2     13948265.61
      3039103.33     13946916.02
#Sta/Elev= 30
   986.4   160.7  1616.4     156  2296.4   156.3  2376.4   154.1  2398.7  155.68
  2426.4   154.2  2876.4   154.6  3034.3     157  4767.9  154.65  4927.6  154.85
  4949.6  151.25  4990.1   145.9  4993.6   142.5  4999.1  142.14  5008.9  144.24
  5010.3  146.31  5019.3  150.22  5021.5  152.97  5028.4   157.6  5035.6  157.47
  5116.9  157.07  5192.2   154.4  5422.2   153.8  5812.2   157.9  5912.2   162.8
  5942.2   160.5  6183.4  162.44  6252.2   164.5  6598.1   164.9  6598.2   164.9
#Mann= 8 ,-1 , 0
   986.4     .15       0  2398.7     .05       0  4767.9     .15       0
  4949.6     .08       0  5021.5     .15       0  5035.6     .07       0
  6183.4     .15       0  6598.1      .2       0
#XS Ineff= 2 , 0
       0    3675     162               0
Permanent Ineff=
       F       F
Bank Sta=4949.6,5021.5
XS Rating Curve= 0
Exp/Cntr=.3,.1

Type RM Length L Ch R = 1 ,67642.9 ,1697.05,1847.1,1633.8
BEGIN DESCRIPTION:
Cross Section 67642.9
Cross Section XS34
Cross Section M100-00-00-X34
Located At: 2ND DS FM 249
END DESCRIPTION:
XS GIS Cut Line= 3
      3038768.23     13952349.49      3039676.94     13948614.74
      3039545.23     13946916.02
#Sta/Elev= 30
   546.3   161.1  1896.3   155.4  1916.3   154.3  1936.7  155.71  1976.3     154
  2006.3   155.2  2296.3   155.4  2326.3   156.7  3386.3   156.8  3486.3   157.8
  3773.4  155.93  4316.3   152.4    4660   151.6    4850   152.9    4880   155.2
  4944.5  154.54  4954.4  152.11  4969.7  151.11  4987.5   147.6  4995.5  141.87
  5004.7   142.3  5011.3  145.68  5021.8  146.19  5030.8  149.51  5081.3  150.66
  5123.1  150.64    5450   155.9    5480   157.2  5719.3  158.95  6093.8   162.6
#Mann= 7 ,-1 , 0
   546.3     .15       0  1936.7     .05       0  3773.4     .15       0
  4969.7     .08       0  5081.3     .15       0  5719.3     .07       0
  6093.8      .2       0
#XS Ineff= 2 , 0
       0    2800     162               0
Permanent Ineff=
       F       F
Bank Sta=4969.7,5081.3
XS Rating Curve= 0
Exp/Cntr=.3,.1

Type RM Length L Ch R = 1 ,65795.8 ,1867.1,2402,2313.49
BEGIN DESCRIPTION:
Cross Section 65795.8
Cross Section XS33
Cross Section M100-00-00-X33
Located At: 3RD US HUFSMITH-KOHRVILLE
END DESCRIPTION:
XS GIS Cut Line= 4
      3041785.07      13950198.8      3041207.92      13948879.6
      3041137.12      13948120.4      3040560.41      13946342.7
#Sta/Elev= 30
  3131.3     166  3301.3   164.9  3361.3   163.3  3421.3   163.7  3831.3     154
  4095.8  151.27  4261.3   150.8  4441.3   151.4  4471.3   150.4  4936.9  149.81
    4952  148.84  4956.3  146.59  4971.1  146.45  4988.1  143.77    5001   140.7
  5019.2  146.67  5022.9  150.73  5111.2  150.79  5133.7  151.47  5151.2   153.9
  5363.7   155.3  5383.7     156  5663.7     157  5673.7   156.2  6163.7   155.9
  6847.6  159.09  7104.7  159.27  7123.7   158.7  7153.7   160.8  7202.6   161.2
#Mann= 8 , 1 , 0
  3131.3      .2       0  3131.3     .05       0  4095.8     .15       0
  4936.9     .08       0  5022.9     .15       0  6847.6     .07       0
  7104.7     .15       0  7202.6      .2       0
Bank Sta=4936.9,5022.9
XS Rating Curve= 0
Exp/Cntr=.3,.1

Type RM Length L Ch R = 1 ,63393.8 ,1576.19,1693.2,1264.25
BEGIN DESCRIPTION:
Cross Section 63393.8
Cross Section XS32
Cross Section M100-00-00-X32
Located At: 2ND US BNSF CORP
END DESCRIPTION:
XS GIS Cut Line= 4
      3042638.54      13950343.7      3043116.28      13948886.6
      3043390.97      13948743.3      3043462.63      13947262.3
#Sta/Elev= 30
    3353     160  3568.5  158.38  4477.9  151.54    4603   150.6    4793   148.3
  4877.4  148.21  4921.9   148.7  4947.4  149.54  4973.6  147.96  4985.3  144.53
  4992.4  139.65  5003.2   138.1  5007.6  139.65  5010.5  142.32  5015.2   145.5
  5032.9  144.33  5041.4  147.74    5068  148.68  5196.2   149.3  5636.2   155.6
  5676.2     157  5816.2   157.8  5846.2   158.4  5916.2   158.9  5946.2   158.1
  6006.2   158.9  6606.2   159.7  6636.2   160.8  6666.2   160.5  6678.9   160.9
#Mann= 8 , 1 , 0
    3353      .2       0    3353     .06       0  3568.5     .05       0
  4477.9     .15       0  4921.9     .07       0  4947.4     .08       0
    5068     .15       0  6678.9      .2       0
Bank Sta=4947.4,5068
XS Rating Curve= 0
Exp/Cntr=.3,.1

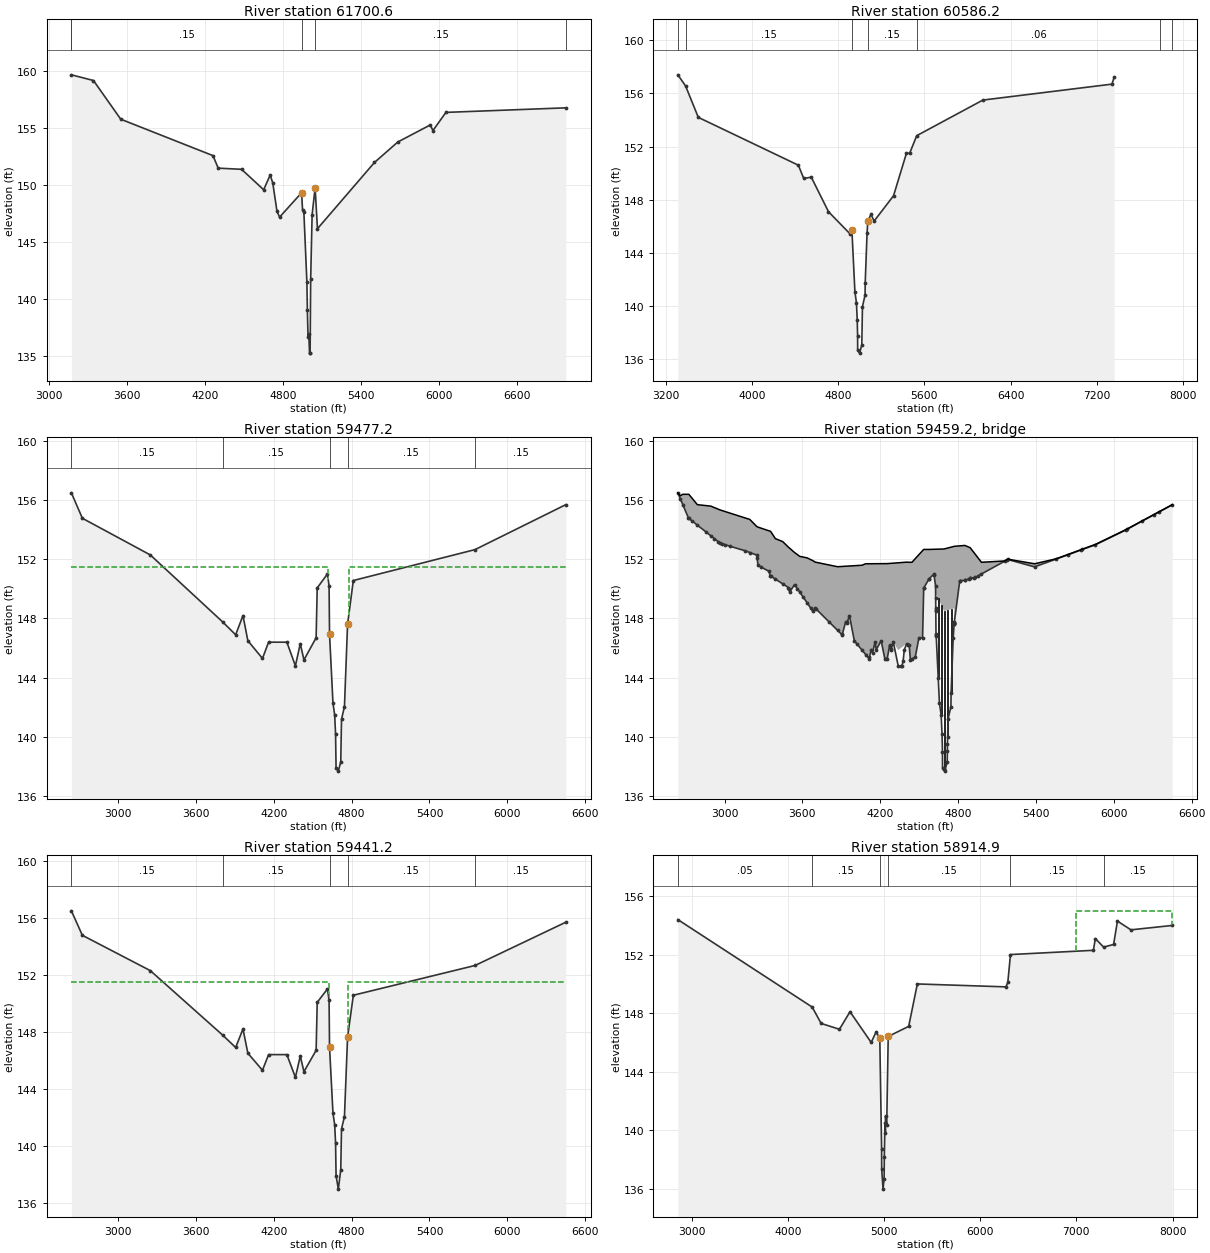
Type RM Length L Ch R = 1 ,61700.6 ,992.11,1114.4,1016.03
BEGIN DESCRIPTION:
Cross Section 61700.6
Cross Section XS31
END DESCRIPTION:
XS GIS Cut Line= 3
      3043961.74      13950817.1      3044555.38      13949382.5
      3044769.75      13947139.9
#Sta/Elev= 30
  3172.1   159.7  3342.1   159.2  3552.1   155.8  4262.1   152.6  4302.1   151.5
  4482.1   151.4  4652.1   149.6  4702.1   150.9  4722.1   150.2  4754.7   147.7
  4774.7   147.2    4944  149.34  4951.2  147.86  4961.4  147.66  4984.8  141.48
  4988.3  139.05  4993.6  136.66  4999.5   136.9  5004.8   135.3  5009.5  135.25
  5013.9  141.76  5024.9  147.41  5048.1  149.76    5066  146.18  5504.7     152
  5684.7   153.8  5934.7   155.3  5954.7   154.8  6054.7   156.4  6977.5   156.8
#Mann= 5 , 1 , 0
  3172.1      .2       0  3172.1     .15       0    4944     .08       0
  5048.1     .15       0  6977.5      .2       0
Bank Sta=4944,5048.1
XS Rating Curve= 0
Exp/Cntr=.3,.1

Type RM Length L Ch R = 1 ,60586.2 ,1029.9,1109,921
BEGIN DESCRIPTION:
Cross Section 60586.2
Cross Section XS30.9
END DESCRIPTION:
XS GIS Cut Line= 3
      3044738.64      13950991.2      3045526.89      13949593.8
      3045663.88      13947147.6
#Sta/Elev= 30
  3308.5   157.4  3380.4  156.56  3498.5   154.2  4428.5   150.6  4478.5   149.6
  4548.5   149.7  4708.5   147.1  4912.9   145.4 4926.05  145.71 4954.15  141.06
 4968.15  140.26 4975.45  138.97 4979.05  137.73 4979.55  136.68 4998.05  136.46
 5017.95  137.09 5024.15  139.96 5048.35  140.83 5049.75  141.76 5066.85  145.48
 5073.95  146.39  5102.9   146.9  5132.9   146.4  5312.9   148.3  5432.9   151.5
  5462.9   151.5  5528.3  152.82  6142.9   155.5  7342.9   156.7  7362.9   157.2
#Mann= 7 ,-1 , 0
  3308.5     .06       0  3380.4     .15       0 4926.05     .08       0
 5073.95     .15       0  5528.3     .06       0  7792.6     .15       0
  7903.4      .2       0
Bank Sta=4926.05,5073.95
XS Rating Curve= 0
Exp/Cntr=.5,.3

Type RM Length L Ch R = 1 ,59477.2 ,36,36,36
BEGIN DESCRIPTION:
Upstream Section of Bridge/Culvert/Weir
END DESCRIPTION:
XS GIS Cut Line= 5
      3045382.46      13950743.3      3046360.58      13948917.4
      3046347.11      13948850.4      3046842.67      13947938.7
      3046824.92       13947306.
#Sta/Elev= 30
2640.348  156.492724.921  154.773248.517  152.293806.131  147.763906.302  146.89
3962.684  148.194000.271  146.494113.035  145.294160.019  146.394300.973  146.39
4366.751  144.794404.339  146.29 4432.53  145.19  4526.5  146.694534.769  150.06
4613.515     1514626.295  150.214629.771  146.924656.271  142.274669.427  141.47
4676.286  140.184680.139  137.894697.523  137.674716.223   138.34722.049  141.17
 4744.79  142.044768.752   147.64813.105  150.565750.825  152.656450.614  155.69
#Mann= 5 ,-1 , 0
2640.348     .15       03806.131     .15       04629.771     .08       0
4768.752     .15       05750.825     .15       0
#XS Ineff= 2 , 0
       04620.375   151.54778.149       0   151.5
Permanent Ineff=
       F       F
Bank Sta=4629.771,4768.752
XS Rating Curve= 0
Skew Angle= 20
Exp/Cntr=.5,.3

Type RM Length L Ch R = 3 ,59459.2 ,,,
BEGIN DESCRIPTION:
BURLINGTON NORTHERN RAILROAD
Structure ID: M100-00-00-12
END DESCRIPTION:
Node Name=Burlington North
Bridge Culvert--1,0,-1,-1, 0
Deck Dist Width WeirC Skew NumUp NumDn MinLoCord MaxHiCord MaxSubmerge Is_Ogee
10,16,2.6,20, 48, 48, , , .95, 0, 1,1,,
2640.3482659.1422677.9362724.9212790.6992894.065 2966.613194.7673248.5173257.914
3342.4873351.8843354.5153392.1033448.4843492.8373502.2343539.8223580.0413636.423
3680.776 3699.573871.3454059.2844087.4754253.9884404.3394423.133 4432.534444.558
4470.1184498.309  4526.54534.7694576.6794691.697 4770.344770.4444851.8214892.792
4980.1835158.7245182.5935389.3255553.3955858.6086093.5316450.614
   156.5   156.3   156.4   156.4   155.7   155.6  155.34   154.7  154.22  154.18
  153.93  153.91   153.9   153.4   153.2  152.82  152.75  152.46   152.2   152.1
  151.91  151.81   151.5   151.6   151.7  151.71  151.81   151.8   151.8   151.8
  152.05  152.32  152.59  152.67  152.67   152.7  152.88  152.88  152.94  152.79
   151.8  151.89  152.01   151.7  152.03  153.01  154.01   155.7
   156.5  156.11  155.72  154.78  154.32   153.6   153.1  152.47   152.3   151.6
   151.2   150.9  150.89  150.67  150.35   150.1   149.8   150.3  149.79  149.07
   148.5   148.7   147.2  145.87  145.57   145.3   146.3   146.2   145.2  145.26
   145.4   146.7   146.7  150.07  150.69   148.5  148.68  147.72  150.58  150.73
  151.02  151.88     152   151.5  152.02     153     154   155.7
2640.3482659.1422677.9362724.9212790.6992894.065 2966.613194.7673248.5173257.914
3342.4873351.8843354.5153392.1033448.4843492.8373502.2343539.8223580.0413636.423
3680.776 3699.573871.3454059.2844087.4754253.9884404.3394423.133 4432.534444.558
4470.1184498.309  4526.54534.7694576.6794691.697 4770.344770.4444851.8214892.792
4980.1835158.7245182.5935389.3255553.3955858.6086093.5316450.614
   156.5   156.3   156.4   156.4   155.7   155.6  155.34   154.7  154.22  154.18
  153.93  153.91   153.9   153.4   153.2  152.82  152.75  152.46   152.2   152.1
  151.91  151.81   151.5   151.6   151.7  151.71  151.84   151.8   151.8   151.8
  152.05  152.32  152.59  152.67  152.67   152.7  152.88  152.88  152.94  152.79
   151.8  151.89  152.01   151.7  152.03  153.01  154.01   155.7
   156.5  156.11  155.72  154.78  154.32   153.6   153.1  152.47   152.3   151.6
   151.2   150.9  150.89  150.67  150.35   150.1   149.8   150.3  149.79  149.07
   148.5   148.7   147.2  145.87  145.57   145.3   146.3   146.2   145.2  145.26
   145.4   146.7   146.7  150.07  150.69   148.5  148.68  147.72  150.58  150.73
  151.02  151.88     152   151.5  152.02     153     154   155.7
Pier Skew= 20
Pier Skew, UpSta & Num, DnSta & Num=  ,4646.404, 2 ,4646.404, 2 , 0 , 0 , 0 ,,
    7.63    7.63
  142.82     160
    7.63    7.63
  142.82     160
Pier Skew, UpSta & Num, DnSta & Num=  ,4669.427, 2 ,4669.427, 2 , 0 , 0 , 0 ,,
    7.63    7.63
  140.28     160
    7.63    7.63
  140.28     160
Pier Skew, UpSta & Num, DnSta & Num=  ,4693.953, 2 ,4693.953, 2 , 0 , 0 , 0 ,,
    7.63    7.63
  136.79  149.51
    7.63    7.63
  136.79  148.77
Pier Skew, UpSta & Num, DnSta & Num=  ,4719.7, 2 ,4719.7, 2 , 0 , 0 , 0 ,,
    7.63    7.63
   138.7  149.56
    7.63    7.63
   138.7  148.82
Pier Skew, UpSta & Num, DnSta & Num=  ,4746.105, 2 ,4746.105, 2 , 0 , 0 , 0 ,,
    7.63    7.63
  141.22  149.62
    7.63    7.63
  141.22  148.88
Abutment Skew #Up #Dn= , 2 , 2
4627.8924629.866
  148.67  146.92
4627.8924629.866
  147.93  146.18
Abutment Skew #Up #Dn= , 2 , 2
4768.8464770.528
  147.62  148.68
4768.8464770.528
  146.88  147.94
BR Coef= 1 , 1 , 1 ,1.25, 0 ,,,.8,0,2,0,
WSPro=,,,, 1 ,,,, 0 ,,,, 0 ,,,,-1 ,-1 ,-1 , 0 , 0 , 0 , 0 , 0
BR U #Sta/Elev= 140
2640.348  156.492659.142   156.12677.936  155.71 2722.29  154.792724.921  154.77
2753.112  154.582790.699  154.312856.478  153.862894.065  153.592922.256   153.4
2950.447   153.2 2966.61  153.092978.638  153.063006.828  152.983044.416  152.88
3154.548  152.593194.767  152.463248.517  152.293251.149  152.093257.914  151.59
3279.339  151.493342.487  151.193351.884  150.893354.515  150.883392.103  150.66
3448.484  150.343492.837  150.093495.469  150.013502.234  149.793539.822  150.29
3561.247  150.023580.041  149.783608.232  149.423636.423  149.063664.613   148.7
3680.776  148.49 3699.57  148.693702.201  148.673806.131  147.763871.345  147.19
3906.302  146.893908.933  146.973934.493  147.79 3943.89  147.693946.521  147.76
3962.684  148.194000.271  146.494021.696  146.264059.284  145.864087.475  145.56
4113.035  145.294115.666  145.374131.829  145.894141.226  145.694160.019  146.39
4169.416  145.894207.004  146.494235.195  145.294253.988  145.294272.782  146.19
4275.413  146.114282.179  145.89 4284.81  145.964300.973  146.394338.561  144.79
4359.986  144.794366.751  144.794376.148  145.094385.545  145.894404.339  146.29
4416.367  146.234423.133  146.19 4432.53  145.194444.558  145.254470.118  145.39
4498.309  146.69  4526.5  146.694534.769  150.064535.051  150.064576.209  150.67
4576.679  150.684613.515     1514614.172  150.964626.295  150.214627.141  149.41
4627.892   148.74627.995   148.6 4628.08  148.524629.771  146.924629.866  146.91
4631.369  146.794646.404     1444656.271  142.274669.427  141.474676.286  140.18
4679.669  138.944680.139  137.894691.697  137.844693.953  137.834697.523  137.67
4716.223   138.34717.257  139.034718.008  139.51  4719.7     1404722.049  141.17
 4744.79  142.044746.105  142.974762.174  146.694768.752   147.64768.846  147.61
 4770.34  147.714770.444  147.714770.538  147.724771.195  147.764813.012  150.55
4813.105  150.564851.821  150.574852.197  150.574882.643  150.684892.416  150.72
4892.792  150.724923.801  150.77 4933.48  150.784951.992  150.874980.183  151.01
5158.724  151.875177.518  151.975182.593  151.995389.325  151.495553.395  152.01
5647.365  152.315750.825  152.655757.403  152.675858.608  152.996093.531  153.99
6105.089  154.056217.852  154.586311.821  155.036349.409  155.216450.614  155.69
BR U #Mann= 5
2640.348     .153806.131     .154629.771     .074768.752     .155750.825     .15
BR D #Sta/Elev= 140
2640.348  156.492659.142   156.12677.936  155.71 2722.29  154.792724.921  154.77
2753.112  154.582790.699  154.312856.478  153.862894.065  153.592922.256   153.4
2950.447   153.2 2966.61  153.092978.638  153.063006.828  152.983044.416  152.88
3154.548  152.593194.767  152.463248.517  152.293251.149  152.093257.914  151.59
3279.339  151.493342.487  151.193351.884  150.893354.515  150.883392.103  150.66
3448.484  150.343492.837  150.093495.469  150.013502.234  149.793539.822  150.29
3561.247  150.023580.041  149.783608.232  149.423636.423  149.063664.613   148.7
3680.776  148.49 3699.57  148.693702.201  148.673806.131  147.763871.345  147.19
3906.302  146.893908.933  146.973934.493  147.79 3943.89  147.693946.521  147.76
3962.684  148.194000.271  146.494021.696  146.264059.284  145.864087.475  145.56
4113.035  145.294115.666  145.374131.829  145.894141.226  145.694160.019  146.39
4169.416  145.894207.004  146.494235.195  145.294253.988  145.294272.782  146.19
4275.413  146.114282.179  145.89 4284.81  145.964300.973  146.394338.561  144.79
4359.986  144.794366.751  144.794376.148  145.094385.545  145.894404.339  146.29
4416.367  146.234423.133  146.19 4432.53  145.194444.558  145.254470.118  145.39
4498.309  146.69  4526.5  146.694534.769  150.064535.051  150.064576.209  150.67
4576.679  150.684613.515     1514614.172  150.964626.295  150.214627.141  149.41
4627.892   148.74627.995   148.6 4628.08  148.524629.771  146.924629.866  146.91
4631.369  146.794646.404     1444656.271  142.274669.427  141.474676.286  140.18
4679.669  138.944680.139  137.894691.697  137.844693.953  137.834697.523  136.94
4716.223   138.34717.257  139.034718.008  139.51  4719.7     1404722.049  141.17
 4744.79  142.044746.105  142.974762.174  146.694768.752   147.64768.846  147.61
 4770.34  147.714770.444  147.714770.538  147.724771.195  147.764813.012  150.55
4813.105  150.564851.821  150.574852.197  150.574882.643  150.684892.416  150.72
4892.792  150.724923.801  150.77 4933.48  150.784951.992  150.874980.183  151.01
5158.724  151.875177.518  151.975182.593  151.995389.325  151.495553.395  152.01
5647.365  152.315750.825  152.655757.403  152.675858.608  152.996093.531  153.99
6105.089  154.056217.852  154.586311.821  155.036349.409  155.216450.614  155.69
BR D #Mann= 5
2640.348     .153806.131     .154629.771     .074768.752     .155750.825     .15
BC Design=,, 0 ,, 0 ,,,,,,
BC HTab HWMax=156.49

Type RM Length L Ch R = 1 ,59441.2 ,526.3,526.3,526.3
BEGIN DESCRIPTION:
Downstream Section of Bridge/Culvert/Weir
END DESCRIPTION:
XS GIS Cut Line= 3
      3045368.18      13950836.5      3046935.28       13947937.
      3046916.64       13947423.
#Sta/Elev= 30
2640.348  156.492724.921  154.773248.517  152.293806.131  147.763906.302  146.89
3962.684  148.194000.271  146.494113.035  145.294160.019  146.394300.973  146.39
4366.751  144.794404.339  146.29 4432.53  145.19  4526.5  146.694534.769  150.06
4613.515     1514626.295  150.214629.771  146.924656.271  142.274669.427  141.47
4676.286  140.184680.139  137.894697.523  136.944716.223   138.34722.049  141.17
 4744.79  142.044768.752   147.64813.105  150.565750.825  152.656450.614  155.69
#Mann= 5 ,-1 , 0
2640.348     .15       03806.131     .15       04629.771     .08       0
4768.752     .15       05750.825     .15       0
#XS Ineff= 2 , 0
       04623.504   151.5 4775.02       0   151.5
Permanent Ineff=
       F       F
Bank Sta=4629.771,4768.752
XS Rating Curve= 0
Skew Angle= 20
Exp/Cntr=.5,.3

Type RM Length L Ch R = 1 ,58914.9 ,390.19,451.8,172.64
BEGIN DESCRIPTION:
Cross Section XS30.7
END DESCRIPTION:
XS GIS Cut Line= 3
      3046047.21       13950982.      3047044.85       13948624.
      3046981.53      13946044.8
#Sta/Elev= 30
  2856.7   154.4  4253.2  148.42  4346.7   147.3  4536.7   146.9  4646.7   148.1
  4866.7     146  4916.7   146.7  4956.2  146.33  4975.1  138.71    4976  137.35
  4989.9  135.97  5001.1  136.68  5003.4   138.2  5010.1  140.49  5014.8  139.78
  5015.7  140.97  5028.2  140.36  5043.8  146.41  5256.7   147.1  5346.7     150
  6267.1   149.8  6287.1   150.1    6315  152.01  7177.1   152.3  7197.1   153.1
  7283.5  152.52  7387.1   152.7  7427.1   154.3  7567.1   153.7  7997.1     154
#Mann= 6 ,-1 , 0
  2856.7     .05       0  4253.2     .15       0  4956.2     .08       0
  5043.8     .15       0    6315     .15       0  7283.5     .15       0
#XS Ineff= 2 , 0
       0                    7000       0     155
Permanent Ineff=
       F       F
Bank Sta=4956.2,5043.8
XS Rating Curve= 0
Exp/Cntr=.3,.1

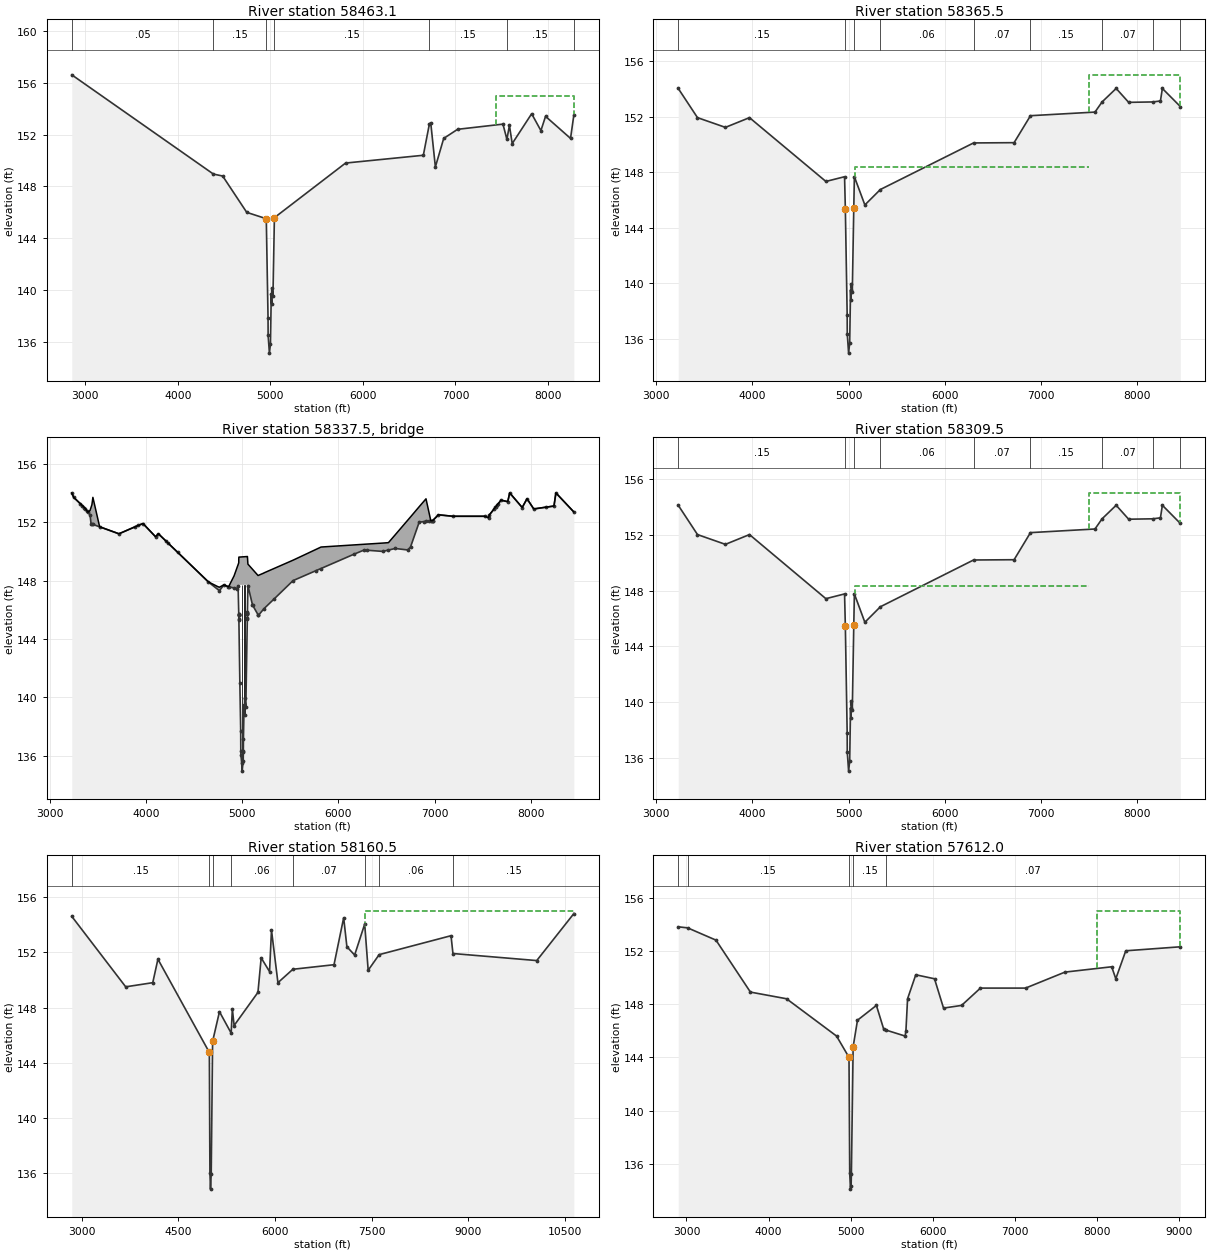
Type RM Length L Ch R = 1 ,58463.1 ,171.8,97.6,43.7
BEGIN DESCRIPTION:
Cross Section XS30.7
END DESCRIPTION:
XS GIS Cut Line= 3
       3046336.7     13951286.41      3047173.51     13949308.49
      3047019.55     13946036.22
#Sta/Elev= 30
    2855   156.6  4385.1  148.95    4485   148.8    4745     146  4956.2  145.51
  4975.1  137.89    4976  136.53  4989.9  135.15  5001.1  135.86  5010.1  139.67
  5014.8  138.96  5015.7  140.15  5028.2  139.54  5043.8  145.59  5812.7   149.8
  6652.7   150.4  6717.7   152.8  6732.7   152.9  6782.7   149.5  6872.7   151.7
  7022.7   152.4  7512.7   152.8  7555.2  151.63  7582.7   152.7  7612.7   151.3
  7822.7   153.6  7922.7   152.3  7972.7   153.4  8242.7   151.7  8278.5   153.5
#Mann= 7 ,-1 , 0
    2855     .05       0  4385.1     .15       0  4956.2     .08       0
  5043.8     .15       0  6717.7     .15       0  7555.2     .15       0
  8278.5      .2       0
#XS Ineff= 2 , 0
       0                    7440       0     155
Permanent Ineff=
       F       F
Bank Sta=4956.2,5043.8
XS Rating Curve= 0
Exp/Cntr=.5,.3

Type RM Length L Ch R = 1 ,58365.5 ,56,56,56
BEGIN DESCRIPTION:
Upstream Section of Bridge/Culvert/Weir
END DESCRIPTION:
XS GIS Cut Line= 4
      3047292.73      13951147.7      3047240.83      13949474.9
      3047216.03      13949307.6      3047067.28      13945984.9
#Sta/Elev= 30
  3231.2  154.02  3431.2  151.92  3721.2  151.22  3971.2  151.92  4764.7  147.33
  4958.7  147.67  4966.9  145.37  4985.9  137.72  4986.8  136.36  5000.7  134.98
  5011.9  135.69  5020.9   139.5  5025.6  138.79  5026.5  139.98    5039  139.37
  5054.5  145.42  5060.7  147.67  5169.6  145.64  5330.6  146.75  6298.4   150.1
  6719.6  150.12  6889.8  152.06  7559.6  152.32  7633.5  153.05  7779.6  154.02
  7909.6  153.02  8161.4  153.05  8239.6  153.12  8259.6  154.02    8446  152.72
#Mann= 9 ,-1 , 0
  3231.2     .15       0  4966.9     .08       0  5054.5     .15       0
  5330.6     .06       0  6298.4     .07       0  6889.8     .15       0
  7633.5     .07       0  8161.4     .15       0    8446      .2       0
#XS Ineff= 3 ,-1
  3231.2  4956.9  147.55  5064.5    7500  148.35    7500    8446     155
Permanent Ineff=
       F       F       F
Bank Sta=4966.9,5054.5
XS Rating Curve= 0
Exp/Cntr=.5,.3

Type RM Length L Ch R = 3 ,58337.5 ,,,
BEGIN DESCRIPTION:
HUFSMITH-KOHRVILLE
Structure ID: M100-00-00-11
Cross Section 58337.5
END DESCRIPTION:
Node Name=Hufsmith-Kohrvi
Bridge Culvert--1,0,-1,-1, 0
Deck Dist Width WeirC Skew NumUp NumDn MinLoCord MaxHiCord MaxSubmerge Is_Ogee
10,36,2.6,0, 57, 58, , , .95, 0, 1,1,,
  3231.2  3251.2  3361.2  3400.5  3421.2  3431.2  3440.5  3450.5  3520.5  3721.2
  3971.2  4101.2  4131.2  4651.2  4747.5  4764.7    4811  4860.1  4917.3  4948.7
  4958.7  4965.5 4965.61  4965.7  4966.9  5055.6  5055.7  5060.7    5166  5226.2
  5227.7  5529.6  5820.4  6269.6  6459.6  6520.4  6589.6  6719.6  6749.6  6839.6
  6910.4  6960.4  6979.6  7039.6  7189.6  7519.6  7559.6  7569.6  7689.6  7759.6
  7779.6  7909.6  7959.6  8029.6  8239.6  8259.6    8446
     154   153.7  153.01  152.68  152.81  153.01   153.2   153.7  151.69  151.21
  151.91  151.01  151.21  147.91  147.59  147.55  147.71  147.58  148.33  148.91
  149.09  149.22  149.37  149.49  149.61  149.65  149.65  149.13  148.35  148.52
  148.53   149.4   150.3  150.49  150.57   150.6  151.13  152.13  152.36  153.06
   153.6   152.1  152.11  152.51  152.41  152.41  152.31  152.51  153.51  153.41
  154.01  153.01  153.61  152.91  153.11  154.01   152.7
     154   153.7     153  152.67   152.5   151.9  151.88  151.85  151.68   151.2
   151.9     151   151.2   147.9  146.24  147.31   147.7  147.57   147.5  147.46
  147.65  145.74  145.71  147.59  147.71  147.71  145.84   145.8  145.66   145.7
  146.08     148  148.83   150.1     150  150.09   150.2   150.1   150.3     152
  152.05  152.09   152.1   152.5   152.4   152.4   152.3   152.5   153.5   153.4
     154     153   153.6   152.9   153.1     154   152.7
  3231.2  3251.2  3361.2  3400.5  3421.2  3431.2  3440.5  3450.5  3520.5  3721.2
  3971.2  4101.2  4131.2  4651.2  4747.5  4764.7    4811  4860.1  4917.3  4948.7
  4958.7  4965.5 4965.61  4965.7  4966.9  5055.6  5055.7  5060.7    5166  5226.2
  5227.7  5529.6  5820.4  6269.6  6459.6  6520.4  6589.6  6719.6  6749.6  6839.6
  6910.4  6940.4  6960.4  6979.6  7039.6  7189.6  7519.6  7559.6  7569.6  7689.6
  7759.6  7779.6  7909.6  7959.6  8029.6  8239.6  8259.6    8446
  154.12  153.82  153.12  152.79  152.81  153.01   153.2   153.7   151.8  151.32
  152.02  151.12  151.32  148.02  147.59  147.55  147.82  147.69  148.33  148.91
  149.09  149.22  149.37  149.49  149.61  149.65  149.65  149.13  148.35  148.52
  148.53   149.4   150.3  150.49  150.57   150.6  151.13  152.13  152.36  153.06
   153.6   152.7  152.21  152.22  152.62  152.52  152.52  152.42  152.62  153.62
  153.52  154.12  153.12  153.72  153.02  153.22  154.12  152.82
  154.12  153.82  153.12  152.79  152.62  152.02     152  151.97   151.8  151.32
  152.02  151.12  151.32  148.02  146.36  147.43  147.82  147.69  147.62  147.58
  147.77  145.86  145.83  147.71  147.71  147.71  145.96   145.8  145.78   145.7
   146.2  148.12  148.95  150.22  150.12  150.21  150.32  150.22  150.42  152.12
  152.17  152.19  152.21  152.22  152.62  152.52  152.52  152.42  152.62  153.62
  153.52  154.12  153.12  153.72  153.02  153.22  154.12  152.82
Pier Skew, UpSta & Num, DnSta & Num=  ,4995.8, 2 ,4995.8, 2 , 0 , 0 , 0 ,,
     1.2     1.2
  134.45  148.51
     1.2     1.2
  134.57  148.63
Pier Skew, UpSta & Num, DnSta & Num=  ,5025.6, 2 ,5025.6, 2 , 0 , 0 , 0 ,,
     1.2     1.2
  137.86  148.37
     1.2     1.2
  137.98  148.49
Abutment Skew #Up #Dn= , 2 , 2
  4965.5    4967
  147.59  145.32
  4965.5    4967
  147.71  145.44
BR Coef= 1 , 1 , 1 ,1.25, 0 ,,,.8,0,2,0,
WSPro=,,,, 1 ,,,, 0 ,,,, 0 ,,,,-1 ,-1 ,-1 , 0 , 0 , 0 , 0 , 0
BR U #Sta/Elev= 104
  3231.2     154  3251.2   153.7  3320.5  153.26  3340.5  153.13  3361.2     153
  3370.5  152.92  3390.5  152.76  3400.5  152.67  3421.2   152.5  3431.2   151.9
  3440.5  151.88  3450.5  151.85  3520.5  151.68  3721.2   151.2  3891.2   151.7
  3921.2   151.8  3971.2   151.9  4101.2     151  4131.2   151.2  4210.5   150.7
  4230.5  150.57  4330.5  149.94  4651.2   147.9  4764.7  147.31    4811   147.7
  4851.6  147.59  4860.1  147.57  4917.3   147.5  4948.7  147.46  4958.7  147.65
  4965.5  145.74 4965.61  145.71  4965.7  145.68  4965.8  145.66  4965.9  145.63
  4966.9  145.35    4967  145.32    4977     141  4985.9   137.7  4986.8  136.34
  4988.6  136.03  4995.7  135.53  5000.7  134.96  5011.9  135.67  5013.1  136.26
  5013.2  136.34  5014.2  137.19  5020.9  139.48  5025.6  138.77  5026.5  139.96
    5039  139.35  5054.5   145.4  5054.6  145.44  5055.3  145.69 5055.39  145.72
  5055.5  145.76  5055.6   145.8  5055.7  145.84  5060.7  147.65  5108.2  146.34
  5109.5  146.32    5166  145.66  5169.6  145.62  5227.7  146.08  5330.6  146.73
  5529.6     148  5770.4  148.69  5820.4  148.83  6159.6   149.8  6269.6   150.1
  6298.4  150.08  6459.6     150  6520.4  150.09  6589.6   150.2  6719.6   150.1
  6749.6   150.3  6839.6     152  6889.8  152.04  6910.4  152.05  6940.4  152.07
  6960.4  152.09  6970.4  152.09  6979.6   152.1  6980.4  152.11  7039.6   152.5
  7189.6   152.4  7519.6   152.4  7559.6   152.3  7569.6   152.5  7620.4  152.92
  7630.4  153.01  7633.5  153.03  7650.4  153.17  7660.4  153.26  7689.6   153.5
  7759.6   153.4  7779.6     154  7909.6     153  7959.6   153.6  8029.6   152.9
  8161.4  153.03  8239.6   153.1  8259.6     154    8446   152.7
BR U #Mann= 8
  3231.2     .15  4966.9     .07  5054.5     .15  5330.6     .06  6298.4     .07
  6889.8     .15  7633.5     .07  8161.4     .15
BR U Banks=4966.9,5054.5
BR D #Sta/Elev= 104
  3231.2  154.12  3251.2  153.82  3320.5  153.38  3340.5  153.25  3361.2  153.12
  3370.5  153.04  3390.5  152.88  3400.5  152.79  3421.2  152.62  3431.2  152.02
  3440.5     152  3450.5  151.97  3520.5   151.8  3721.2  151.32  3891.2  151.82
  3921.2  151.92  3971.2  152.02  4101.2  151.12  4131.2  151.32  4210.5  150.82
  4230.5  150.69  4330.5  150.06  4651.2  148.02  4764.7  147.43    4811  147.82
  4851.6  147.71  4860.1  147.69  4917.3  147.62  4948.7  147.58  4958.7  147.77
  4965.5  145.86 4965.61  145.83  4965.7   145.8  4965.8  145.78  4965.9  145.75
  4966.9  145.47    4967  145.44    4977  141.12  4985.9  137.82  4986.8  136.46
  4988.6  136.15  4995.7  135.65  5000.7  135.08  5011.9  135.79  5013.1  136.38
  5013.2  136.46  5014.2  137.31  5020.9   139.6  5025.6  138.89  5026.5  140.08
    5039  139.47  5054.5  145.52  5054.6  145.56  5055.3  145.81 5055.39  145.84
  5055.5  145.88  5055.6  145.92  5055.7  145.96  5060.7  147.77  5108.2  146.46
  5109.5  146.44    5166  145.78  5169.6  145.74  5227.7   146.2  5330.6  146.85
  5529.6  148.12  5770.4  148.81  5820.4  148.95  6159.6  149.92  6269.6  150.22
  6298.4   150.2  6459.6  150.12  6520.4  150.21  6589.6  150.32  6719.6  150.22
  6749.6  150.42  6839.6  152.12  6889.8  152.16  6910.4  152.17  6940.4  152.19
  6960.4  152.21  6970.4  152.21  6979.6  152.22  6980.4  152.23  7039.6  152.62
  7189.6  152.52  7519.6  152.52  7559.6  152.42  7569.6  152.62  7620.4  153.04
  7630.4  153.13  7633.5  153.15  7650.4  153.29  7660.4  153.38  7689.6  153.62
  7759.6  153.52  7779.6  154.12  7909.6  153.12  7959.6  153.72  8029.6  153.02
  8161.4  153.15  8239.6  153.22  8259.6  154.12    8446  152.82
BR D #Mann= 8
  3231.2     .15  4966.9     .07  5054.5     .15  5330.6     .06  6298.4     .07
  6889.8     .15  7633.5     .07  8161.4     .15
BR D Banks=4966.9,5054.5
BC Design=,, 0 ,, 0 ,,,,,,
BC HTab HWMax=154.02

Type RM Length L Ch R = 1 ,58309.5 ,127.1,149,183.1
BEGIN DESCRIPTION:
Downstream Section of Bridge/Culvert/Weir
END DESCRIPTION:
XS GIS Cut Line= 4
      3047343.04      13951059.7      3047302.99      13949471.4
      3047268.68      13949286.2      3047081.48      13945945.3
#Sta/Elev= 30
  3231.2  154.11  3431.2  152.01  3721.2  151.31  3971.2  152.01  4764.7  147.42
  4958.7  147.76  4966.9  145.46  4985.9  137.81  4986.8  136.45  5000.7  135.07
  5011.9  135.78  5020.9  139.59  5025.6  138.88  5026.5  140.07    5039  139.46
  5054.5  145.51  5060.7  147.76  5169.6  145.73  5330.6  146.84  6298.4  150.19
  6719.6  150.21  6889.8  152.15  7559.6  152.41  7633.5  153.14  7779.6  154.11
  7909.6  153.11  8161.4  153.14  8239.6  153.21  8259.6  154.11    8446  152.81
#Mann= 9 ,-1 , 0
  3231.2     .15       0  4966.9     .08       0  5054.5     .15       0
  5330.6     .06       0  6298.4     .07       0  6889.8     .15       0
  7633.5     .07       0  8161.4     .15       0    8446      .2       0
#XS Ineff= 3 ,-1
  3231.2    4955  147.36    5065    7500  148.35    7500    8446     155
Permanent Ineff=
       F       F       F
Bank Sta=4966.9,5054.5
XS Rating Curve= 0
Exp/Cntr=.5,.3

Type RM Length L Ch R = 1 ,58160.5 ,483.79,548.5,532.95
BEGIN DESCRIPTION:
Cross Section XS30.5
END DESCRIPTION:
XS GIS Cut Line= 5
      3047429.56     13951531.72      3047437.28     13951075.18
      3047429.37     13949033.14      3047413.48     13946077.61
      3047411.46     13943742.03
#Sta/Elev= 30
  2846.5   154.6  3683.1   149.5  4103.1   149.8  4183.1   151.5  4981.1  144.75
  4989.9  136.04    4999  134.86    5010  135.96  5031.6  145.55    5138   147.7
  5319.6  146.15    5338   147.9  5365.2   146.7  5735.2   149.1  5785.2   151.6
  5915.2   150.6  5945.2   153.6  6045.2   149.8  6276.8  150.77  6915.2   151.1
  7065.2   154.5  7115.2   152.4  7235.2   151.8  7391.3  154.04  7445.2   150.7
  7615.9  151.83  8730.8   153.2  8760.5  151.91 10060.8   151.4 10636.4   154.8
#Mann= 8 ,-1 , 0
  2846.5     .15       0  4981.1     .08       0  5031.6     .15       0
  5319.6     .06       0  6276.8     .07       0  7391.3     .12       0
  7615.9     .06       0  8760.5     .15       0
#XS Ineff= 2 , 0
       0                    7395       0     155
Permanent Ineff=
       F       F
#Block Obstruct= 2 , 0
       0                    9850       0   152.3
Bank Sta=4981.1,5031.6
XS Rating Curve= 0
Exp/Cntr=.3,.1

Type RM Length L Ch R = 1 ,57612.0 ,1065.56,2091.2,2071.43
BEGIN DESCRIPTION:
Cross Section 57612.0
Cross Section XS30
END DESCRIPTION:
XS GIS Cut Line= 4
      3047758.43      13951269.6      3047928.96      13948859.9
      3047938.33      13948258.5      3050371.85      13946307.5
#Sta/Elev= 30
  2899.4   153.8  3014.6  153.72  3359.4   152.8  3779.4   148.9  4219.4   148.4
  4829.4   145.6  4981.1     144  4989.9  135.29    4999  134.11  5006.9  134.34
    5010  135.21  5031.6   144.8  5084.6  146.79  5315.1   147.9  5405.1   146.1
  5431.6  146.05  5665.1   145.6  5675.1     146  5695.1   148.4  5795.1   150.2
  6023.4   149.9  6133.4   147.7  6353.4   147.9  6583.4   149.2  7133.4   149.2
  7613.4   150.4  8183.4   150.8  8233.4   149.9    8355     152  9019.9   152.3
#Mann= 5 ,-1 , 0
  2899.4      .1       0  3014.6     .15       0  4981.1     .08       0
  5031.6     .15       0  5431.6     .07       0
#XS Ineff= 2 ,-1
    5860    8000   150.1    8000  9019.9     155
Permanent Ineff=
       F       F
Bank Sta=4981.1,5031.6
XS Rating Curve= 0
Exp/Cntr=.3,.1