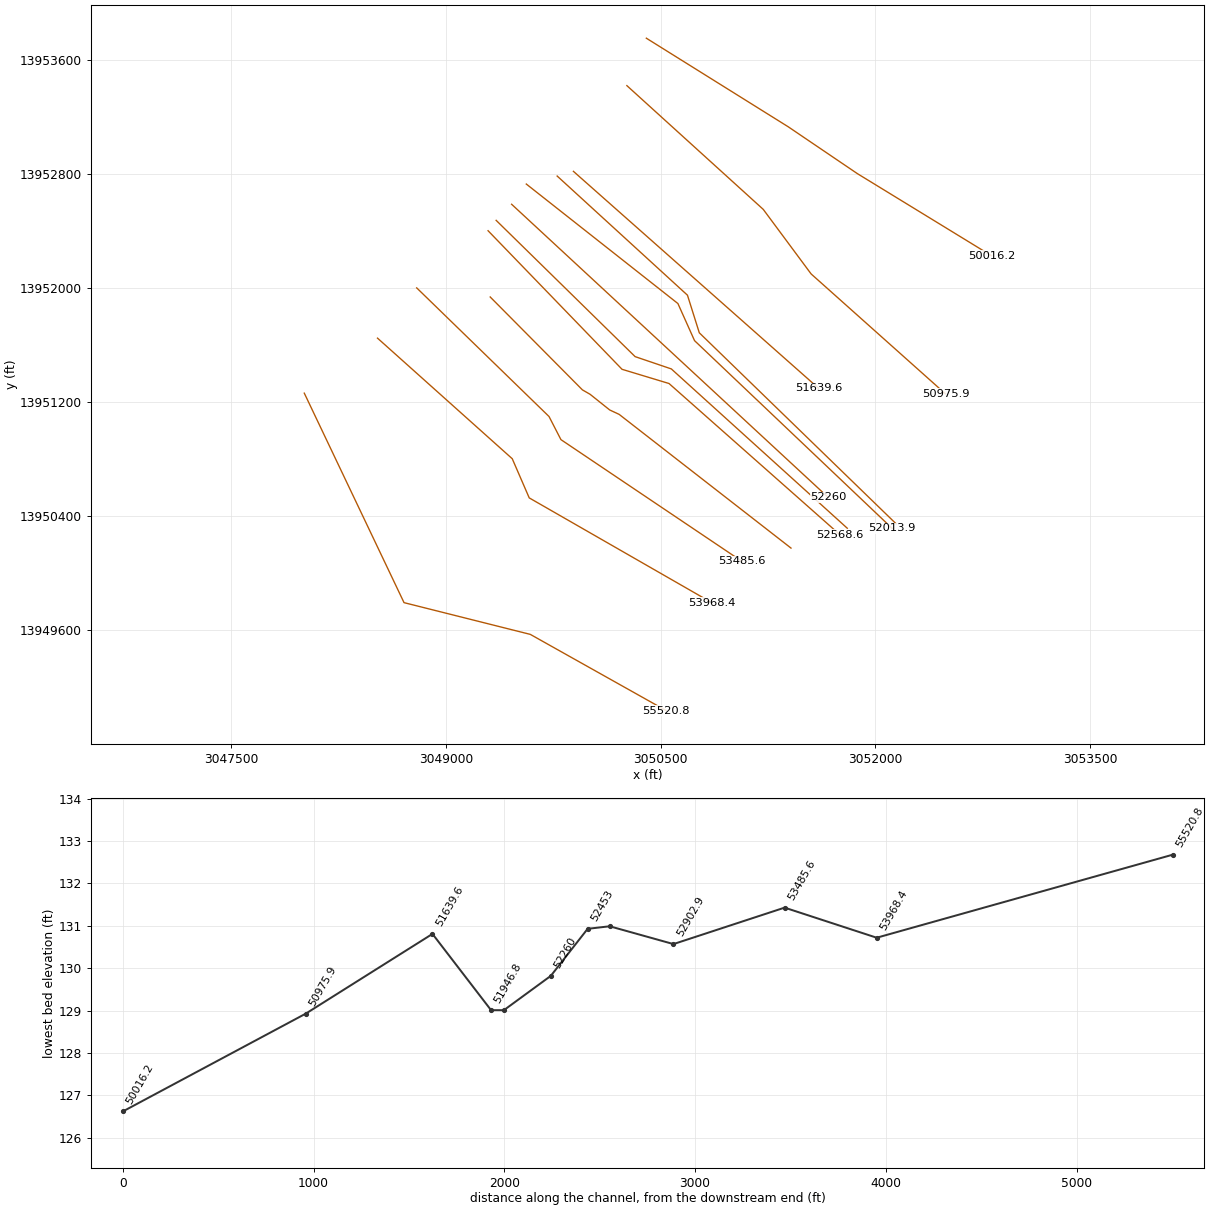
HEC-RAS study M100-00-00.prj: M100-00-00

--- M100-00-00.g01 (geometry) --- (continued)

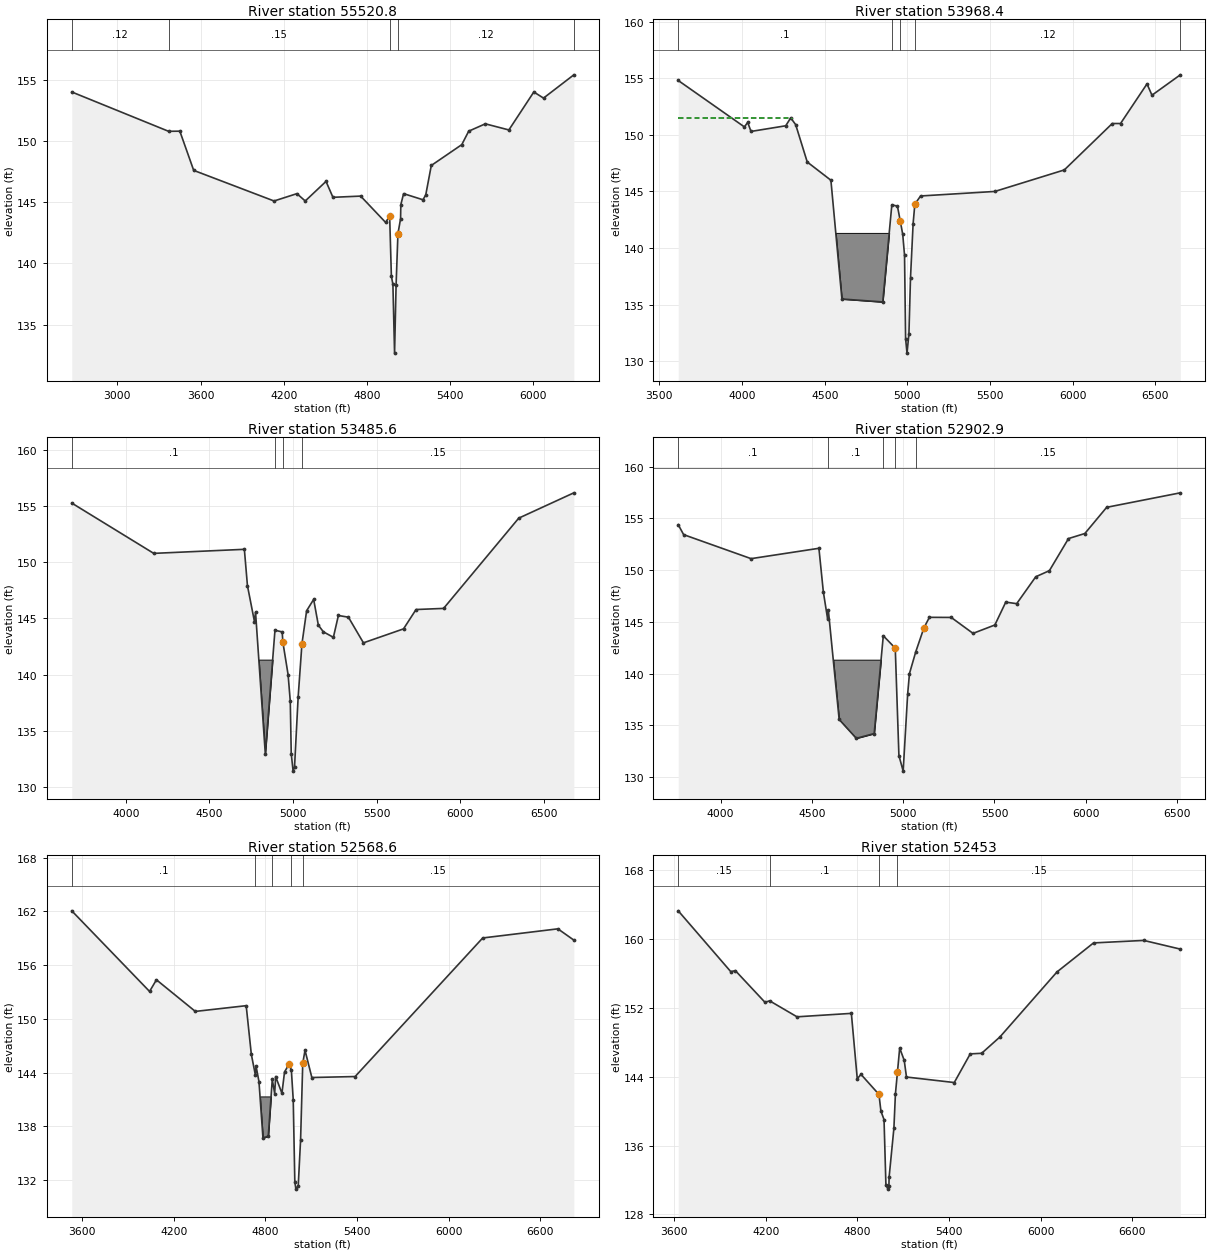
Type RM Length L Ch R = 1 ,55520.8 ,1630,1552.4,1530
BEGIN DESCRIPTION:
Cross Section 55520.8
Cross Section XS29
END DESCRIPTION:
XS GIS Cut Line= 4
      3048010.52      13951262.2      3048707.47      13949794.1
      3049589.77      13949571.7      3050538.81      13949037.9
#Sta/Elev= 30
  2670.6     154  3369.2  150.79  3450.6   150.8  3550.6   147.6  4130.6   145.1
  4295.7   145.7  4355.7   145.1  4505.7   146.7  4555.7   145.4  4755.7   145.5
  4935.9  143.35    4965  143.87  4977.5  138.96  4988.5   138.3  5000.5  132.68
  5011.5  138.25  5024.8  142.43  5043.9  143.65  5045.7   144.8  5065.7   145.7
  5205.6   145.2  5225.6   145.6  5265.6     148  5485.6   149.7  5535.6   150.8
  5655.6   151.4  5825.6   150.9  6005.6     154  6075.6   153.5  6294.5   155.4
#Mann= 5 ,-1 , 0
  2670.6     .12       0  3369.2     .15       0    4965     .08       0
  5024.8     .12       0  6294.5      .2       0
Bank Sta=4965,5024.8
XS Rating Curve= 0
Exp/Cntr=.3,.1

Type RM Length L Ch R = 1 ,53968.4 ,416.3,482.8,415.5
BEGIN DESCRIPTION:
Cross Section 53968.4 Albury Trails LOMR - As-Built Cut and Fill added
END DESCRIPTION:
XS GIS Cut Line= 4
      3048522.11      13951647.7      3049463.73      13950802.5
      3049582.36      13950528.1      3050857.62      13949794.1
#Sta/Elev= 30
  3614.5   154.8  4014.5   150.7  4034.5   151.1  4054.5   150.3  4264.5   150.8
  4294.5   151.5  4324.5   150.9  4394.5   147.6 4537.55  145.99    4604   135.5
    4851  135.24    4906  143.82  4939.8   143.7  4956.5  142.43  4971.9   141.2
  4982.7  139.37  4989.2     132  4997.7  130.72  5009.2   132.4  5018.8  137.37
  5034.6  142.16  5045.1  143.88  5079.8   144.6  5528.7     145  5948.7   146.9
  6238.7     151  6288.7     151  6448.7   154.5  6478.7   153.5  6650.1   155.3
#Mann= 5 ,-1 , 0
  3614.5      .1       0    4906     .12       0  4956.5     .08       0
  5045.1     .12       0  6650.1      .2       0
#XS Ineff= 1 ,-1
  3614.5    4300   151.5
Permanent Ineff=
       F
#Block Obstruct= 1 ,-1
    4560 4911.58  141.34
Bank Sta=4956.5,5045.1
XS Rating Curve= 0
Exp/Cntr=.3,.1

Type RM Length L Ch R = 1 ,53485.6 ,310.1,582.7,328.5
BEGIN DESCRIPTION:
Added Section -  Albury Trails LOMR - As-Built Cut and Fill added
END DESCRIPTION:
XS GIS Cut Line= 4
 3048796.096486113951999.7401988 3049720.541487613951098.5471193
 3049803.840861713950936.5024959  3051069.39476113950082.8919984
#Sta/Elev= 30
 3677.53  155.25 4167.23  150.78 4708.73  151.14 4727.12  147.91 4769.21  144.71
 4775.51  145.56  4833.8  132.99 4891.58  143.95 4934.68   143.8 4938.88  142.88
 4970.04     140    4983  137.65 4988.84  132.98    5000  131.43 5008.53   131.8
 5030.04     138 5052.65  142.73 5080.68  145.68 5122.73  146.69 5150.76   144.4
 5180.69  143.81 5240.55  143.32 5270.48  145.26 5330.35  145.11 5420.14  142.83
  5659.6  144.07 5734.43  145.79 5899.05  145.89 6348.03  153.91 6677.28  156.16
#Mann= 4 ,-1 , 0
 3677.53      .1       0 4891.58     .12       0 4938.88     .08       0
 5052.65     .15       0
#Block Obstruct= 1 ,-1
    4788    4886  141.34
Bank Sta=4938.88,5052.65
XS Rating Curve= 0
Exp/Cntr=.3,.1

Type RM Length L Ch R = 1 ,52902.9 ,306.1,334.3,374.7
BEGIN DESCRIPTION:
Added Section -  Albury Trails LOMR - As-Built Cut and Fill added
END DESCRIPTION:
XS GIS Cut Line= 6
  3049309.64237513951936.0795649 3049954.008540413951285.0470743
 3050007.5172916 13951254.246611 3050144.749956813951144.2494557
 3050210.441426413951113.5677585 3051411.461990313950176.3793442
#Sta/Elev= 30
 3768.21  154.38 3797.76  153.42 4167.11   151.1 4538.61   152.1 4562.78   147.9
 4586.36  145.26 4590.31  146.11 4649.49  135.56 4743.23  133.74 4841.27   134.2
 4891.19  143.65 4956.69  142.45  4976.7  132.08    5000  130.57 5024.54     138
 5034.54     140    5069   142.1 5113.81  144.42 5143.68  145.43 5263.16  145.42
 5382.65  143.88 5502.13  144.69 5561.87   146.9 5621.61  146.75 5726.16  149.35
 5800.84  149.94 5905.38  153.04    5995  153.53 6114.48  156.06 6517.74  157.46
#Mann= 5 ,-1 , 0
 3768.21      .1       0 4586.36      .1       0 4891.19     .12       0
 4956.69     .08       0    5069     .15       0
#Block Obstruct= 1 ,-1
    4590    4891  141.34
Bank Sta=4956.69,5113.81
XS Rating Curve= 0
Exp/Cntr=.3,.1

Type RM Length L Ch R = 1 ,52568.6 ,112.2,115.6,121.8
BEGIN DESCRIPTION:
Added Section -  Albury Trails LOMR - As-Built Cut and Fill added
END DESCRIPTION:
XS GIS Cut Line= 4
 3049294.695226513952400.4168909 3050230.885939413951429.2282164
 3050559.049981213951329.7481004 3051753.5295476  13950269.86669
#Sta/Elev= 30
 3531.84  162.06 4041.44  153.06 4086.41  154.36 4341.21  150.83 4674.37  151.47
 4707.92  146.05 4734.52  143.73  4739.1  144.71    4758     143 4784.15  136.72
 4818.91  136.88 4845.15  143.23 4861.01  141.66 4867.29  143.56 4908.52  141.69
 4925.52  144.07 4955.34  144.95 4970.24  144.27 4982.52  140.97 4992.91  131.81
    5000  130.99 5015.27  131.38 5030.68   136.5 5044.79  145.03  5059.7  146.49
 5104.43  143.45 5387.87  143.56 6223.64  159.03 6716.15  160.05 6820.62  158.79
#Mann= 5 ,-1 , 0
 3531.84      .1       0 4734.52      .1       0 4845.15     .12       0
 4970.24     .08       0 5044.79     .15       0
#Block Obstruct= 1 ,-1
    4758    4845  141.34
Bank Sta=4955.34,5044.79
XS Rating Curve= 0
Exp/Cntr=.3,.1

Type RM Length L Ch R = 1 ,52453   ,180.6,193,169.81
BEGIN DESCRIPTION:
Added Section -  Albury Trails LOMR - As-Built Cut and Fill added
END DESCRIPTION:
XS GIS Cut Line= 4
 3049351.266963713952473.0492915 3050322.335559613951518.0410309
 3050575.230723113951431.9847726 3051804.587844513950315.5312968
#Sta/Elev= 30
 3625.96  163.28  3970.2  156.21 4000.13  156.33  4194.7  152.64 4224.64  152.82
 4404.24  150.96 4760.33  151.36 4798.97  143.76 4823.31  144.27 4941.09  141.94
 4954.04     140  4974.4  139.01 4986.72  131.44    5000  130.93 5006.34  131.26
 5007.61  132.31 5039.04     138 5049.04     142 5062.15  144.49    5077  147.33
 5106.68   145.9 5121.52  143.96 5434.62  143.32 5539.34  146.65 5614.15  146.72
 5733.83  148.62 6107.86  156.18 6347.23  159.55 6676.37  159.84 6915.75  158.83
#Mann= 4 ,-1 , 0
 3625.96     .15       0 4224.64      .1       0 4941.09     .08       0
 5062.15     .15       0
Bank Sta=4941.09,5062.15
XS Rating Curve= 0
Exp/Cntr=.3,.1

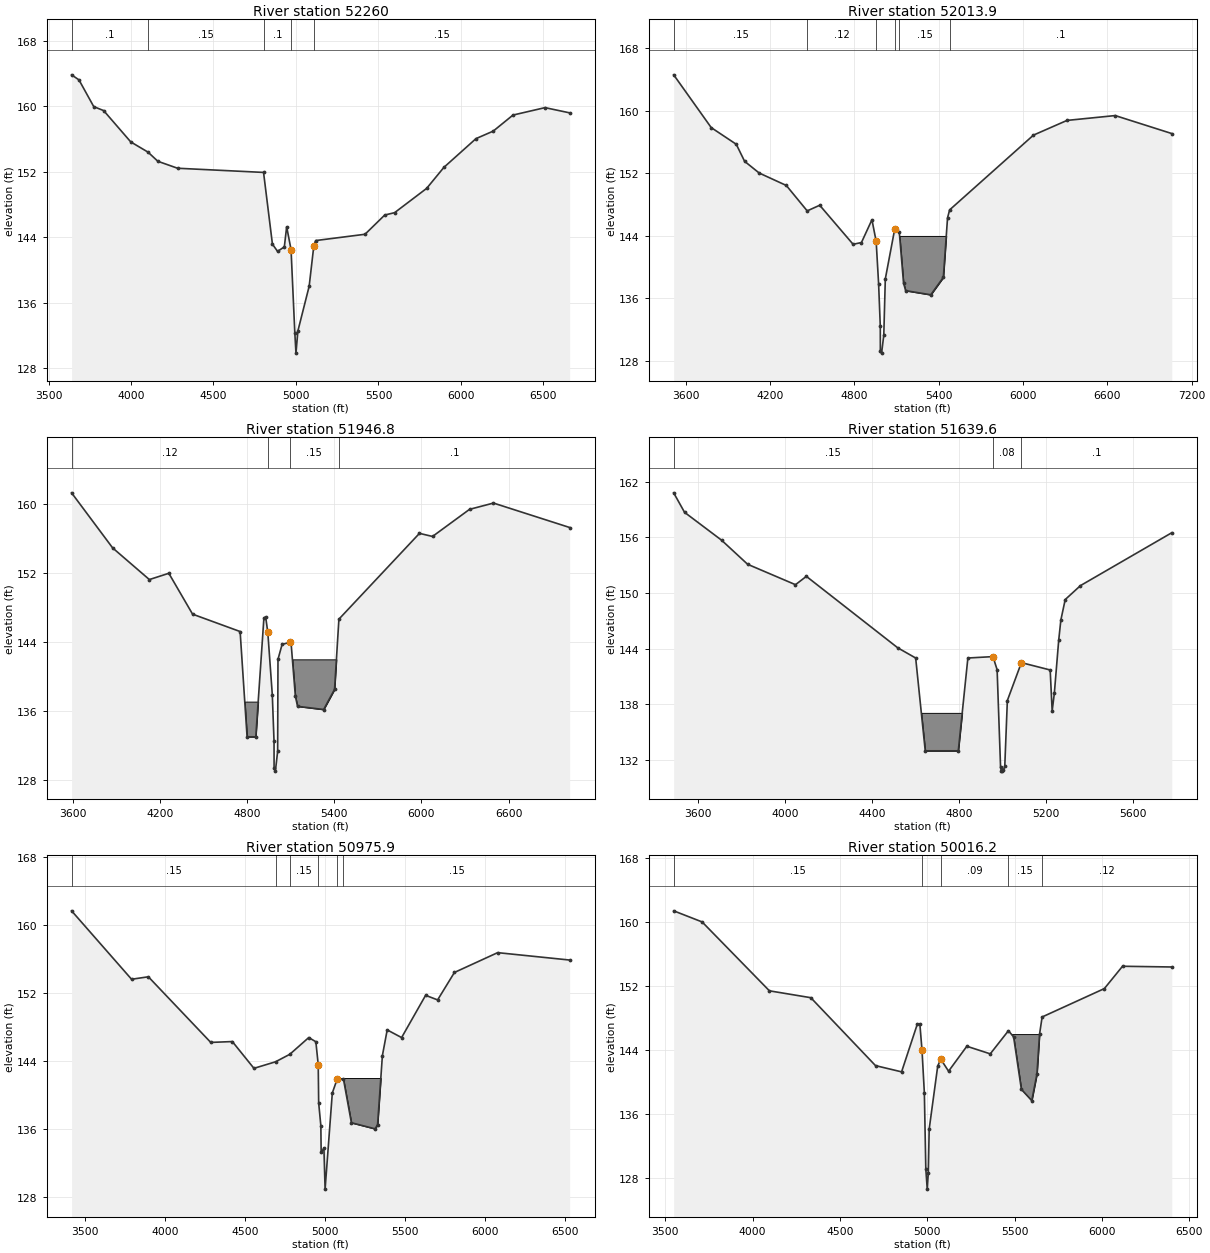
Type RM Length L Ch R = 1 ,52260   ,245.86,246.1,178.6
BEGIN DESCRIPTION:
Added Section -  Albury Trails LOMR - As-Built Cut and Fill added
END DESCRIPTION:
XS GIS Cut Line= 2
 3049459.256577113952585.8331867 3051671.907991713950530.9117716
#Sta/Elev= 30
 3639.64  163.84 3684.49  163.22 3774.18  159.95 3833.98  159.47 3998.42  155.64
 4103.06  154.39 4162.85  153.27 4282.45  152.42 4803.48  151.91  4857.3  143.14
 4888.38  142.26 4929.52  142.81  4943.6  145.27 4970.14  142.48 4992.94  132.34
    5000  129.82 5011.73  132.54 5080.04     138 5108.11  142.92 5119.59  143.58
 5418.57  144.35 5538.16   146.7 5597.96  146.99 5792.29  149.96 5896.93  152.53
 6091.27  156.04 6195.91  156.96 6315.51  158.92 6509.84  159.83 6659.33  159.19
#Mann= 5 ,-1 , 0
 3639.64      .1       0 4103.06     .15       0 4803.48      .1       0
 4970.14     .08       0 5108.11     .15       0
Bank Sta=4970.14,5108.11
XS Rating Curve= 0
Exp/Cntr=.3,.1

Type RM Length L Ch R = 1 ,52013.9 ,128.9,67.1,58.6
BEGIN DESCRIPTION:
Added Section - Albury LOMR
END DESCRIPTION:
XS GIS Cut Line= 4
 3049561.852828613952727.5021947 3050621.255237413951890.0724391
 3050737.395096913951630.2258459 3052118.848698913950313.9732291
#Sta/Elev= 30
    3515   164.6 3782.12  157.85 3960.19  155.72 4019.55  153.54 4123.43  152.04
 4316.35  150.45 4464.74   147.2 4553.78  147.92 4791.22  142.93 4850.58  143.15
 4925.34  146.07  4955.3  143.31  4972.7   137.9  4984.7  132.46  4985.1  129.34
 4993.94  129.01  5009.6  131.31 5020.43   138.5 5087.96  144.93 5120.08  144.44
 5150.04  137.99 5164.94     137 5343.83  136.47 5433.27   138.7 5463.09  146.31
 5477.99  147.33 6074.28  156.89  6312.8  158.77 6655.67  159.39 7058.17  157.09
#Mann= 6 ,-1 , 0
    3515     .15       0 4464.74     .12       0  4955.3     .08       0
 5087.96      .1       0 5120.08     .15       0 5477.99      .1       0
#Block Obstruct= 1 ,-1
    5120    5463     144
Bank Sta=4955.3,5087.96
XS Rating Curve= 0
Exp/Cntr=.3,.1

Type RM Length L Ch R = 1 ,51946.8 ,119.5,307.2,300
BEGIN DESCRIPTION:
Added Section - Albury LOMR
END DESCRIPTION:
XS GIS Cut Line= 4
 3049777.472804213952783.7146807 3050688.014618313951948.5618234
 3050770.714912213951685.1194369 3052146.295822413950346.2143064
#Sta/Elev= 30
    3590  161.35 3872.84  154.95  4125.9  151.27 4259.87     152 4423.62  147.25
 4751.11  145.23    4799     133    4859     133    4915  146.83 4927.27   146.9
  4941.8  145.13  4972.7   137.9  4984.7  132.464985.103  129.344993.941  129.01
  5009.6  131.31  5011.9     142 5040.17  143.73 5091.24  143.97 5101.66  143.99
 5131.65  137.71 5146.65  136.54 5326.61  136.17  5401.6  138.51 5431.59  146.67
 5986.48  156.64 6076.46  156.28 6331.41  159.43 6496.38  160.16 7021.28  157.32
#Mann= 4 ,-1 , 0
    3590     .12       0  4941.8     .08       0 5091.24     .15       0
 5431.59      .1       0
#Block Obstruct= 2 ,-1
    5101    5416     142    4750    4915  137.09
Bank Sta=4941.8,5091.24
XS Rating Curve= 0
Exp/Cntr=.3,.1

Type RM Length L Ch R = 1 ,51639.6 ,712.2,663.7,569.2
BEGIN DESCRIPTION:
Cross Section 51639.6
END DESCRIPTION:
XS GIS Cut Line= 2
      3049891.12      13952816.5      3051603.84      13951296.6
#Sta/Elev= 28
  3487.5   160.8  3537.5   158.7  3707.5   155.7  3827.5   153.1  4047.5   150.9
  4097.5   151.8  4517.5   144.1    4600     143    4644     133    4796     133
    4840     143  4955.3  143.15  4974.4  141.74  4990.3  131.22  4993.9  130.81
    4999  130.86  5003.5  130.92  5009.6  131.31  5021.5  138.42    5086   142.5
  5218.3  141.71  5227.5   137.3  5237.5   139.2  5257.5   144.9  5267.5   147.1
  5287.5   149.3  5357.5   150.8  5777.4   156.5
#Mann= 3 ,-1 , 0
  3487.5     .15       0  4955.3     .08       0    5086      .1       0
#XS Ineff= 2 , 0
       0                    5086       0   142.5
Permanent Ineff=
       F       F
#Block Obstruct= 1 ,-1
    4600    4840  137.09
Bank Sta=4955.3,5086
XS Rating Curve= 0
Exp/Cntr=.3,.1

Type RM Length L Ch R = 1 ,50975.9 ,535.66,959.7,811.5
BEGIN DESCRIPTION:
Added Section - Albury LOMR End 80' Clearing Strip
END DESCRIPTION:
XS GIS Cut Line= 4
 3050264.685084413953417.1504217 3051217.655619413952549.8765657
 3051551.932509913952097.7819974 3052490.280698813951257.8348584
#Sta/Elev= 30
 3417.04  161.67 3791.61  153.62 3896.49  153.91 4286.05  146.19  4420.9  146.29
 4555.74  143.14 4690.59  143.91 4779.55  144.79 4897.92  146.76 4942.31  146.27
 4957.11  143.58 4959.96  139.06  4973.5   136.4 4975.44  133.24 4992.64  133.76
 5000.03  128.93 5045.07  140.24 5075.48  141.88 5114.83  141.85 5164.25  136.74
  5312.8  136.02  5327.8  136.53 5357.78  144.64 5387.77  147.66 5477.72  146.76
 5627.65  151.73 5702.61  151.19 5807.55  154.42 6077.42  156.75 6527.19  155.88
#Mann= 6 ,-1 , 0
 3417.04     .15       0 4690.59     .08       0 4779.55     .15       0
 4957.11     .08       0 5075.48     .12       0 5114.83     .15       0
#Block Obstruct= 1 ,-1
 5090.27 5357.78     142
Bank Sta=4957.11,5075.48
XS Rating Curve= 0
Exp/Cntr=.3,.1

Type RM Length L Ch R = 1 ,50016.2 ,664.6,775.3,631.2
BEGIN DESCRIPTION:
Added Section - Albury LOMR 80' Clearing Strip Added
END DESCRIPTION:
XS GIS Cut Line= 4
  3050400.62805413953749.5861085 3051392.747460813953128.3527709
 3051874.899055513952800.7369564 3052811.385371513952225.8640904
#Sta/Elev= 30
 3548.04  161.41 3711.03  160.02 4096.28  151.41 4333.36  150.55 4703.79  142.06
 4853.13  141.28 4942.81  147.22 4957.76  147.27 4970.04     144 4970.05     144
 4983.51  138.66 4991.87  129.14    5000  126.62 5006.05  128.61 5011.18  134.13
 5060.04     142 5077.33  142.87 5122.17  141.36  5226.8  144.48 5360.93  143.53
 5464.88  146.42 5494.58  145.66 5539.12  139.09 5598.52  137.68 5628.22  141.01
 5643.07  145.97 5657.92  148.14 6014.31  151.69 6118.25  154.48 6400.39  154.39
#Mann= 5 ,-1 , 0
 3548.04     .15       0 4970.04     .08       0 5077.33     .09       0
 5464.88     .15       0 5657.92     .12       0
#Block Obstruct= 1 ,-1
 5479.73 5657.92     146
Bank Sta=4970.05,5077.33
XS Rating Curve= 0
Exp/Cntr=.3,.1