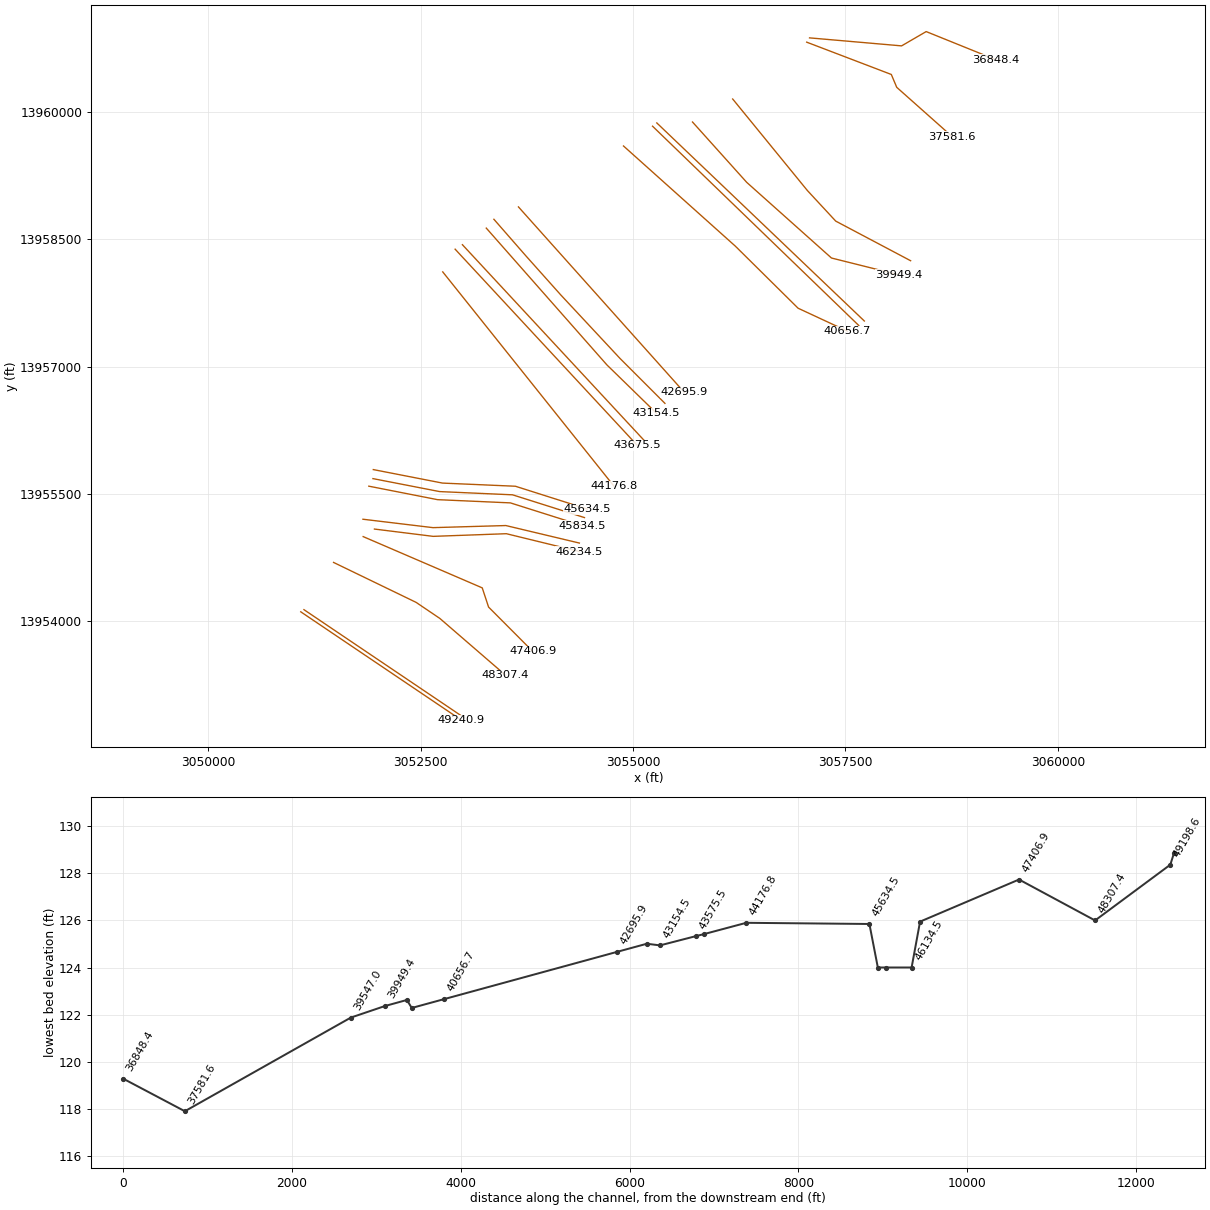
HEC-RAS study M100-00-00.prj: M100-00-00

--- M100-00-00.g01 (geometry) --- (continued)

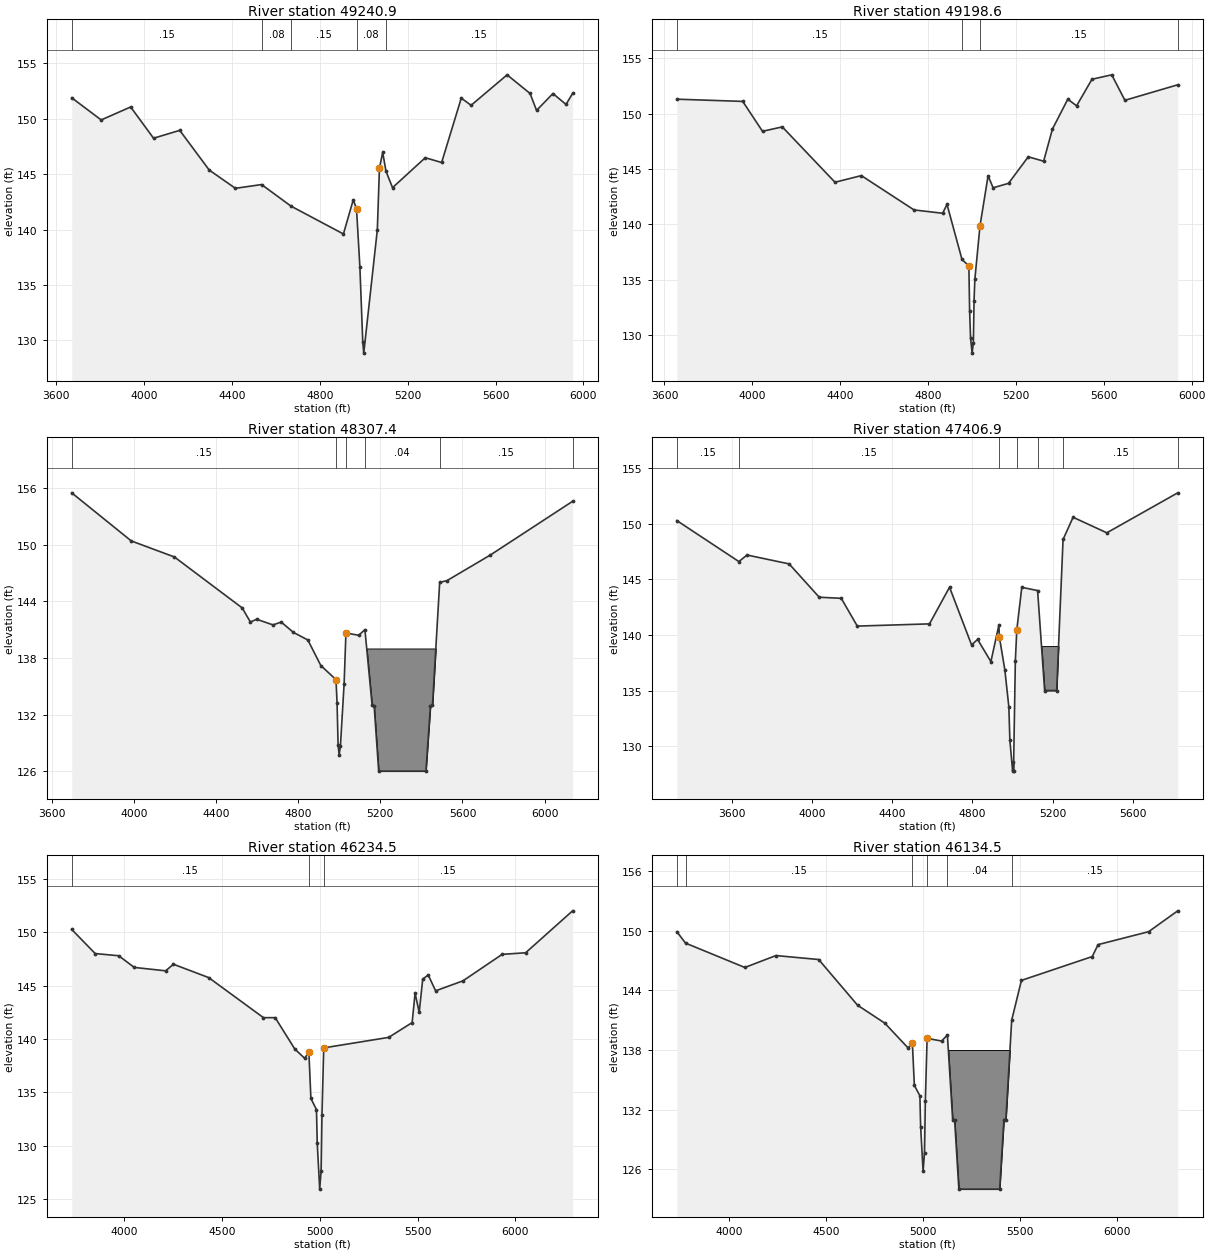
Type RM Length L Ch R = 1 ,49240.9 ,48.2,42.3,41.17
BEGIN DESCRIPTION:
Added Section - Albury LOMR Begin 80' Clearing Strip
END DESCRIPTION:
XS GIS Cut Line= 2
  3051086.992823 13954113.547979 3052977.652755513952838.3477735
#Sta/Elev= 30
 3670.29  151.89 3804.44  149.89 3938.59  151.06 4042.92  148.24 4162.17  148.95
 4296.31  145.37 4415.55  143.72  4534.8  144.06 4668.94  142.11 4907.43   139.6
 4952.14  142.68 4967.05  141.87 4982.29  136.66 4995.54  129.83    5000  128.85
 5061.89     140 5071.39  145.54 5086.29  146.96  5101.2  145.26 5131.01  143.78
 5280.06  146.48 5354.59  146.05 5444.02  151.86 5488.73  151.21 5652.69  153.96
 5757.03  152.28 5786.84  150.75 5861.37  152.27 5920.99  151.29  5950.8  152.28
#Mann= 5 ,-1 , 0
 3670.29     .15       0  4534.8     .08       0 4668.94     .15       0
 4967.05     .08       0  5101.2     .15       0
Bank Sta=4967.05,5071.39
XS Rating Curve= 0
Exp/Cntr=.3,.1

Type RM Length L Ch R = 1 ,49198.6 ,807.2,891.2,792.27
BEGIN DESCRIPTION:
Cross Section 49198.6
Cross Section XS26
END DESCRIPTION:
XS GIS Cut Line= 2
      3051124.54      13954138.9       3053015.2      13952863.7
#Sta/Elev= 30
  3656.3   151.3  3956.3   151.1  4046.3   148.4  4136.3   148.8  4376.3   143.8
  4496.3   144.4  4736.3   141.3  4866.3     141  4886.3   141.8  4954.5  136.83
  4985.9  136.24  4989.2  132.21  4993.5  129.74  5000.6  128.37  5006.4   129.3
  5009.4   133.1  5013.1  135.04  5036.5  139.86  5073.3  144.38  5096.3   143.3
  5166.3   143.7  5256.3   146.1  5326.3   145.7  5366.3   148.6  5436.3   151.3
  5476.3   150.7  5546.3   153.1  5636.3   153.5  5696.3   151.2  5936.8   152.6
#Mann= 4 ,-1 , 0
  3656.3     .15       0  4954.5     .08       0  5036.5     .15       0
  5936.8      .2       0
Bank Sta=4985.9,5036.5
XS Rating Curve= 0
Exp/Cntr=.3,.1

Type RM Length L Ch R = 1 ,48307.4 ,628.49,900.5,509.05
BEGIN DESCRIPTION:
Cross Section 48307.4
Cross Section XS25
END DESCRIPTION:
XS GIS Cut Line= 4
      3051473.01       13954695.      3052444.83      13954224.8
      3052724.61      13954035.4      3053497.13      13953367.8
#Sta/Elev= 30
  3697.6   155.5  3987.6   150.4  4197.6   148.7  4527.6   143.3  4567.6   141.8
  4597.6   142.1  4677.6   141.5  4717.6   141.8  4777.2   140.7  4847.2   139.9
  4910.4  137.19  4984.2   135.7  4989.4  133.21  4994.4  128.79  4999.5  127.72
  5005.8  128.67  5023.7  135.25  5032.6  140.64    5095   140.4    5125     141
    5160     133    5170   132.9    5192     126    5422     126    5444   132.9
    5454     133    5489     146  5525.1   146.2  5735.1   148.9    6136   154.6
#Mann= 6 ,-1 , 0
  3697.6     .15       0  4984.2     .08       0  5032.6     .15       0
    5125     .04       0    5489     .15       0    6136      .2       0
#Block Obstruct= 1 ,-1
    5125    5489     139
Bank Sta=4984.2,5032.6
XS Rating Curve= 0
Exp/Cntr=.3,.1

Type RM Length L Ch R = 1 ,47406.9 ,940,1172.4,1115
BEGIN DESCRIPTION:
Cross Section 47406.9
Cross Section XS24
END DESCRIPTION:
XS GIS Cut Line= 4
      3051821.49       13954999.      3053223.46      13954395.5
      3053298.09      13954169.4      3053815.95      13953649.6
#Sta/Elev= 30
  3325.7   150.3  3635.1  146.61  3675.7   147.2  3885.7   146.4  4035.7   143.4
  4145.7   143.3  4225.7   140.8  4585.7     141  4685.7   144.3  4795.7   139.1
  4825.7   139.6    4892   137.6    4932   140.9  4934.2  139.84  4961.6  136.86
  4981.6  133.52  4986.7  130.52  5000.3  127.75  5004.7  128.54  5004.8  127.74
    5014  137.66  5021.1  140.44  5046.1  144.29    5125     144    5160     135
    5220     135    5252   148.6    5302   150.6  5470.2   149.2  5823.9   152.8
#Mann= 7 ,-1 , 0
  3325.7     .15       0  3635.1     .15       0  4934.2     .08       0
  5021.1     .15       0    5125     .04       0    5252     .15       0
  5823.9      .2       0
#Block Obstruct= 1 ,-1
    5125    5252     139
Bank Sta=4934.2,5021.1
XS Rating Curve= 0
Exp/Cntr=.3,.1

Type RM Length L Ch R = 1 ,46234.5 ,100,100,100
BEGIN DESCRIPTION:
Added 46234.5 - modified Cross Section 46134.5 upstream
Cross Section XS23
END DESCRIPTION:
XS GIS Cut Line= 4
 3051954.226528713955087.8544175       3052646.1      13955001.9
       3053507.4      13955033.1       3054367.7      13954823.2
#Sta/Elev= 30
  3732.4  150.26  3852.4     148  3972.4147.7956  4052.4146.7021  4212.4146.3838
  4252.4     147  4432.4145.7516  4712.4     142  4772.4     142  4872.4  139.07
  4922.8   138.2  4944.6  138.75  4954.9  134.44  4983.4  133.39  4987.2  130.28
  4999.9  125.95  5007.2  127.68  5011.5  132.88  5020.5  139.17  5352.4140.1536
  5472.4141.5397  5487.4   144.3  5508.4   142.5  5526.4   145.6  5554.4     146
  5592.4144.5113  5732.4145.4479  5932.4147.9265  6052.4148.0726  6292.4     152
#Mann= 3 ,-1 , 0
  3732.4     .15       0  4944.6     .08       0  5020.5     .15       0
Bank Sta=4944.6,5020.5
XS Rating Curve= 0
Exp/Cntr=.3,.1

Type RM Length L Ch R = 1 ,46134.5 ,310,300,295
BEGIN DESCRIPTION:
Cross Section 46134.5
Cross Section XS23
END DESCRIPTION:
XS GIS Cut Line= 4
       3051819.2      13955203.5       3052643.7      13955104.5
      3053501.17      13955129.2      3054366.89      13954923.1
#Sta/Elev= 30
  3732.4   149.9  3777.2  148.75  4082.4   146.3  4242.4   147.5  4462.4   147.1
  4662.8   142.5  4802.8   140.7  4922.8   138.2  4944.6  138.75  4954.9  134.44
  4983.4  133.39  4987.2  130.28  4999.9   125.8  5007.2  127.68  5011.5  132.88
  5020.5  139.17    5095   138.9    5125   139.5    5152     131    5162     131
    5184     124    5394     124    5416     131    5426     131    5456     141
    5506     145  5870.6   147.4  5900.6   148.6  6160.6   149.9  6310.6     152
#Mann= 6 ,-1 , 0
  3732.4     .15       0  3777.2     .15       0  4944.6     .08       0
  5020.5     .15       0    5125     .04       0    5456     .15       0
#Block Obstruct= 1 ,-1
    5125    5456     138
Bank Sta=4944.6,5020.5
XS Rating Curve= 0
Exp/Cntr=.3,.1

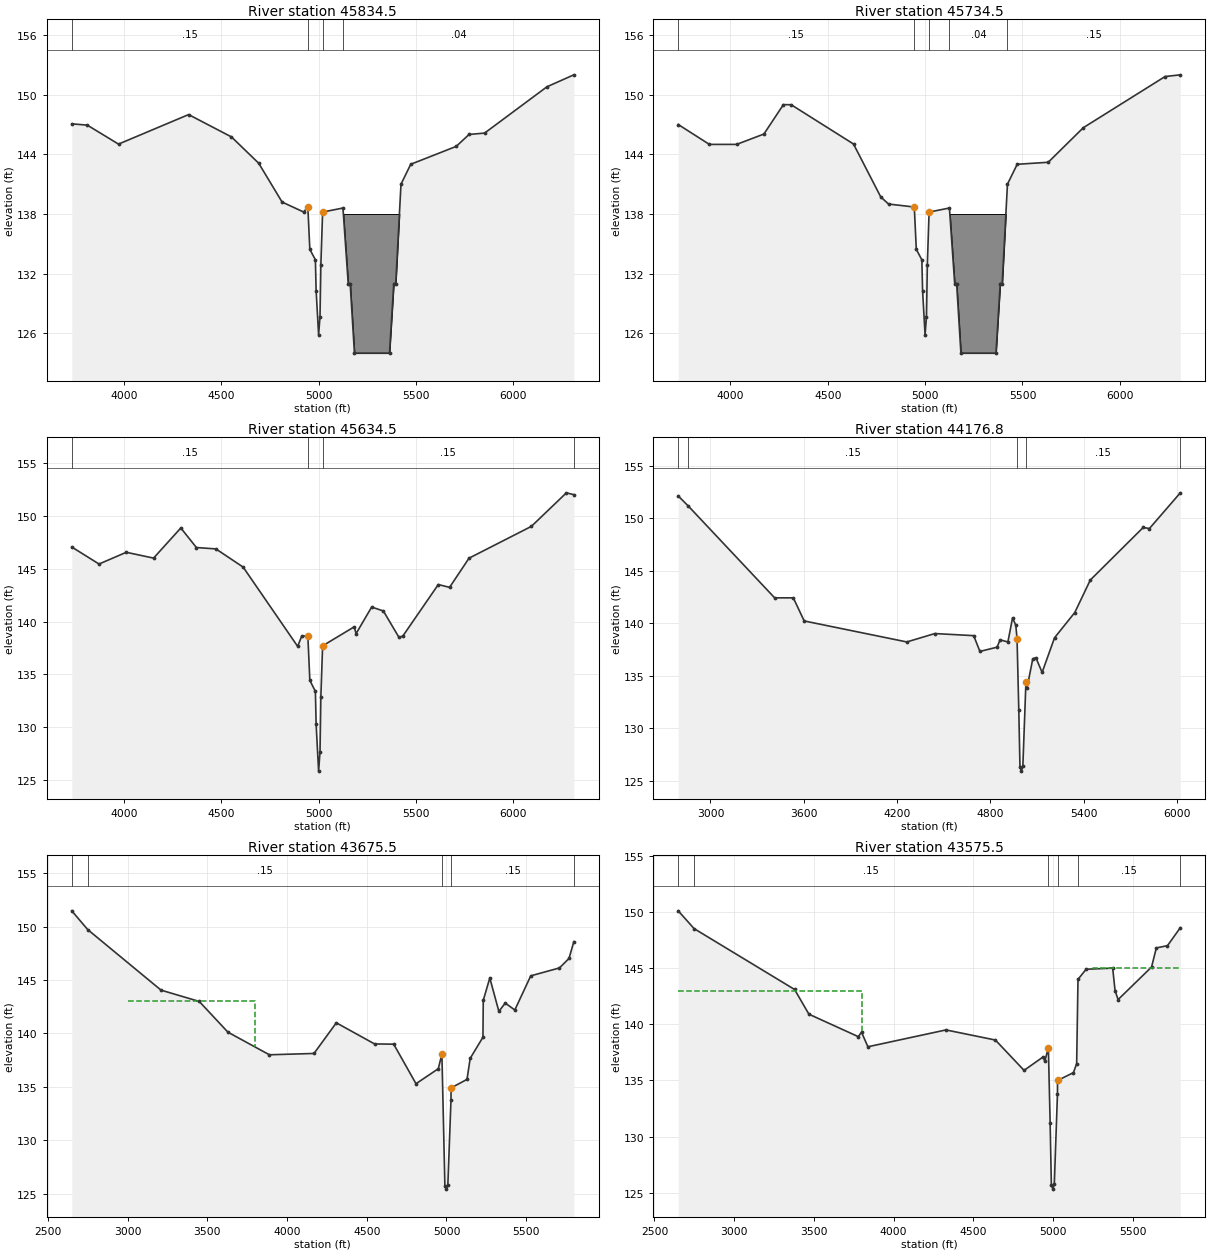
Type RM Length L Ch R = 1 ,45834.5 ,100,100,100
BEGIN DESCRIPTION:
Added 45834.5 - modified Cross Section 46134.5 downstream
Cross Section XS23
END DESCRIPTION:
XS GIS Cut Line= 4
 3051887.979365913955592.7444623        3052697.       13955434.
        3053555.       13955396.        3054402.       13955128.
#Sta/Elev= 30
  3732.4  147.07  3812.4146.9365  3972.4145.0301  4332.4     148  4552.4145.7534
  4692.4143.1031  4812.4139.2007  4922.8   138.2  4944.6   138.7  4954.9  134.44
  4983.4  133.39  4987.2  130.28  4999.9  125.85  5007.2  127.68  5011.5  132.88
  5020.5  138.19    5125   138.6    5152     131    5162     131    5184     124
    5364     124    5386     131    5396     131    5423     141    5473     143
  5706.6   144.8  5772.4     146  5852.4146.1387  6172.4150.7959  6310.6     152
#Mann= 4 ,-1 , 0
  3732.4     .15       0  4944.6     .08       0  5020.5     .15       0
    5125     .04       0
#Block Obstruct= 1 ,-1
    5125    5423     138
Bank Sta=4944.6,5020.5
XS Rating Curve= 0
Exp/Cntr=.3,.1

Type RM Length L Ch R = 1 ,45734.5 ,100,100,100
BEGIN DESCRIPTION:
Added 45734.5 - modified Cross Section 46134.5 downstream
Cross Section XS23
END DESCRIPTION:
XS GIS Cut Line= 4
 3051936.660593113955681.7006612        3052722.       13955529.
        3053580.       13955491.        3054427.       13955223.
#Sta/Elev= 30
  3732.4     147  3892.4     145  4032.4     145  4172.4 146.044  4272.4     149
  4312.4148.9914  4632.4145.0402  4772.4139.7109  4812.4     139  4944.6   138.7
  4954.9  134.44  4983.4  133.39  4987.2  130.28  4999.9  125.85  5007.2  127.68
  5011.5  132.88  5020.5  138.19    5125   138.6    5152     131    5162     131
    5184     124    5364     124    5386     131    5396     131    5423     141
    5473     143  5632.4143.2012  5812.4146.6786  6232.4151.8279  6310.6     152
#Mann= 5 ,-1 , 0
  3732.4     .15       0  4944.6     .08       0  5020.5     .15       0
    5125     .04       0    5423     .15       0
#Block Obstruct= 1 ,-1
    5125    5423     138
Bank Sta=4944.6,5020.5
XS Rating Curve= 0
Exp/Cntr=.3,.1

Type RM Length L Ch R = 1 ,45634.5 ,1506.71,1457.7,977.24
BEGIN DESCRIPTION:
Added 45534.5 - modified Cross Section 46134.5 downstream
Cross Section XS23
END DESCRIPTION:
XS GIS Cut Line= 4
        3051941.       13955788.        3052756.       13955629.
        3053614.       13955592.        3054461.       13955323.
#Sta/Elev= 30
  3732.4  147.05  3872.4  145.44  4012.4  146.55  4152.4     146  4292.4  148.85
  4372.4     147  4472.4  146.87  4612.4  145.15  4892.4  137.65  4912.8   138.6
  4944.6  138.67  4954.9  134.44  4983.4  133.39  4987.2  130.28  4999.9  125.85
  5007.2  127.68  5011.5  132.88  5020.5   137.7  5182.8   139.5  5192.4138.8577
  5272.4141.3698  5332.4     141  5412.4138.5108  5432.4138.6255  5614.6   143.5
  5672.4 143.233  5772.4145.9943  6092.4     149  6272.4152.1746  6310.6     152
#Mann= 4 ,-1 , 0
  3732.4     .15       0  4944.6     .08       0  5020.5     .15       0
  6310.6      .2       0
Bank Sta=4944.6,5020.5
XS Rating Curve= 0
Exp/Cntr=.3,.1

Type RM Length L Ch R = 1 ,44176.8 ,444.98,501.3,463.06
BEGIN DESCRIPTION:
Cross Section 44176.8
Cross Section XS22
Cross Section M100-00-00-X22
Located At: US STUEBNER-AIRLINE
END DESCRIPTION:
XS GIS Cut Line= 2
      3052758.48      13958115.5      3054773.96      13955593.1
#Sta/Elev= 30
  2792.6   152.1  2858.1  151.13  3412.6   142.4  3532.6   142.4  3602.6   140.2
  4262.6   138.2  4442.6     139  4692.6   138.8  4732.6   137.3  4842.6   137.7
  4862.6   138.4  4912.6   138.2  4942.6   140.5  4963.6  139.78  4971.4  138.49
  4982.6  131.75  4990.2   126.3  4999.9   125.9  5008.8   126.4  5028.5  134.38
    5036  133.85  5072.6   136.6  5092.6   136.7  5132.6   135.3  5212.6   138.6
  5342.6     141  5442.6   144.1  5782.6   149.1  5822.6     149  6021.3   152.4
#Mann= 5 ,-1 , 0
  2792.6     .14       0  2858.1     .15       0  4971.4     .08       0
  5028.5     .15       0  6021.3      .2       0
Bank Sta=4971.4,5028.5
XS Rating Curve= 0
Exp/Cntr=.3,.1

Type RM Length L Ch R = 1 ,43675.5 ,100,100,100
BEGIN DESCRIPTION:
Added Cross Section 43675.5, copied 43575.5 upstream
Cross Section XS20.9
END DESCRIPTION:
XS GIS Cut Line= 2
        3052904.       13958383.        3055048.       13956074.
#Sta/Elev= 30
    2649  151.49    2749149.7324    3209144.0612    3449     143    3629140.1211
    3889138.0049    4169138.1292    4309     141    4549139.0204    4669     139
    4809135.2947    4949   136.7 4971.45  138.08 4990.25  125.73 4999.95  125.42
 5008.85  125.83 5028.55  133.81    5029   134.9    5129   135.7    5149  137.67
    5229  139.65    5231   143.1    5272   145.2    5329  142.07    5369  142.85
    5429   142.2    5529   145.4    5709  146.14    5769  147.03  5799.4   148.6
#Mann= 5 ,-1 , 0
    2649     .14       0    2749     .15       0 4971.45     .07       0
    5029     .15       0  5799.4      .2       0
#XS Ineff= 2 ,-1
    3000    3800     143    5369    5500  142.85
Permanent Ineff=
       F       F
Bank Sta=4971.45,5029
XS Rating Curve= 0
Exp/Cntr=.3,.1

Type RM Length L Ch R = 1 ,43575.5 ,405.3,421,371.3
BEGIN DESCRIPTION:
Cross Section 43575.5
Cross Section XS20.9
END DESCRIPTION:
XS GIS Cut Line= 2
      3052989.98      13958435.5      3055133.68      13956126.9
#Sta/Elev= 30
    2649   150.1  2748.2  148.52    3379   143.1    3469   140.9    3779   138.9
    3799   139.3    3839     138    4329   139.5    4639   138.6    4819   135.9
    4939   137.1    4949   136.7 4971.45  137.92 4982.65  131.18 4990.25  125.73
 4999.95  125.33 5008.85  125.83 5028.55  133.81    5029     135    5129   135.7
    5149   136.5  5157.4     144  5208.4   144.9    5375     145    5390     143
    5409   142.2    5619   145.1    5649   146.8    5719     147  5799.4   148.6
#Mann= 6 ,-1 , 0
    2649     .14       0  2748.2     .15       0 4971.45     .07       0
    5029      .1       0  5157.4     .15       0  5799.4      .2       0
#XS Ineff= 2 ,-1
    2649    3800     143 5248.47 5883.44     145
Permanent Ineff=
       F       F
Bank Sta=4971.45,5029
XS Rating Curve= 0
Exp/Cntr=.5,.3

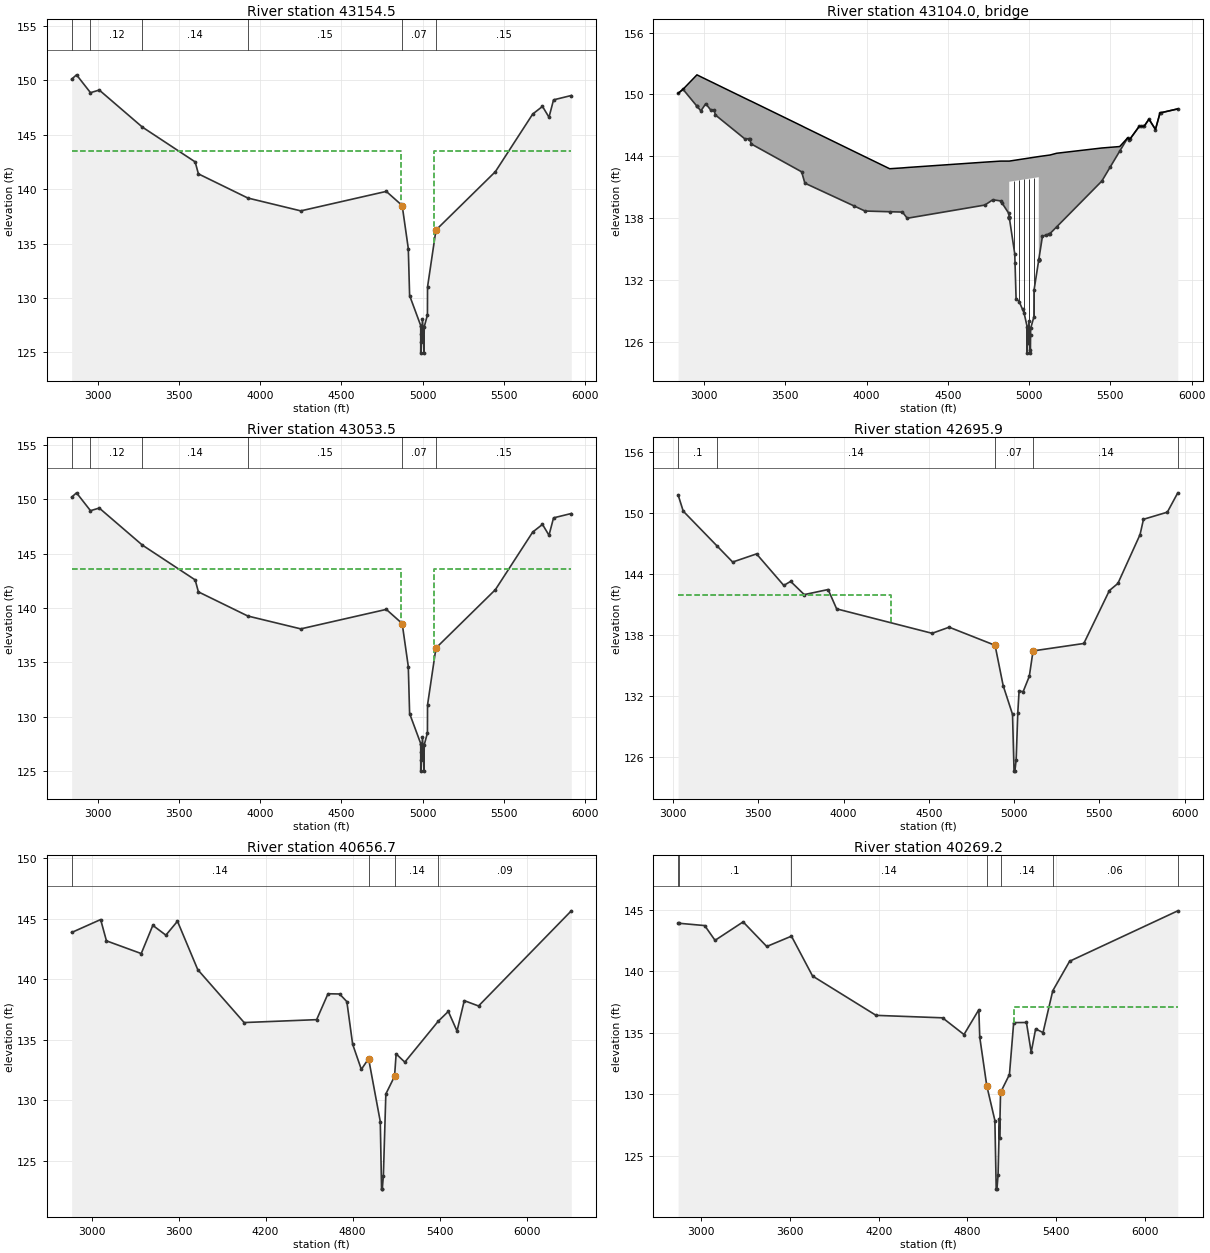
Type RM Length L Ch R = 1 ,43154.5 ,156,156,156
BEGIN DESCRIPTION:
Upstream Section of Bridge/Culvert/Weir
END DESCRIPTION:
XS GIS Cut Line= 3
      3053271.17      13958630.9      3054691.47      13957020.2
      3055277.16      13956449.2
#Sta/Elev= 30
  2840.1  150.11  2870.1  150.51    2956  148.87  3010.1  149.11    3275  145.71
  3600.1  142.51  3620.1  141.41  3924.4  139.19  4250.1  138.01  4776.3   139.8
  4874.1   138.5  4911.7  134.55  4919.8  130.23  4988.2  127.47  4988.4  124.94
    4991  127.45  4991.1  126.71  4992.5  125.96  4998.9  128.07  5007.9  124.98
  5009.8  127.36  5029.5  128.45  5030.1  131.02  5081.9  136.25  5447.5  141.61
  5677.5  146.91  5737.5  147.61  5777.5  146.61  5805.5  148.21  5914.8  148.61
#Mann= 6 , 1 , 0
  2840.1      .2       0    2956     .12       0    3275     .14       0
  3924.4     .15       0  4874.1     .07       0  5081.9     .15       0
#XS Ineff= 2 , 0
       0    4865  143.55    5070       0  143.55
Permanent Ineff=
       F       F
Bank Sta=4874.1,5081.9
XS Rating Curve= 0
Exp/Cntr=.5,.3

Type RM Length L Ch R = 3 ,43104.0 ,,,
BEGIN DESCRIPTION:
STUEBNER-AIRLINE/2920
Structure ID: M100-00-00-10
Cross Section 43104.0
END DESCRIPTION:
Node Name=Stuebner(FM2920)
Bridge Culvert--1,0,-1,-1, 0
Deck Dist Width WeirC Skew NumUp NumDn MinLoCord MaxHiCord MaxSubmerge Is_Ogee
10,81,2.6,0, 38, 38, , , .95, 0, 1,1,,
  2840.1  2870.1    2956  2980.1  3010.1  3040.1  3060.1  3070.1  3250.1  3280.1
  3290.1  3600.1  3620.1  3990.1  4141.9  4220.1  4250.1  4728.2  4776.3  4825.2
  4874.1 4877.81  4877.9 5059.49  5059.6  5081.9  5128.9  5169.3  5447.5  5557.5
  5607.5  5617.5  5677.5  5707.5  5737.5  5777.5  5805.5  5914.8
   150.1   150.5   151.9  151.71  151.48  151.25   151.1  151.02  149.64  149.41
  149.34  146.96   146.8  143.96   142.8  142.88  142.92  143.44  143.49  143.54
  143.54  143.54  143.54  143.98  143.98  144.03  144.13   144.3  144.81  144.95
  145.81  145.61  146.91  146.91  147.61  146.61  148.21   148.6
   150.1   150.5  148.86   148.4   149.1   148.5   148.5     148   145.7   145.7
   145.2   142.5   141.4   138.7  138.63   138.6     138  139.28  139.79  139.68
  138.49   138.1  141.54  141.98  133.99  136.24  136.52  137.16   141.6   144.5
   145.8   145.6   146.9   146.9   147.6   146.6   148.2   148.6
  2840.1  2870.1    2956  2980.1  3010.1  3040.1  3060.1  3070.1  3250.1  3280.1
  3290.1  3600.1  3620.1  3990.1  4141.9  4220.1  4250.1  4728.2  4776.3  4825.2
  4874.1 4877.81  4877.9 5059.49  5059.6  5081.9  5128.9  5169.3  5447.5  5557.5
  5607.5  5617.5  5677.5  5707.5  5737.5  5777.5  5805.5  5914.8
  150.19  150.59   151.9  151.71  151.48  151.25   151.1  151.02  149.64  149.41
  149.34  146.96   146.8  143.96   142.8  142.88  142.92  143.44  143.49  143.54
  143.54  143.54  143.54  143.98  143.98  144.03  144.13   144.3  144.81  144.95
  145.89  145.69  146.99  146.99  147.69  146.69  148.29  148.69
  150.19  150.59  148.95  148.49  149.19  148.59  148.59  148.09  145.79  145.79
  145.29  142.59  141.49  138.79  138.72  138.69  138.09  139.37  139.88  139.77
  138.58  138.19  141.63  142.07  134.08  136.33  136.61  137.25  141.69  144.59
  145.89  145.69  146.99  146.99  147.69  146.69  148.29  148.69
Pier Skew, UpSta & Num, DnSta & Num=  ,4908.6, 2 ,4908.6, 2 , 0 , 0 , 0 ,,
     1.4     1.4
  133.79   142.6
     1.4     1.4
  133.88  142.69
Pier Skew, UpSta & Num, DnSta & Num=  ,4938.5, 2 ,4938.5, 2 , 0 , 0 , 0 ,,
     1.4     1.4
   128.9  142.68
     1.4     1.4
  128.99  142.77
Pier Skew, UpSta & Num, DnSta & Num=  ,4969.2, 2 ,4969.2, 2 , 0 , 0 , 0 ,,
     1.4     1.4
  127.77  142.75
     1.4     1.4
  127.86  142.84
Pier Skew, UpSta & Num, DnSta & Num=  ,4998.9, 2 ,4998.9, 2 , 0 , 0 , 0 ,,
     1.4     1.4
  126.82   142.8
     1.4     1.4
  126.91  142.89
Pier Skew, UpSta & Num, DnSta & Num=  ,5029.5, 2 ,5029.5, 2 , 0 , 0 , 0 ,,
     1.4     1.4
   127.4  142.88
     1.4     1.4
  127.49  142.97
Abutment Skew #Up #Dn= , 2 , 2
  4877.7  4878.8
  141.54     138
  4877.7  4878.8
  141.63  138.09
BR Coef= 1 , 1 , 1 ,1.25, 0 ,,,.8,0,2,0,
WSPro=,,,, 1 ,,,, 0 ,,,, 0 ,,,,-1 ,-1 ,-1 , 0 , 0 , 0 , 0 , 0
BR U #Sta/Elev= 73
  2840.1   150.1  2870.1   150.5  2955.9  148.86    2956  148.86  2980.1   148.4
  3010.1   149.1  3040.1   148.5  3060.1   148.5  3070.1     148  3250.1   145.7
    3275   145.7  3280.1   145.7  3290.1   145.2  3600.1   142.5  3620.1   141.4
  3924.4  139.18  3990.1   138.7  4141.9  138.63  4220.1   138.6  4250.1     138
  4728.2  139.28  4776.3  139.79  4825.2  139.68    4832  139.51  4874.1  138.49
  4877.7  138.11 4877.81   138.1  4877.9  138.09  4878.1  138.07  4878.8     138
  4911.7  134.54  4913.4  133.63  4919.8  130.22  4938.5  129.93  4959.9  129.16
  4969.2  128.82  4988.2  127.46  4988.4  124.93    4991  127.44  4991.1   126.7
  4992.5  125.95  4998.9  128.06    5007  125.28  5007.9  124.97  5008.9  126.65
  5009.8  127.35  5029.5  128.44  5030.1  131.01  5058.8  133.91 5059.49  133.98
  5059.6  133.99  5059.7     134  5059.8  134.01  5081.9  136.24  5101.7  136.36
  5121.9  136.48  5128.9  136.52  5169.3  137.16  5447.5   141.6  5499.3  142.97
  5557.5   144.5  5607.5   145.8  5617.5   145.6  5619.3  145.64  5677.5   146.9
  5689.3   146.9  5699.3   146.9  5707.5   146.9  5737.5   147.6  5777.5   146.6
  5805.5   148.2  5809.3  148.21  5914.8   148.6
BR U #Mann= 6
  2840.1      .2    2956     .12    3275     .14  3924.4     .15  4874.1     .06
  5081.9     .15
BR U Banks=4874.1,5081.9
BR D #Sta/Elev= 73
  2840.1  150.19  2870.1  150.59  2955.9  148.95    2956  148.95  2980.1  148.49
  3010.1  149.19  3040.1  148.59  3060.1  148.59  3070.1  148.09  3250.1  145.79
    3275  145.79  3280.1  145.79  3290.1  145.29  3600.1  142.59  3620.1  141.49
  3924.4  139.27  3990.1  138.79  4141.9  138.72  4220.1  138.69  4250.1  138.09
  4728.2  139.37  4776.3  139.88  4825.2  139.77    4832   139.6  4874.1  138.58
  4877.7   138.2 4877.81  138.19  4877.9  138.18  4878.1  138.16  4878.8  138.09
  4911.7  134.63  4913.4  133.72  4919.8  130.31  4938.5  130.02  4959.9  129.25
  4969.2  128.91  4988.2  127.55  4988.4  125.02    4991  127.53  4991.1  126.79
  4992.5  126.04  4998.9  128.15    5007  125.37  5007.9  125.06  5008.9  126.74
  5009.8  127.44  5029.5  128.53  5030.1   131.1  5058.8     134 5059.49  134.07
  5059.6  134.08  5059.7  134.09  5059.8   134.1  5081.9  136.33  5101.7  136.45
  5121.9  136.57  5128.9  136.61  5169.3  137.25  5447.5  141.69  5499.3  143.06
  5557.5  144.59  5607.5  145.89  5617.5  145.69  5619.3  145.73  5677.5  146.99
  5689.3  146.99  5699.3  146.99  5707.5  146.99  5737.5  147.69  5777.5  146.69
  5805.5  148.29  5809.3   148.3  5914.8  148.69
BR D #Mann= 6
  2840.1      .2    2956     .12    3275     .14  3924.4     .15  4874.1     .06
  5081.9     .15
BR D Banks=4874.1,5081.9
BC Design=,, 0 ,, 0 ,,,,,,
BC HTab HWMax=150.51

Type RM Length L Ch R = 1 ,43053.5 ,342.3,357.6,325.6
BEGIN DESCRIPTION:
Downstream Section of Bridge/Culvert/Weir
END DESCRIPTION:
XS GIS Cut Line= 5
      3053360.83      13958734.9      3053734.01      13958307.9
      3054146.26      13957846.2      3054847.02      13957094.9
      3055374.15      13956567.8
#Sta/Elev= 30
  2840.1  150.18  2870.1  150.58    2956  148.94  3010.1  149.18    3275  145.78
  3600.1  142.58  3620.1  141.48  3924.4  139.26  4250.1  138.08  4776.3  139.87
  4874.1  138.57  4911.7  134.62  4919.8   130.3  4988.2  127.54  4988.4  125.01
    4991  127.52  4991.1  126.78  4992.5  126.03  4998.9  128.14  5007.9  125.05
  5009.8  127.43  5029.5  128.52  5030.1  131.09  5081.9  136.32  5447.5  141.68
  5677.5  146.98  5737.5  147.68  5777.5  146.68  5805.5  148.28  5914.8  148.68
#Mann= 6 ,-1 , 0
  2840.1      .2       0    2956     .12       0    3275     .14       0
  3924.4     .15       0  4874.1     .07       0  5081.9     .15       0
#XS Ineff= 2 , 0
       0    4865  143.55    5070       0  143.55
Permanent Ineff=
       F       F
Bank Sta=4874.1,5081.9
XS Rating Curve= 0
Exp/Cntr=.5,.3

Type RM Length L Ch R = 1 ,42695.9 ,1687.81,2039.2,1701.81
BEGIN DESCRIPTION:
Cross Section 42695.9
Cross Section XS20.8
END DESCRIPTION:
XS GIS Cut Line= 2
      3053649.58      13958880.7      3055603.64      13956695.8
#Sta/Elev= 30
  3029.2   151.8  3059.2   150.2  3258.2  146.77  3349.2   145.2  3489.2     146
  3649.2   142.9  3689.2   143.3  3769.2     142  3909.2   142.5  3959.2   140.6
  4519.2   138.2  4619.2   138.8  4888.6  137.02  4936.1  133.06    4991  130.24
  4999.9  124.68  5004.8  124.66  5012.4  125.78  5021.9  130.39  5029.4  132.52
  5053.3  132.47  5089.5  133.98  5111.4  136.47  5409.2   137.2  5559.2   142.4
  5609.2   143.1  5739.2   147.9  5759.2   149.4  5899.2   150.1  5960.4     152
#Mann= 5 ,-1 , 0
  3029.2      .1       0  3258.2     .14       0  4888.6     .07       0
  5111.4     .14       0  5960.4      .2       0
#XS Ineff= 2 , 0
       0    4280     142               0
Permanent Ineff=
       F       F
Bank Sta=4888.6,5111.4
XS Rating Curve= 0
Exp/Cntr=.3,.1

Type RM Length L Ch R = 1 ,40656.7 ,339.1,387.5,343.4
BEGIN DESCRIPTION:
Cross Section 40656.7
Cross Section XS20.7
END DESCRIPTION:
XS GIS Cut Line= 4
      3054886.52      13959597.8      3056203.79       13958418.
      3056942.17      13957687.7      3057522.43      13957417.8
#Sta/Elev= 30
    2862  143.86    3062  144.93    3102  143.17    3342  142.12    3422  144.45
    3512  143.64    3592  144.79    3732  140.79    4052  136.42    4552  136.66
  4630.4   138.8  4710.4  138.78  4760.4  138.15  4800.4  134.63  4860.4  132.55
 4910.45  133.44 4991.05  128.24 4999.95  122.68 5004.85  122.66 5012.45  123.78
 5029.45  130.52 5089.55  131.98  5100.4  133.83  5160.4  133.15  5390.9  136.53
  5460.4  137.34  5520.4  135.72  5570.4  138.23  5668.9  137.79  6308.8  145.65
#Mann= 4 ,-1 , 0
    2862     .14       0 4910.45     .07       0 5089.55     .14       0
  5390.9     .09       0
Bank Sta=4910.45,5089.55
XS Rating Curve= 0
Exp/Cntr=.5,.3

Type RM Length L Ch R = 1 ,40269.2 ,58,58,58
BEGIN DESCRIPTION:
Upstream Section of Bridge/Culvert/Weir
END DESCRIPTION:
XS GIS Cut Line= 2
      3055228.58      13959830.6      3057656.84       13957484.
#Sta/Elev= 30
  2842.6  143.91  2847.4   143.9  3022.6  143.71  3092.6  142.51  3282.6  144.01
  3442.6  142.01  3609.9  142.85  3752.6  139.61  4182.6  136.41  4632.6  136.21
  4777.6  134.85  4878.1  136.87  4884.3  134.64  4931.9  130.68  4986.8  127.86
  4995.7   122.3  5000.6  122.28  5008.2   123.4  5017.7  128.01  5018.3   126.4
  5025.2  130.14  5085.3   131.6    5114  135.82  5200.4  135.83  5232.6  133.41
  5262.6  135.31  5312.6  135.01  5378.5  138.41  5492.6  140.81  6224.7  144.91
#Mann= 7 ,-1 , 0
  2842.6      .2       0  2847.4      .1       0  3609.9     .14       0
  4931.9     .07       0  5025.2     .14       0  5378.5     .06       0
  6224.7      .2       0
#XS Ineff= 2 , 0
       0    4873   136.5    5117       0  137.09
Permanent Ineff=
       F       F
Bank Sta=4931.9,5025.2
XS Rating Curve= 0
Exp/Cntr=.5,.3

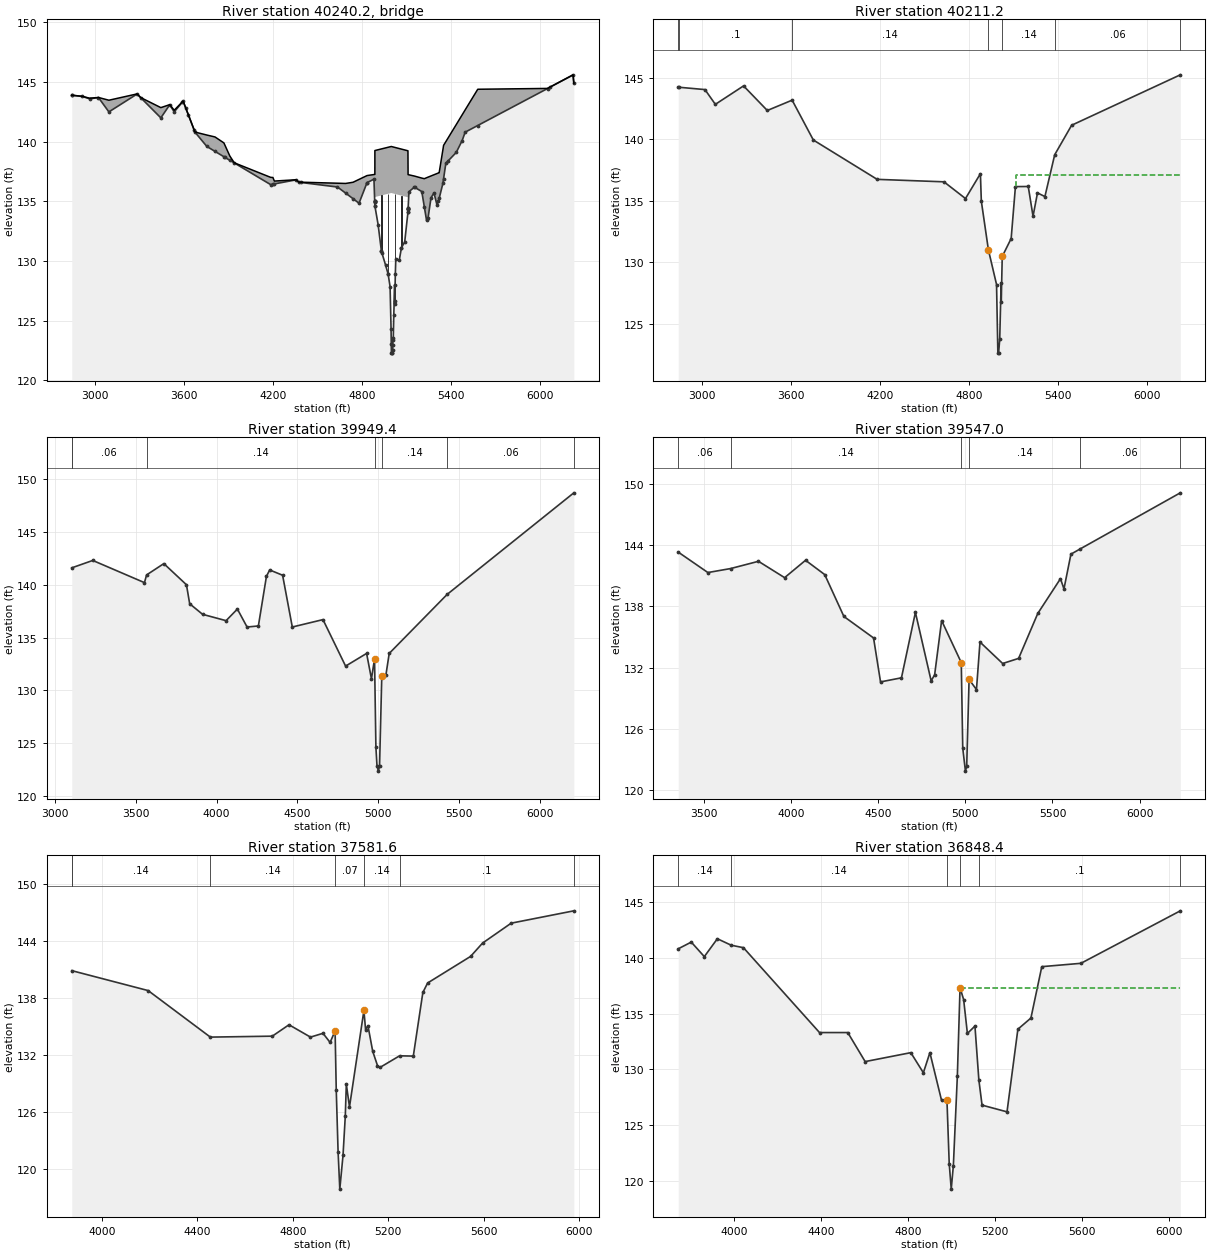
Type RM Length L Ch R = 3 ,40240.2 ,,,
BEGIN DESCRIPTION:
TUWA
Structure ID: M100-00-00-09
Cross Section 40420.2
END DESCRIPTION:
Node Name=Tuwa Rd.
Bridge Culvert--1,0,-1,-1, 0
Deck Dist Width WeirC Skew NumUp NumDn MinLoCord MaxHiCord MaxSubmerge Is_Ogee
10,38,2.6,0, 52, 52, , , .95, 0, 1,1,,
  2842.6  2912.6  2962.6  3022.6  3092.6  3282.6  3307.4  3442.6  3502.6  3532.6
  3592.6  3672.6  3752.6  3807.4  3867.4  3907.4  3937.4  4182.6  4197.4  4207.4
  4352.6  4372.6  4632.6  4687.4  4737.4  4777.6  4831.5  4884.3  4884.4  4994.9
  5107.2  5108.1  5150.8  5200.4  5217.4  5232.6  5242.6  5262.6  5282.6  5302.6
  5312.6  5317.4  5342.6  5347.4  5362.6  5432.6  5472.6  5492.6  5577.4  6047.4
  6219.5  6224.7
   143.9  143.81  143.65  143.71  143.48  144.01   143.7  142.86  143.11  142.64
  143.41  140.81  140.56   140.4   139.9   138.8  138.23  137.01     137   136.7
  136.81  136.61  136.52   136.5   136.6  136.84  137.16  137.26  139.26   139.6
  139.24  137.24  137.12  136.95   136.9  136.98  137.03  137.13  137.23  137.33
  137.38   137.4  139.33   139.7  140.01  141.44  142.26  142.67   144.4  144.47
  145.61   144.9
   143.9   143.8   143.6   143.7   142.5     144  143.69     142   143.1   142.5
   143.4   140.8   139.6  139.19  138.74  138.44  138.22   136.4  136.43  136.46
   136.8   136.6   136.2  135.69  135.22  134.84  136.56  135.36  135.36   135.7
  135.34  135.34  136.19  135.82  134.54   133.4   133.6   135.3   135.7   134.7
     135  135.24   136.5  136.91   138.2   139.1   140.1   140.8  141.36  144.46
   145.6   144.9
  2842.6  2912.6  2962.6  3022.6  3092.6  3282.6  3307.4  3442.6  3502.6  3532.6
  3592.6  3672.6  3752.6  3807.4  3867.4  3907.4  3937.4  4182.6  4197.4  4207.4
  4352.6  4372.6  4632.6  4687.4  4737.4  4777.6  4831.5  4884.3  4884.4  4994.9
  5107.2  5108.1  5150.8  5200.4  5217.4  5232.6  5242.6  5262.6  5282.6  5302.6
  5312.6  5317.4  5342.6  5347.4  5362.6  5432.6  5472.6  5492.6  5577.4  6047.4
  6219.5  6224.7
  144.26  144.16  143.96  144.06  143.48  144.36  144.05  142.86  143.46  142.86
  143.76  141.16  140.56   140.4   139.9   138.8  138.58  137.01     137  136.82
  137.16  136.96  136.56   136.5   136.6  136.84  137.16  137.26  139.26   139.6
  139.24  137.24  137.12  136.95   136.9  136.98  137.03  137.13  137.23  137.33
  137.38   137.4  139.33   139.7  140.01  141.44  142.26  142.67   144.4  144.82
  145.96  145.26
  144.26  144.16  143.96  144.06  142.86  144.36  144.05  142.36  143.46  142.86
  143.76  141.16  139.96  139.55   139.1   138.8  138.58  136.76  136.79  136.82
  137.16  136.96  136.56  136.05  135.58   135.2  136.92  135.72  135.72  136.06
   135.7   135.7  136.55  136.18   134.9  133.76  133.96  135.66  136.06  135.06
  135.36   135.6  136.86  137.27  138.56  139.46  140.46  141.16  141.72  144.82
  145.96  145.26
Pier Skew, UpSta & Num, DnSta & Num=  ,4928.4, 2 ,4928.4, 2 , 0 , 0 , 0 ,,
     1.4     1.4
   129.8  136.53
     1.4     1.4
  130.16  136.89
Pier Skew, UpSta & Num, DnSta & Num=  ,4973.3, 2 ,4973.3, 2 , 0 , 0 , 0 ,,
     1.4     1.4
  127.86  136.64
     1.4     1.4
  128.22     137
Pier Skew, UpSta & Num, DnSta & Num=  ,5018.3, 2 ,5018.3, 2 , 0 , 0 , 0 ,,
     1.4     1.4
  125.85  136.63
     1.4     1.4
  126.21  136.99
Pier Skew, UpSta & Num, DnSta & Num=  ,5063.3, 2 ,5063.3, 2 , 0 , 0 , 0 ,,
     1.4     1.4
  130.06  136.53
     1.4     1.4
  130.42  136.89
Abutment Skew #Up #Dn= , 2 , 2
  4883.2  4884.4
  135.51  134.62
  4883.2  4884.4
  135.87  134.98
Abutment Skew #Up #Dn= , 2 , 2
  5107.2 5108.39
  134.11  135.53
  5107.2 5108.39
  134.47  135.89
BR Coef= 1 , 1 , 1 ,1.25, 0 ,,,.8,0,2,0,
WSPro=,,,, 1 ,,,, 0 ,,,, 0 ,,,,-1 ,-1 ,-1 , 0 , 0 , 0 , 0 , 0
BR U #Sta/Elev= 101
  2842.6   143.9  2847.4  143.89  2912.6   143.8  2962.6   143.6  3022.6   143.7
  3092.6   142.5  3282.6     144  3307.4  143.69  3442.6     142  3502.6   143.1
  3532.6   142.5  3587.4  143.32  3592.6   143.4  3609.9  142.84  3627.4  142.27
  3667.4  140.97  3672.6   140.8  3752.6   139.6  3807.4  139.19  3867.4  138.74
  3872.6   138.7  3907.4  138.44  3937.4  138.22  4182.6   136.4  4197.4  136.43
  4207.4  136.46  4352.6   136.8  4372.6   136.6  4387.4  136.58  4632.6   136.2
  4687.4  135.69  4737.4  135.22  4777.6  134.84  4831.1  136.55  4831.5  136.56
  4878.1  136.86  4883.1  135.06  4883.2  135.03 4883.31  134.99  4883.4  134.95
  4883.5  134.92  4884.3  134.63  4884.4  134.62  4906.2  133.05  4928.2  130.85
  4928.4  130.83  4931.9  130.67  4956.1  129.67  4973.2  128.92  4973.3  128.92
  4986.8  127.85  4993.4  124.31  4994.9  123.01  4995.7  122.29  4996.8  122.29
  5000.6  122.27  5004.2  122.56  5005.1  122.96  5006.4  123.57  5008.2  123.39
  5011.7  125.43  5017.7     128  5018.2  126.66  5018.3  126.39  5022.1  128.88
  5025.2  130.13  5049.1  130.08  5063.2   131.1  5063.3  131.11  5085.3  131.59
  5107.1  134.08  5107.2  134.11  5108.1  134.33 5108.19  134.35  5108.3  134.38
  5108.4  134.41  5108.5  134.43    5114  135.81  5150.8  136.19  5151.6  136.18
  5200.4  135.82  5217.4  134.54  5232.6   133.4  5242.6   133.6  5262.6   135.3
  5282.6   135.7  5302.6   134.7  5312.6     135  5317.4  135.24  5342.6   136.5
  5347.4  136.91  5362.6   138.2  5378.5   138.4  5432.6   139.1  5472.6   140.1
  5492.6   140.8  5577.4  141.36  6047.4  144.46  6067.4   144.6  6219.5   145.6
  6224.7   144.9
BR U #Mann= 6
  2842.6      .2  2847.4      .1  3609.9     .14  4931.9     .06  5025.2     .14
  5378.5     .06
BR U Banks=4931.9,5025.2
BR D #Sta/Elev= 101
  2842.6  144.26  2847.4  144.25  2912.6  144.16  2962.6  143.96  3022.6  144.06
  3092.6  142.86  3282.6  144.36  3307.4  144.05  3442.6  142.36  3502.6  143.46
  3532.6  142.86  3587.4  143.68  3592.6  143.76  3609.9   143.2  3627.4  142.63
  3667.4  141.33  3672.6  141.16  3752.6  139.96  3807.4  139.55  3867.4   139.1
  3872.6  139.06  3907.4   138.8  3937.4  138.58  4182.6  136.76  4197.4  136.79
  4207.4  136.82  4352.6  137.16  4372.6  136.96  4387.4  136.94  4632.6  136.56
  4687.4  136.05  4737.4  135.58  4777.6   135.2  4831.1  136.91  4831.5  136.92
  4878.1  137.22  4883.1  135.42  4883.2  135.39 4883.31  135.35  4883.4  135.31
  4883.5  135.28  4884.3  134.99  4884.4  134.98  4906.2  133.41  4928.2  131.21
  4928.4  131.19  4931.9  131.03  4956.1  130.03  4973.2  129.28  4973.3  129.28
  4986.8  128.21  4993.4  124.67  4994.9  123.37  4995.7  122.65  4996.8  122.65
  5000.6  122.63  5004.2  122.92  5005.1  123.32  5006.4  123.93  5008.2  123.75
  5011.7  125.79  5017.7  128.36  5018.2  127.02  5018.3  126.75  5022.1  129.24
  5025.2  130.49  5049.1  130.44  5063.2  131.46  5063.3  131.47  5085.3  131.95
  5107.1  134.44  5107.2  134.47  5108.1  134.69 5108.19  134.71  5108.3  134.74
  5108.4  134.77  5108.5  134.79    5114  136.17  5150.8  136.55  5151.6  136.54
  5200.4  136.18  5217.4   134.9  5232.6  133.76  5242.6  133.96  5262.6  135.66
  5282.6  136.06  5302.6  135.06  5312.6  135.36  5317.4   135.6  5342.6  136.86
  5347.4  137.27  5362.6  138.56  5378.5  138.76  5432.6  139.46  5472.6  140.46
  5492.6  141.16  5577.4  141.72  6047.4  144.82  6067.4  144.96  6219.5  145.96
  6224.7  145.26
BR D #Mann= 6
  2842.6      .2  2847.4      .1  3609.9     .14  4931.9     .06  5025.2     .14
  5378.5     .06
BR D Banks=4931.9,5025.2
BC Design=,, 0 ,, 0 ,,,,,,
BC HTab HWMax=145.61

Type RM Length L Ch R = 1 ,40211.2 ,261.8,261.8,261.8
BEGIN DESCRIPTION:
Downstream Section of Bridge/Culvert/Weir
END DESCRIPTION:
XS GIS Cut Line= 2
      3055278.72       13959869.      3057721.84      13957537.2
#Sta/Elev= 30
  2842.6  144.25  2847.4  144.24  3022.6  144.05  3092.6  142.85  3282.6  144.35
  3442.6  142.35  3609.9  143.19  3752.6  139.95  4182.6  136.75  4632.6  136.55
  4777.6  135.19  4878.1  137.21  4884.3  134.98  4931.9  131.02  4986.8   128.2
  4995.7  122.64  5000.6  122.62  5008.2  123.74  5017.7  128.35  5018.3  126.74
  5025.2  130.48  5085.3  131.94    5114  136.16  5200.4  136.17  5232.6  133.75
  5262.6  135.65  5312.6  135.35  5378.5  138.75  5492.6  141.15  6224.7  145.25
#Mann= 7 ,-1 , 0
  2842.6      .2       0  2847.4      .1       0  3609.9     .14       0
  4931.9     .07       0  5025.2     .14       0  5378.5     .06       0
  6224.7      .2       0
#XS Ineff= 2 , 0
       0    4873   136.5    5117       0  137.09
Permanent Ineff=
       F       F
Bank Sta=4931.9,5025.2
XS Rating Curve= 0
Exp/Cntr=.5,.3

Type RM Length L Ch R = 1 ,39949.4 ,403.77,402.4,374.35
BEGIN DESCRIPTION:
Cross Section 39949.4
Cross Section XS20.5
END DESCRIPTION:
XS GIS Cut Line= 4
      3055698.97      13959879.9      3056337.44      13959169.3
      3057335.08      13958278.8       3058126.6      13958080.9
#Sta/Elev= 30
  3103.1   141.6  3233.1   142.3  3553.1   140.2  3566.4  140.93  3673.1     142
  3813.1     140  3833.1   138.2  3913.1   137.2  4058.4   136.6  4128.4   137.7
  4188.4     136  4258.4   136.1  4308.4   140.8  4328.4   141.4  4408.4   140.9
  4468.4     136  4658.4   136.7  4798.4   132.3  4928.4   133.5  4958.4   131.1
  4977.6  132.98    4986  124.62  4992.8  122.86  5001.4  122.36  5008.6  122.84
  5022.4  131.33  5048.4   131.5  5068.4   133.5  5427.4  139.09  6211.5   148.7
#Mann= 7 , 1 , 0
  3103.1      .2       0  3103.1     .06       0  3566.4     .14       0
  4977.6     .07       0  5022.4     .14       0  5427.4     .06       0
  6211.5      .2       0
#XS Ineff= 2 , 0
       0  4328.4   141.4               0
Permanent Ineff=
       F       F
Bank Sta=4977.6,5022.4
XS Rating Curve= 0
Exp/Cntr=.3,.1

Type RM Length L Ch R = 1 ,39547.0 ,1655.88,1965.4,1723.51
BEGIN DESCRIPTION:
Cross Section 39547.0
Cross Section M100-00-00-X20
Located At: DS TUWA
END DESCRIPTION:
XS GIS Cut Line= 4
      3056171.94      13960150.9      3057051.04      13959073.8
      3057385.11      13958713.3      3058266.64       13958247.
#Sta/Elev= 30
  3354.1   143.3  3524.1   141.3  3654.4  141.69  3814.1   142.4  3964.1   140.8
  4084.1   142.5  4194.1   141.1  4304.1     137  4474.1   134.9  4514.1   130.6
  4634.1     131  4714.1   137.4  4804.4   130.7  4824.4   131.3  4864.4   136.6
  4977.1  132.49  4985.5  124.13  5000.9  121.87  5008.2  122.35  5021.9  130.84
  5064.2  129.85  5084.4   134.5  5214.4   132.4  5305.9   132.9  5415.9   137.3
  5545.9   140.7  5565.9   139.7  5605.9   143.1  5657.8   143.6  6233.1   149.1
#Mann= 6 ,-1 , 0
  3354.1     .06       0  3654.4     .14       0  4977.1     .07       0
  5021.9     .14       0  5657.8     .06       0  6233.1      .2       0
Bank Sta=4977.1,5021.9
XS Rating Curve= 0
Exp/Cntr=.3,.1

Type RM Length L Ch R = 1 ,37581.6 ,500,733.2,900
BEGIN DESCRIPTION:
Cross Section 37581.6
Cross Section M100-00-00-X19
Located At: 2ND DS TUWA
Cross Section XS19
END DESCRIPTION:
XS GIS Cut Line= 4
      3057043.19      13960820.1       3058039.4      13960439.8
      3058103.34      13960288.4      3058755.58      13959708.8
#Sta/Elev= 30
  3873.8   140.9  4193.8   138.8  4454.3   133.9  4713.8     134  4783.8   135.2
  4873.8   133.9  4926.2   134.3  4955.9  133.34  4976.9  134.55  4981.7  128.33
  4989.4  121.84  4996.6  117.89  5010.1  121.46  5019.6  125.59  5023.9  128.93
  5037.2  126.55  5097.6  136.71  5104.5   134.7  5114.5   135.1  5134.5   132.4
  5154.5   130.9  5164.5   130.7  5247.1  131.93  5304.5   131.9  5344.5   138.6
  5364.5   139.6  5544.5   142.4  5594.5   143.8  5714.5   145.9    5977   147.2
#Mann= 7 , 1 , 0
  3873.8      .2       0  3873.8     .14       0  4454.3     .14       0
  4976.9     .07       0  5097.6     .14       0  5247.1      .1       0
    5977      .2       0
#XS Ineff= 2 , 0
       0                  5097.6       0  136.71
Permanent Ineff=
       F       F
Bank Sta=4976.9,5097.6
XS Rating Curve= 0
Exp/Cntr=.3,.1

Type RM Length L Ch R = 1 ,36848.4 ,336.92,322.36,285.22
BEGIN DESCRIPTION:
Cross Section 36848.4
Cross Section XS18
END DESCRIPTION:
XS GIS Cut Line= 4
      3057076.85      13960870.6      3058160.56      13960776.4
        3058450.      13960944.7      3059272.65      13960612.2
#Sta/Elev= 30
  3743.6   140.8  3803.6   141.4  3863.6   140.1  3923.6   141.7  3987.4  141.12
  4043.6   140.9  4393.6   133.3  4523.6   133.3  4603.6   130.7  4813.6   131.5
  4871.4   129.7  4901.4   131.5  4955.1  127.22  4979.8   127.3  4990.3  121.57
  4999.6  119.28  5009.4  121.39  5027.7   129.4  5040.1  137.31  5056.7  136.25
  5073.9  133.22  5108.7  133.88  5126.7  129.05  5141.4   126.8  5256.2   126.2
  5306.2   133.6  5366.2   134.6  5416.2   139.2  5596.2   139.5  6053.5   144.2
#Mann= 6 ,-1 , 0
  3743.6     .14       0  3987.4     .14       0  4979.8     .07       0
  5040.1     .14       0  5126.7      .1       0  6053.5      .2       0
#XS Ineff= 2 , 0
       0                    5040       0   137.3
Permanent Ineff=
       F       T
Bank Sta=4979.8,5040.1
XS Rating Curve= 0
Exp/Cntr=.3,.1