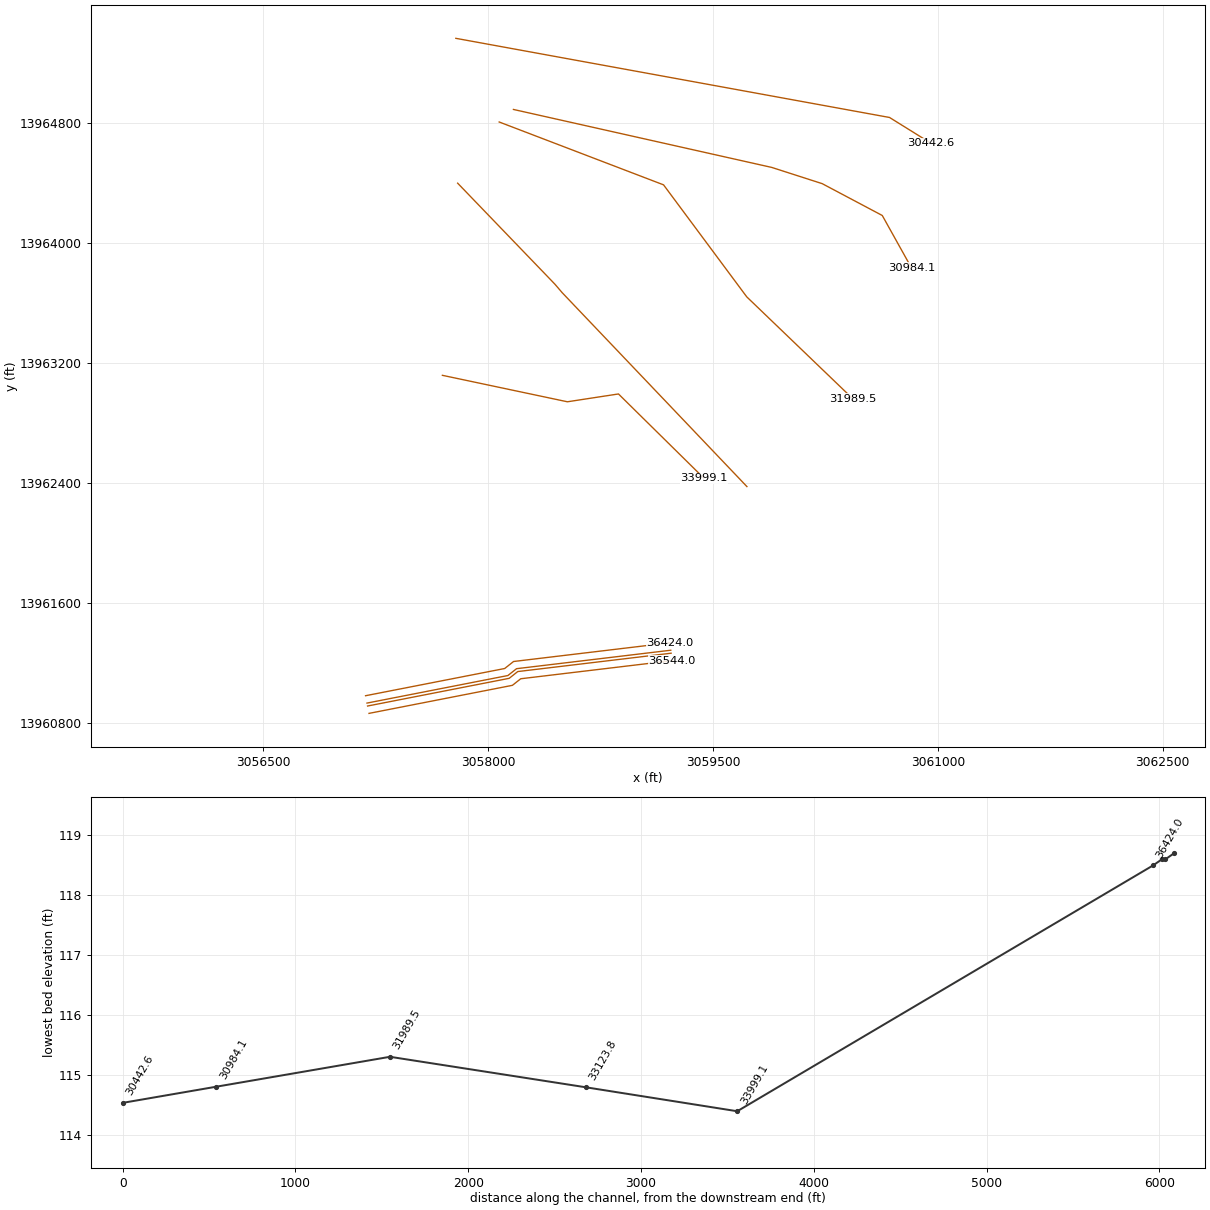
HEC-RAS study M100-00-00.prj: M100-00-00

--- M100-00-00.g01 (geometry) --- (continued)

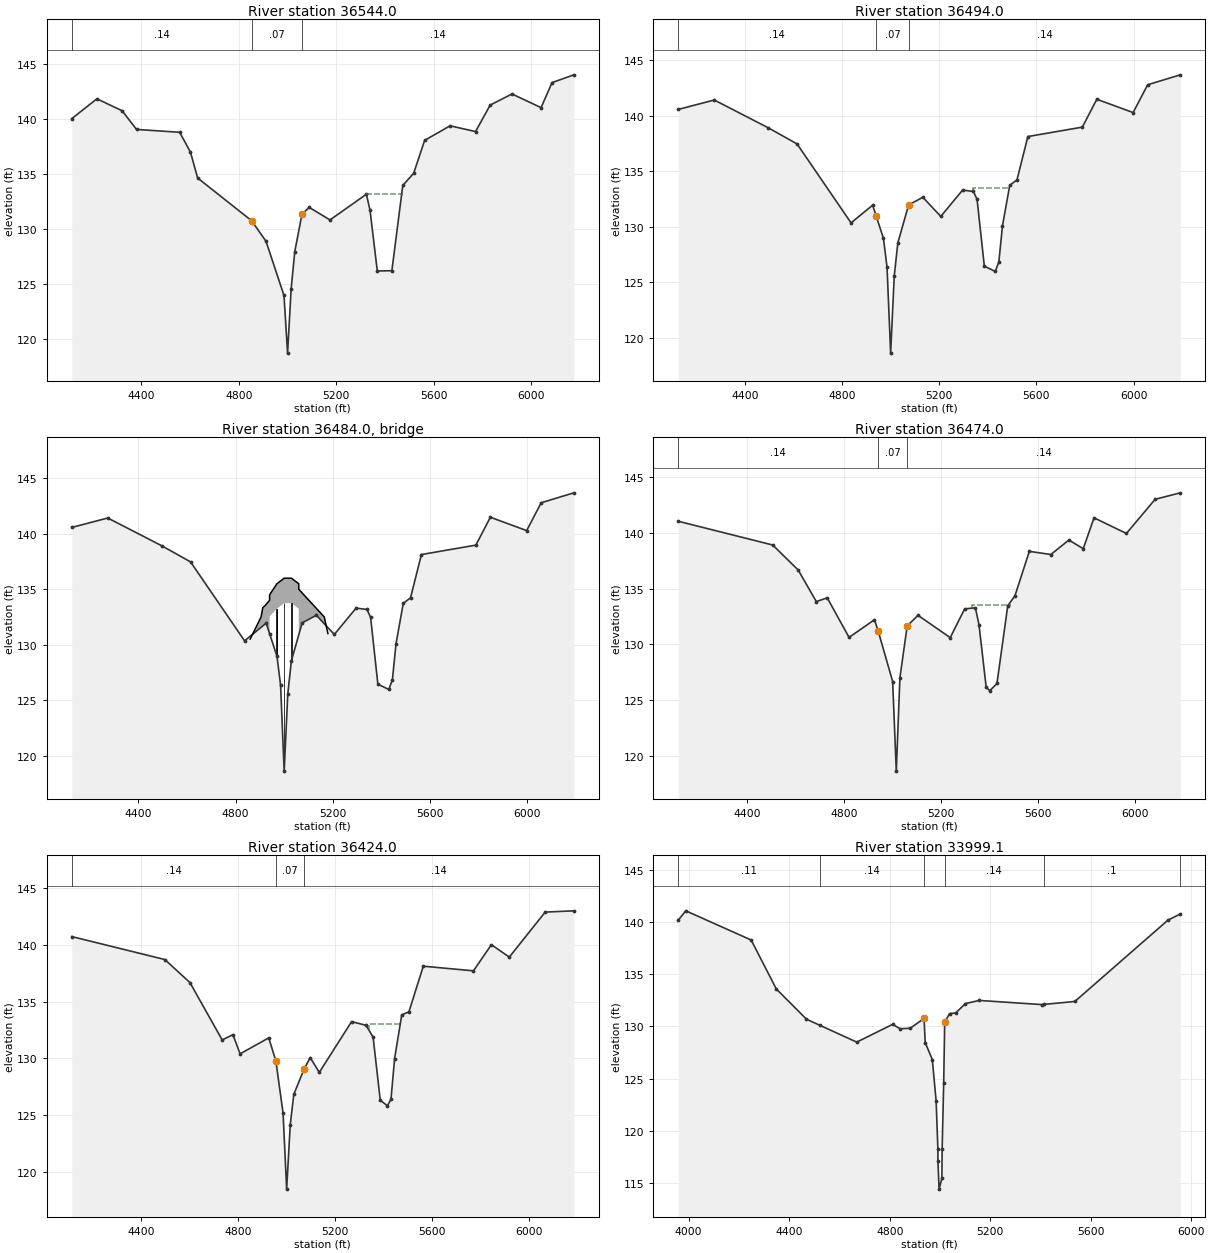
Type RM Length L Ch R = 1 ,36544.0 ,50.02,50.02,50.02
BEGIN DESCRIPTION:
Cross-Section Added by RGME
END DESCRIPTION:
XS GIS Cut Line= 5
      3057204.26     13960861.94     3058000.066      13961017.6
     3058161.067     13961049.09     3058216.506     13961092.94
     3059225.918     13961213.76
#Sta/Elev= 30
 4113.61140.03444217.022141.83524320.434140.74844379.527139.04944556.805138.7906
4601.125136.98454630.671134.62984852.268 130.7454911.361128.87624985.227123.9486
    5000   118.75014.773124.55835029.546127.93555059.092131.33145088.639131.9613
5174.246130.8177 5323.73133.15595338.679131.68715368.576126.1701 5428.37126.1985
5473.215133.95355518.061135.06835562.906138.05475667.545139.38135772.185 138.855
5831.979141.26335921.669142.27496041.257141.03276086.103 143.3076175.793144.0175
#Mann= 3 ,-1 , 0
 4113.61     .14       04852.268     .07       05059.092     .14       0
#XS Ineff= 1 ,-1
 5323.73 5473.21  133.21
Permanent Ineff=
       T
Bank Sta=4852.268,5059.092
XS Rating Curve= 0
Exp/Cntr=.5,.3

Type RM Length L Ch R = 1 ,36494.0 ,20,20,20
BEGIN DESCRIPTION:
Cross-Section Added by RGME
END DESCRIPTION:
XS GIS Cut Line= 5
      3057194.66     13960911.01     3057990.468     13961066.67
     3058139.564     13961095.83     3058196.555     13961140.91
     3059219.975     13961263.41
#Sta/Elev= 30
4125.735140.56634273.916141.41664496.187138.91314614.731137.45854837.001130.3442
 4925.91131.93334940.728 130.9384970.364128.94874985.182 126.345    5000   118.6
5014.818125.54995029.636 128.545 5074.09131.96035132.488132.64815206.355130.9216
5295.983133.29175340.797133.17495355.735132.45565385.611126.44045430.425 125.963
5445.363126.81875460.301130.07465490.177133.72465520.053134.22315564.867138.1234
5788.937138.97265848.688 141.4845998.068140.2839 6057.82142.79026192.262143.6861
#Mann= 3 ,-1 , 0
4125.735     .14       04940.728     .07       0 5074.09     .14       0
#XS Ineff= 1 ,-1
  5340.8 5490.18   133.5
Permanent Ineff=
       T
Bank Sta=4940.728,5074.09
XS Rating Curve= 0
Exp/Cntr=.5,.3

Type RM Length L Ch R = 3 ,36484.0 ,,,
BEGIN DESCRIPTION:
WWTP Bridge - Added by RGME
END DESCRIPTION:
Bridge Culvert--1,0,-1,-1, 0
Deck Dist Width WeirC Skew NumUp NumDn MinLoCord MaxHiCord MaxSubmerge Is_Ogee
1,18,2.6,0, 14, 14, , , .95, 0, 0,0,,
    4860    4905    4912    4920    4940    4940    4970    5000    5030    5060
    5060    5081    5165    5180
   130.5   132.5  133.34  133.49     134  134.49  135.49  135.99  135.99  135.49
     135  134.49   132.5     131
      88      88      88      88      88  132.54  133.24  133.74  133.74  133.24
      88      88      88      88
    4860    4905    4912    4920    4940    4940    4970    5000    5030    5060
    5060    5081    5165    5180
   130.5   132.5  133.34  133.49     134  134.49  135.49  135.99  135.99  135.49
     135  134.49   132.5     131
      88      88      88      88      88  132.54  133.24  133.74  133.74  133.24
      88      88      88      88
Pier Skew, UpSta & Num, DnSta & Num=  ,4968.7, 2 ,4968.7, 2 , 0 , 0 , 0 ,,
    1.33    1.33
      88  133.24
    1.33    1.33
      88  133.24
Pier Skew, UpSta & Num, DnSta & Num=  ,4970, 2 ,4970, 2 , 0 , 0 , 0 ,,
    1.17    1.17
      88  133.24
    1.17    1.17
      88  133.24
Pier Skew, UpSta & Num, DnSta & Num=  ,5000, 2 ,5000, 2 , 0 , 0 , 0 ,,
    1.16    1.16
      88  133.74
    1.16    1.16
      88  133.74
Pier Skew, UpSta & Num, DnSta & Num=  ,5030, 2 ,5030, 2 , 0 , 0 , 0 ,,
    1.17    1.17
      88  133.74
    1.17    1.17
      88  133.74
BR Coef=-1 , 0 , 0 ,, 0 ,,,.8,-1,,0,
WSPro=,,,, 1 ,,,, 0 ,,,, 0 ,,,,-1 ,-1 ,-1 , 0 , 0 , 0 , 0 , 0
BC Design=,, 0 ,, 0 ,,,,,,
BC HTab HWMax=143.6861

Type RM Length L Ch R = 1 ,36474.0 ,50,50,50
BEGIN DESCRIPTION:
Cross-Section Added by RGME
END DESCRIPTION:
XS GIS Cut Line= 5
      3057190.82     13960930.63     3057986.628      13961086.3
     3058130.963     13961114.53     3058188.574     13961160.09
     3059217.598     13961283.27
#Sta/Elev= 30
4116.853141.04184506.037138.90854610.816136.6645 4685.66 133.8254730.565134.1646
4820.377130.61194925.157132.19634940.125 131.204    5000126.64925014.969   118.6
5029.938126.99655059.875131.63445104.234132.59735237.161 130.5895296.388133.1698
5340.808133.27325355.614131.74185385.228126.13515400.035125.82245429.648126.4711
5474.068133.45135503.682134.34685562.909138.3393 5651.75138.05575725.783139.3558
 5785.01138.57715829.431141.35115962.691139.94636081.146143.01516184.793143.5951
#Mann= 3 ,-1 , 0
4116.853     .14       04940.125     .07       05059.875     .14       0
#XS Ineff= 1 ,-1
    5326 5488.88   133.5
Permanent Ineff=
       T
Bank Sta=4940.125,5059.875
XS Rating Curve= 0
Exp/Cntr=.5,.3

Type RM Length L Ch R = 1 ,36424.0 ,1963.72,2406.92,1729.5
BEGIN DESCRIPTION:
Cross-Section Added by RGME
END DESCRIPTION:
XS GIS Cut Line= 5
      3057181.22     13960979.71      3057977.03     13961135.37
      3058109.46     13961161.27     3058168.623     13961208.06
     3059211.656     13961332.91
#Sta/Elev= 30
4113.137140.72284497.444138.70194600.912136.67284733.941131.62654778.285132.0928
4807.847130.40294926.095131.80964955.657129.75664985.219125.1866    5000   118.5
5014.782124.12825029.563 126.8465071.735129.04175096.955130.07115134.784128.7734
5267.953133.23725327.139132.91935356.732131.88875386.325126.32815415.918125.8328
5430.715126.42135445.511129.98655475.104133.83545504.697134.10195563.883138.1174
5771.035137.70925845.018140.0092    5919138.91746066.965142.87786185.337142.9892
#Mann= 3 ,-1 , 0
4113.137     .14       04955.657     .07       05071.735     .14       0
#XS Ineff= 1 ,-1
 5341.94  5475.1     133
Permanent Ineff=
       T
Bank Sta=4955.657,5071.735
XS Rating Curve= 0
Exp/Cntr=.5,.3

Type RM Length L Ch R = 1 ,33999.1 ,819.76,875.3,192.74
BEGIN DESCRIPTION:
Cross Section 33999.1
Cross Section XS17
END DESCRIPTION:
XS GIS Cut Line= 4
      3057693.92      13963117.4      3058527.86      13962940.9
      3058868.66      13962993.1      3059437.98      13962431.8
#Sta/Elev= 30
  3958.9   140.2  3988.9   141.1  4248.9   138.3  4348.9   133.6  4468.9   130.7
  4523.3   130.1  4668.9   128.5  4811.3   130.2  4841.8  129.78  4881.4  129.83
  4936.5  130.77  4941.1  128.45  4969.3  126.83  4984.5  122.86  4991.5  118.25
  4991.6  117.08  4996.3  114.39  5007.4  115.42  5008.5  118.28  5014.6  124.61
  5018.6  130.42  5037.8  131.23  5062.3   131.3  5101.3   132.2  5156.1   132.5
  5406.1   132.1  5413.6  132.12  5536.1   132.4  5906.1   140.2  5955.6   140.8
#Mann= 6 ,-1 , 0
  3958.9     .11       0  4523.3     .14       0  4936.5     .07       0
  5018.6     .14       0  5413.6      .1       0  5955.6      .2       0
Bank Sta=4936.5,5018.6
XS Rating Curve= 0
Exp/Cntr=.3,.1

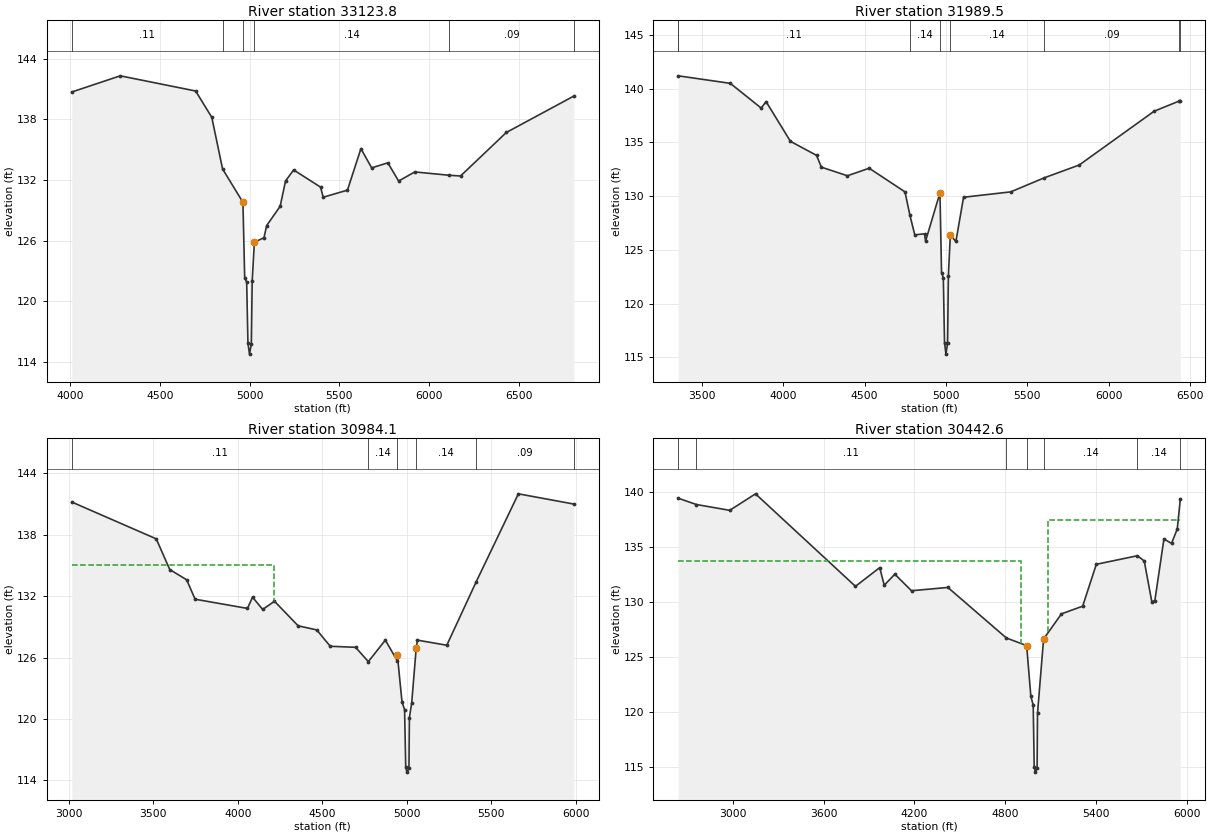
Type RM Length L Ch R = 1 ,33123.8 ,1003.95,1134.3,892.65
BEGIN DESCRIPTION:
Cross Section Xs16.5
END DESCRIPTION:
XS GIS Cut Line= 4
      3057795.66      13964399.4       3058443.6      13963726.5
      3058493.52      13963668.3      3059725.62      13962375.1
#Sta/Elev= 30
  4009.2   140.7  4279.2   142.3  4699.2   140.8  4789.2   138.2  4849.2   133.1
  4962.7   129.8  4972.5  122.36  4983.5  121.91  4990.7  115.87  4999.4  114.79
  5009.6  115.81  5014.3  122.02  5026.4  125.85    5080   126.3    5095   127.5
    5170   129.4    5200   131.9    5245     133    5395   131.3    5410   130.3
    5545     131    5620   135.1    5680   133.2    5770   133.7    5830   131.9
    5920   132.8  6112.4  132.47    6175   132.4    6430   136.7  6806.2   140.3
#Mann= 6 ,-1 , 0
  4009.2     .11       0  4849.2     .14       0  4962.7     .07       0
  5026.4     .14       0  6112.4     .09       0  6806.2      .2       0
Bank Sta=4962.7,5026.4
XS Rating Curve= 0
Exp/Cntr=.3,.1

Type RM Length L Ch R = 1 ,31989.5 ,489.57,1005.4,936.81
BEGIN DESCRIPTION:
Cross Section 31989.5
Cross Section XS16
Cross Section M100-00-00-X16
Located At: US HUFSMITH
END DESCRIPTION:
XS GIS Cut Line= 4
       3058072.8      13964807.6      3059169.36      13964388.3
      3059724.47       13963641.       3060432.3       13962961.
#Sta/Elev= 30
  3353.8   141.2  3673.8   140.5  3863.8   138.2  3893.8   138.8  4043.8   135.1
  4203.8   133.8  4233.8   132.7  4393.8   131.9  4527.8   132.6  4747.8   130.4
  4777.4  128.27  4807.8   126.4  4867.8   126.5  4874.4  125.82  4962.7  130.31
  4972.5  122.87  4983.5  122.42  4990.7  116.38  4999.4   115.3  5009.6  116.32
  5014.3  122.53  5026.4  126.36  5060.8  125.79  5107.8   129.9  5397.8   130.4
  5604.1  131.71  5818.8   132.9  6278.8   137.9  6431.2  138.84  6440.3   138.9
#Mann= 8 , 1 , 0
  3353.8      .2       0  3353.8     .11       0  4777.4     .14       0
  4962.7     .07       0  5026.4     .14       0  5604.1     .09       0
  6431.2      .1       0  6440.3      .2       0
Bank Sta=4962.7,5026.4
XS Rating Curve= 0
Exp/Cntr=.3,.1

Type RM Length L Ch R = 1 ,30984.1 ,479.2,541.5,524.7
BEGIN DESCRIPTION:
Cross Section 30984.1
Cross Section XS15.5
END DESCRIPTION:
XS GIS Cut Line= 5
      3058167.82      13964891.3      3059891.04      13964504.6
      3060227.82      13964396.3      3060628.76      13964183.8
       3060822.7      13963835.9
#Sta/Elev= 30
  3017.2   141.2  3517.2   137.6  3597.2   134.6  3697.2   133.6  3747.2   131.7
  4057.2   130.8  4087.2   131.9  4147.2   130.7  4217.2   131.5  4357.2   129.1
  4467.2   128.7  4547.2   127.1  4697.2     127  4772.6   125.6  4873.3   127.7
  4943.3   125.7  4944.1  126.29  4971.8  121.68  4987.3   120.9    4994  115.28
  5001.2   114.8    5013  115.17  5015.7  120.13  5029.3  121.57  5055.9  126.89
  5063.3   127.7    5237   127.2  5409.9  133.36  5660.8     142  5989.1     141
#Mann= 6 ,-1 , 0
  3017.2     .11       0  4772.6     .14       0  4944.1     .07       0
  5055.9     .14       0  5409.9     .09       0  5989.1      .2       0
#XS Ineff= 2 , 0
       0    4215     135               0
Permanent Ineff=
       F       F
Bank Sta=4944.1,5055.9
XS Rating Curve= 0
Exp/Cntr=.5,.3

Type RM Length L Ch R = 1 ,30442.6 ,67,67,67
BEGIN DESCRIPTION:
Upstream Section of Bridge/Culvert/Weir
END DESCRIPTION:
XS GIS Cut Line= 3
      3057783.66      13965365.8      3060677.11      13964837.8
      3060953.92      13964665.8
#Sta/Elev= 30
  2640.7   139.4  2760.8  138.83  2980.7   138.3  3150.8   139.8  3810.7   131.4
  3970.7   133.1  4000.7   131.5  4070.7   132.5  4180.7     131  4420.8   131.3
    4807  126.71  4940.9  126.02  4968.6  121.41  4984.1  120.63  4990.7  115.01
    4998  114.53  5009.8   114.9  5012.5  119.86  5052.7  126.62  5170.7   128.9
  5310.7   129.6  5400.7   133.4  5672.3  134.18  5717.2   133.7  5767.2     130
  5787.2   130.1  5847.2   135.7  5897.2   135.3    5935   136.6  5955.3   139.3
#Mann= 7 ,-1 , 0
  2640.7      .2       0  2760.8     .11       0    4807     .14       0
  4940.9     .07       0  5052.7     .14       0  5672.3     .14       0
  5955.3      .2       0
#XS Ineff= 2 , 0
       0    4905  133.67    5084       0   137.4
Permanent Ineff=
       F       F
Bank Sta=4940.9,5052.7
XS Rating Curve= 0
Exp/Cntr=.5,.3