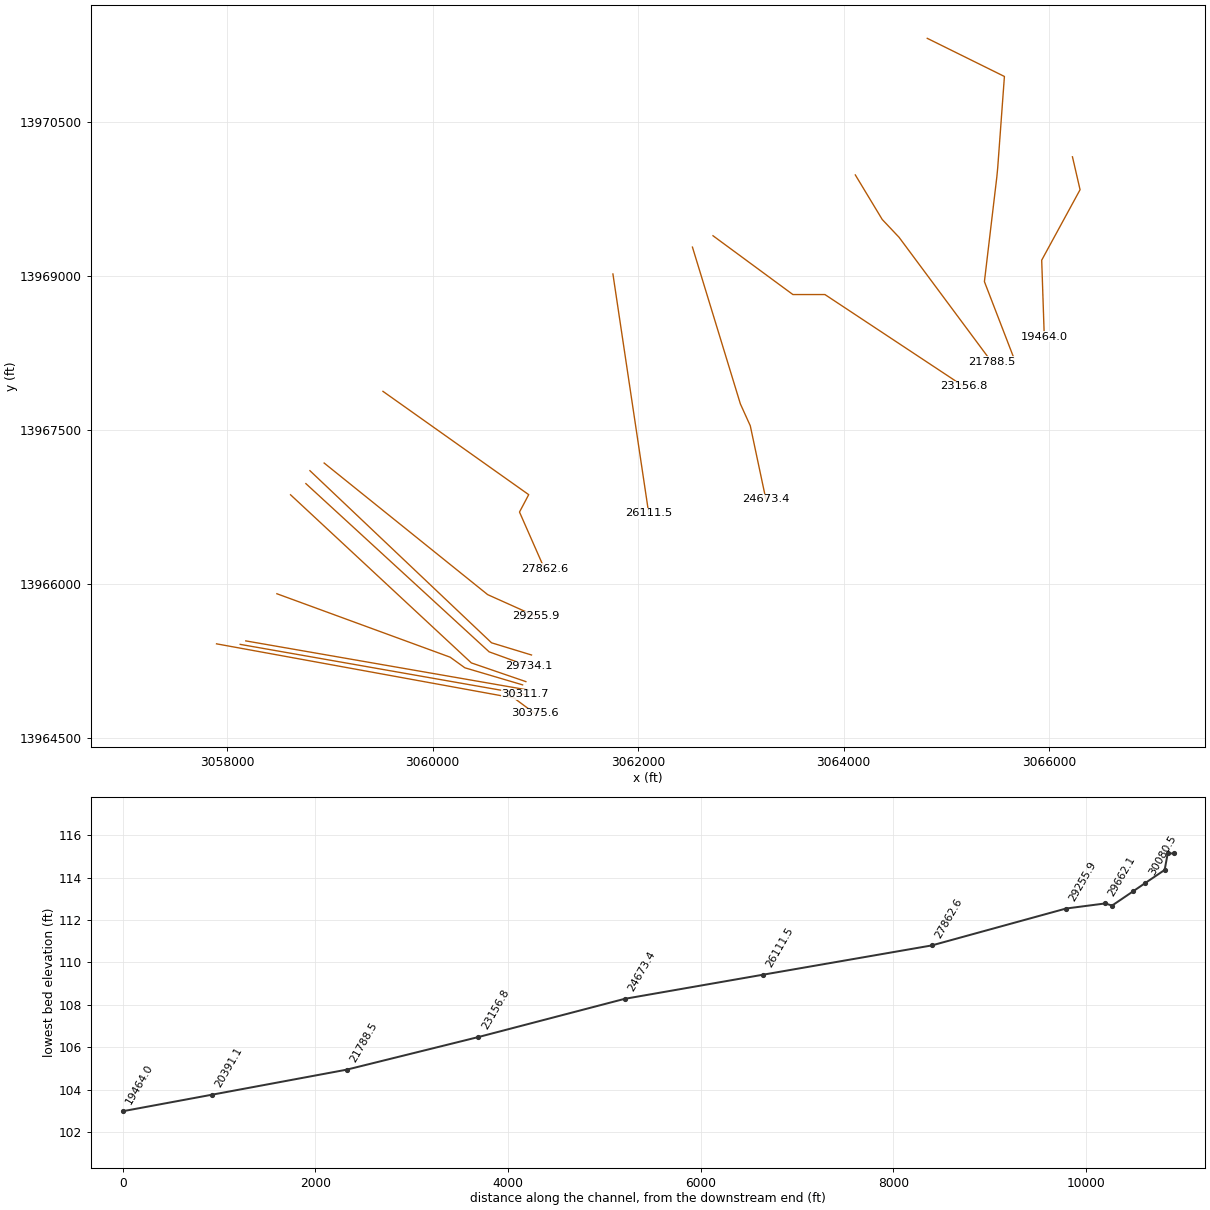
HEC-RAS study M100-00-00.prj: M100-00-00

--- M100-00-00.g01 (geometry) --- (continued)

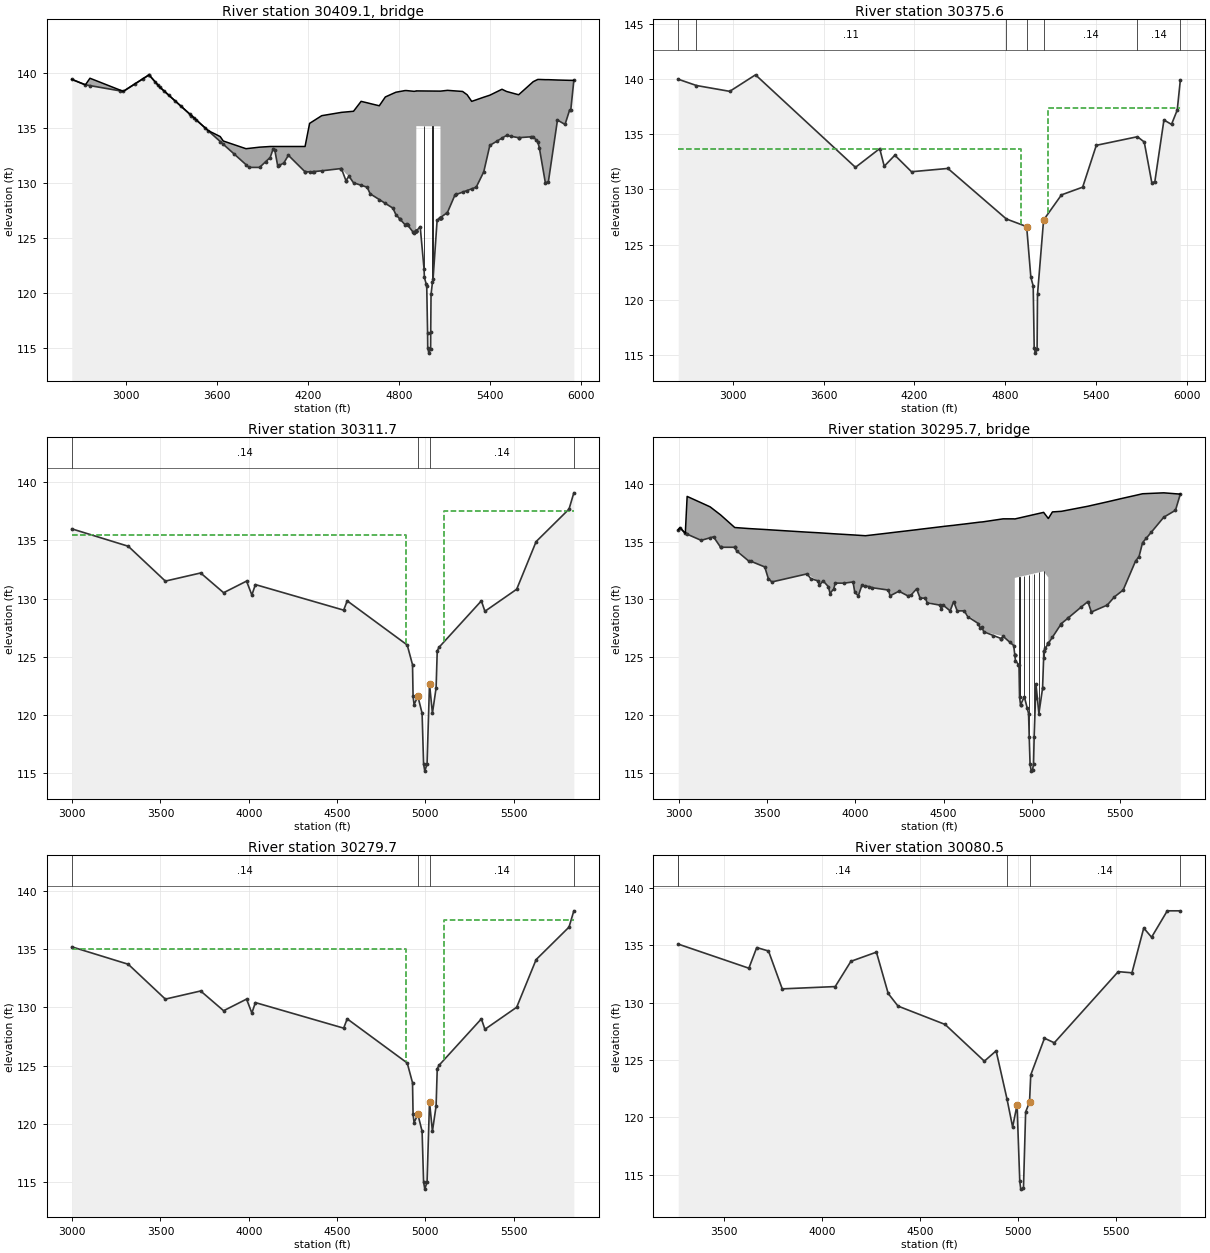
Type RM Length L Ch R = 3 ,30409.1 ,,,
BEGIN DESCRIPTION:
HUFSMITH KUYKENDAHL
Structure ID: M100-00-00-08
Cross Section 30409.1
END DESCRIPTION:
Node Name=Kuykend-Hufsmith
Bridge Culvert--1,0,-1,-1, 0
Deck Dist Width WeirC Skew NumUp NumDn MinLoCord MaxHiCord MaxSubmerge Is_Ogee
10,47,2.6,0, 60, 60, , , .95, 0, 1,1,,
  2640.7  2730.7  2760.8  2980.7  3150.7  3220.7  3540.8  3620.8  3640.8  3790.8
  3810.7  3880.7  3950.7  3970.7  3980.7  4000.7  4040.7  4070.7  4180.8  4210.8
  4290.8  4420.8  4500.7  4550.8  4590.7  4610.7  4670.8  4710.8  4760.7  4780.7
  4840.7  4850.7  4900.7 4915.11  4915.2  4915.6 5074.79  5074.9  5075.1  5120.7
  5170.7  5220.8  5250.8  5280.8  5310.7  5360.7  5400.7  5480.8  5510.7  5590.8
  5687.2  5717.2  5727.2  5767.2  5787.2  5847.2  5897.2  5927.2    5935  5955.3
   139.4   138.9   139.5  138.31  139.81  138.71  134.75   134.2   133.8   133.1
  133.13  133.24   133.3   133.3   133.3   133.3   133.3   133.3   133.3   135.4
   136.1   136.4   136.5   137.4  137.27   137.2     137   137.8  138.11  138.23
  138.38  138.38  138.31  138.34  138.34  138.35  138.33  138.33  138.33   138.4
  138.35   138.3     138   137.4  137.54  137.78  137.96   138.5   138.3     138
  139.19  139.39  139.39  139.37  139.37  139.34  139.32  139.31  139.31   139.3
   139.4   138.9  138.83   138.3   139.8   138.7  134.74  133.75   133.5  131.65
   131.4   131.4   132.3   133.1     133   131.5   131.8   132.5     131     131
  131.09   131.3     130  129.78   129.6     129  128.48  128.13   127.7   127.1
   126.2   126.3   125.4  125.62  135.14  135.15  135.13  126.84  126.84   127.3
   128.9  129.15   129.3  129.45   129.6     131   133.4  134.06   134.3   134.1
   134.2   133.7   133.2     130   130.1   135.7   135.3   136.6   136.6   139.3
  2640.7  2730.7  2980.7  3150.7  3220.7  3640.8  3710.8  3790.8  3810.7  3880.7
  3950.7  3970.7  3980.7  4000.7  4040.7  4070.7  4180.8  4210.8  4290.8  4420.8
  4500.7  4550.8  4590.7  4610.7  4670.8  4710.8  4760.7  4780.7  4840.7  4850.7
  4900.7 4915.11  4915.2  4915.6 5074.79  5074.9  5075.1  5120.7  5170.7  5220.8
  5250.8  5280.8  5310.7  5360.7  5400.7  5450.8  5480.8  5510.7  5590.8  5687.2
    5704  5717.2  5727.2  5767.2  5787.2  5847.2  5897.2  5927.2    5935  5955.3
  140.01  139.51  138.91  140.41  139.31  134.11   133.4   133.1  133.13  133.24
   133.3  133.71  133.61   133.3   133.3   133.3   133.3   135.4   136.1   136.4
   136.5   137.4  137.27   137.2     137   137.8  138.11  138.23  138.38  138.38
  138.31  138.34  138.34  138.35  138.33  138.33  138.33   138.4  138.35   138.3
     138   137.4  137.54  137.78  137.96   138.2   138.5   138.3     138  139.19
   139.4  139.39  139.39  139.37  139.37  139.34  139.32  139.31  139.31  139.91
  140.01  139.51  138.91  140.41  139.31  134.11  133.25  132.26  132.01  132.01
  132.91  133.71  133.61  132.11  132.41  133.11  131.61  131.61   131.7  131.91
  130.61  130.39  130.21  129.61  129.09  128.74  128.31  127.71  126.81  126.91
  126.01  126.23  135.75  135.76  135.74  127.45  127.45  127.91  129.51  129.76
  129.91  130.06  130.21  131.61  134.01  134.42  134.67  134.91  134.71  134.81
  134.53  134.31  133.81  130.61  130.71  136.31  135.91  137.21  137.21  139.91
Pier Skew, UpSta & Num, DnSta & Num=  ,4968.5, 2 ,4968.5, 2 , 0 , 0 , 0 ,,
     1.5     1.5
  120.38  136.17
     1.5     1.5
  120.99  136.78
Pier Skew, UpSta & Num, DnSta & Num=  ,5021.7, 2 ,5021.7, 2 , 0 , 0 , 0 ,,
     1.5     1.5
  119.85  136.16
     1.5     1.5
  120.46  136.77
Abutment Skew #Up #Dn= , 2 , 2
    4915  4916.5
  135.14  125.64
    4915  4916.5
  135.75  126.25
Abutment Skew #Up #Dn= , 2 , 2
  5073.9 5074.99
  126.83  135.13
  5073.9 5074.99
  127.44  135.74
BR Coef= 1 , 1 , 1 ,1.25, 0 ,,,.8,0,2,0,
WSPro=,,,, 1 ,,,, 0 ,,,, 0 ,,,,-1 ,-1 ,-1 , 0 , 0 , 0 , 0 , 0
BR U #Sta/Elev= 116
  2640.7   139.4  2730.7   138.9  2760.8  138.83  2960.8  138.35  2980.7   138.3
  3060.8  139.01  3110.8  139.45  3150.7   139.8  3150.8   139.8  3190.8  139.17
  3210.8  138.86  3220.7   138.7  3250.8  138.33  3280.8  137.96  3320.8  137.46
  3360.8  136.97  3420.8  136.22  3430.8   136.1  3450.8  135.85  3460.8  135.73
  3520.8  134.99  3540.8  134.74  3620.8  133.75  3640.8   133.5  3710.8  132.64
  3790.8  131.65  3810.7   131.4  3880.7   131.4  3920.8  131.92  3950.7   132.3
  3970.7   133.1  3980.7     133  4000.7   131.5  4010.8  131.58  4040.7   131.8
  4070.7   132.5  4180.7     131  4180.8     131  4210.8     131  4230.7     131
  4240.8  131.02  4290.8  131.09  4420.7   131.3  4420.8   131.3  4450.7   130.2
  4450.8   130.2  4470.7   130.6  4500.7     130  4550.8  129.78  4590.7   129.6
  4610.7     129  4670.8  128.48  4710.8  128.13  4760.7   127.7  4780.7   127.1
    4807  126.71  4807.3   126.7  4840.7   126.2  4850.7   126.3  4858.8  126.15
  4893.3  125.53  4900.7   125.4 4915.11  125.62  4915.2  125.62  4915.3  125.63
  4915.5  125.63  4915.6  125.63  4916.5  125.64  4940.9  126.02  4966.5  122.16
  4968.6  121.41  4980.7   120.8  4984.1  120.63  4989.7  116.39  4990.7  115.01
    4998  114.53  5009.8   114.9  5010.4  116.43  5012.5  119.86  5021.8  120.95
  5026.1   121.3  5052.7  126.62  5073.9  126.83 5074.79  126.84  5074.9  126.84
    5075  126.84  5075.1  126.84  5075.3  126.85  5119.6  127.29  5120.7   127.3
  5170.7   128.9  5178.6  128.94  5220.8  129.15  5250.8   129.3  5280.8  129.45
  5310.7   129.6  5360.7     131  5400.7   133.4  5450.8  133.81  5480.8  134.06
  5510.7   134.3  5540.8  134.22  5590.7   134.1  5590.8   134.1  5672.3  134.18
  5687.2   134.2    5704  133.92  5717.2   133.7  5727.2   133.2  5767.2     130
  5787.2   130.1  5847.2   135.7  5897.2   135.3  5927.2   136.6    5935   136.6
  5955.3   139.3
BR U #Mann= 6
  2640.7      .2  2760.8     .11    4807     .14  4940.9     .06  5052.7     .14
  5672.3     .14
BR U Banks=4940.9,5052.7
BR D #Sta/Elev= 116
  2640.7  140.01  2730.7  139.51  2760.8  139.44  2960.8  138.96  2980.7  138.91
  3060.8  139.62  3110.8  140.06  3150.7  140.41  3150.8  140.41  3190.8  139.78
  3210.8  139.47  3220.7  139.31  3250.8  138.94  3280.8  138.57  3320.8  138.07
  3360.8  137.58  3420.8  136.83  3430.8  136.71  3450.8  136.46  3460.8  136.34
  3520.8   135.6  3540.8  135.35  3620.8  134.36  3640.8  134.11  3710.8  133.25
  3790.8  132.26  3810.7  132.01  3880.7  132.01  3920.8  132.53  3950.7  132.91
  3970.7  133.71  3980.7  133.61  4000.7  132.11  4010.8  132.19  4040.7  132.41
  4070.7  133.11  4180.7  131.61  4180.8  131.61  4210.8  131.61  4230.7  131.61
  4240.8  131.63  4290.8   131.7  4420.7  131.91  4420.8  131.91  4450.7  130.81
  4450.8  130.81  4470.7  131.21  4500.7  130.61  4550.8  130.39  4590.7  130.21
  4610.7  129.61  4670.8  129.09  4710.8  128.74  4760.7  128.31  4780.7  127.71
    4807  127.32  4807.3  127.31  4840.7  126.81  4850.7  126.91  4858.8  126.76
  4893.3  126.14  4900.7  126.01 4915.11  126.23  4915.2  126.23  4915.3  126.24
  4915.5  126.24  4915.6  126.24  4916.5  126.25  4940.9  126.63  4966.5  122.77
  4968.6  122.02  4980.7  121.41  4984.1  121.24  4989.7     117  4990.7  115.62
    4998  115.14  5009.8  115.51  5010.4  117.04  5012.5  120.47  5021.8  121.56
  5026.1  121.91  5052.7  127.23  5073.9  127.44 5074.79  127.45  5074.9  127.45
    5075  127.45  5075.1  127.45  5075.3  127.46  5119.6   127.9  5120.7  127.91
  5170.7  129.51  5178.6  129.55  5220.8  129.76  5250.8  129.91  5280.8  130.06
  5310.7  130.21  5360.7  131.61  5400.7  134.01  5450.8  134.42  5480.8  134.67
  5510.7  134.91  5540.8  134.83  5590.7  134.71  5590.8  134.71  5672.3  134.79
  5687.2  134.81    5704  134.53  5717.2  134.31  5727.2  133.81  5767.2  130.61
  5787.2  130.71  5847.2  136.31  5897.2  135.91  5927.2  137.21    5935  137.21
  5955.3  139.91
BR D #Mann= 6
  2640.7      .2  2760.8     .11    4807     .14  4940.9     .06  5052.7     .14
  5672.3     .14
BR D Banks=4940.9,5052.7
BC Design=,, 0 ,, 0 ,,,,,,
BC HTab HWMax=139.8

Type RM Length L Ch R = 1 ,30375.6 ,63.9,63.9,63.9
BEGIN DESCRIPTION:
Downstream Section of Bridge/Culvert/Weir
END DESCRIPTION:
XS GIS Cut Line= 3
      3057896.95       13965421.      3060792.47      13964893.5
      3060994.59      13964744.1
#Sta/Elev= 30
  2640.7  140.01  2760.8  139.44  2980.7  138.91  3150.8  140.41  3810.7  132.01
  3970.7  133.71  4000.7  132.11  4070.7  133.11  4180.7  131.61  4420.8  131.91
    4807  127.32  4940.9  126.63  4968.6  122.02  4984.1  121.24  4990.7  115.62
    4998  115.14  5009.8  115.51  5012.5  120.47  5052.7  127.23  5170.7  129.51
  5310.7  130.21  5400.7  134.01  5672.3  134.79  5717.2  134.31  5767.2  130.61
  5787.2  130.71  5847.2  136.31  5897.2  135.91    5935  137.21  5955.3  139.91
#Mann= 7 ,-1 , 0
  2640.7      .2       0  2760.8     .11       0    4807     .14       0
  4940.9     .07       0  5052.7     .14       0  5672.3     .14       0
  5955.3      .2       0
#XS Ineff= 2 , 0
       0    4905  133.67    5084       0   137.4
Permanent Ineff=
       F       F
Bank Sta=4940.9,5052.7
XS Rating Curve= 0
Exp/Cntr=.5,.3

Type RM Length L Ch R = 1 ,30311.7 ,32,32,32
BEGIN DESCRIPTION:
Upstream Section of Bridge/Culvert/Weir
END DESCRIPTION:
XS GIS Cut Line= 2
      3058127.68      13965415.7      3060901.53      13964928.1
#Sta/Elev= 30
  2997.5     136  3317.5   134.5  3527.5   131.5  3727.5   132.2  3857.5   130.5
  3987.5   131.5  4017.5   130.3  4037.5   131.2  4537.5     129  4557.5   129.8
  4897.5     126  4927.5   124.3  4930.6  121.57  4936.3  120.87  4957.8  121.58
  4981.7  120.12  4990.2  115.75    4997  115.14  5009.8  115.75  5023.7  122.66
  5040.2  120.12    5061   122.3  5067.5   125.5  5077.5   125.8  5317.5   129.8
  5337.5   128.9  5517.5   130.8  5627.5   134.9  5813.9   137.7  5841.2   139.1
#Mann= 4 ,-1 , 0
  2997.5     .14       0  4957.8     .07       0  5023.7     .14       0
  5841.2      .2       0
#XS Ineff= 2 , 0
       0    4892   135.5    5103       0  137.52
Permanent Ineff=
       F       F
Bank Sta=4957.8,5023.7
XS Rating Curve= 0
Exp/Cntr=.5,.3

Type RM Length L Ch R = 3 ,30295.7 ,,,
BEGIN DESCRIPTION:
UNION PACIFIC RAILROAD
Structure ID: M100-00-00-07
END DESCRIPTION:
Node Name=Union Pacific RR
Bridge Culvert--1,0,-1,-1, 0
Deck Dist Width WeirC Skew NumUp NumDn MinLoCord MaxHiCord MaxSubmerge Is_Ogee
10,12,2.6,0, 60, 60, , , .95, 0, 1,1,,
  2997.5  3007.5  3037.5  3047.9  3127.5  3177.9  3197.5  3237.5  3317.5  3397.5
  3487.5  3507.5  3527.5  3727.5  3787.5  3797.5  3817.5  3847.5  3857.5  3887.5
  3987.5  3997.5  4017.5  4037.5  4057.9  4187.5  4197.5  4247.5  4297.5  4347.5
  4367.5  4487.5  4497.5  4537.5  4557.5  4577.5  4617.5  4707.5  4717.5  4727.5
  4837.5  4897.5 4903.81  4903.9  5067.1 5093.49  5093.6  5093.7  5116.9  5167.5
  5317.5  5337.5  5427.5  5517.5  5587.5  5607.5  5627.5  5747.5  5813.9  5841.2
     136   136.2   135.7   138.9  138.35     138  137.77   137.3  136.21  136.12
  136.04  136.02     136  135.81  135.76  135.75  135.73   135.7  135.69  135.66
  135.57  135.56  135.54  135.52   135.5  135.73  135.75  135.84  135.93  136.02
  136.06  136.28   136.3  136.37   136.4  136.44  136.51  136.68  136.69  136.71
  136.96  136.96  136.95  136.95  137.52  136.99  136.99  136.99  137.56  137.61
  138.05  138.12  138.43  138.75  138.99  139.06  139.13  139.21  139.13   139.1
     136   136.2   135.7  135.63   135.1  135.32   135.4   134.5   134.5   133.3
   132.8   131.8   131.5   132.2   131.6   131.2   131.6   131.1   130.5   131.4
   131.5   130.6   130.3   131.2  131.15   130.8   130.3   130.7   130.3   130.9
   130.1   129.2   129.5     129   129.8     129     129   127.5   127.6   127.2
   126.8     126  125.18  131.85  132.42  131.89  126.18  126.18  126.72   127.9
   129.8   128.9   129.5   130.8   133.3   133.7   134.9   137.1   137.7   139.1
  2997.5  3007.5  3037.5  3047.9  3127.5  3177.9  3197.5  3237.5  3317.5  3397.5
  3487.5  3507.5  3527.5  3727.5  3787.5  3797.5  3817.5  3847.5  3857.5  3887.5
  3987.5  3997.5  4017.5  4037.5  4057.9  4187.5  4197.5  4247.5  4297.5  4347.5
  4367.5  4487.5  4497.5  4537.5  4557.5  4577.5  4617.5  4707.5  4717.5  4727.5
  4837.5  4897.5 4903.81  4903.9  5067.1 5093.49  5093.6  5093.7  5116.9  5167.5
  5317.5  5337.5  5427.5  5517.5  5587.5  5607.5  5627.5  5747.5  5813.9  5841.2
     136   136.2   135.7   138.9  138.35     138  137.77   137.3  136.21  136.12
  136.04  136.02     136  135.81  135.76  135.75  135.73   135.7  135.69  135.66
  135.57  135.56  135.54  135.52   135.5  135.73  135.75  135.84  135.93  136.02
  136.06  136.28   136.3  136.37   136.4  136.44  136.51  136.68  136.69  136.71
  136.96  136.96  136.95  136.95  137.52  136.99  136.99  136.99  137.56  137.61
  138.05  138.12  138.43  138.75  138.99  139.06  139.13  139.21  139.13   139.1
  135.25  135.45  134.95  134.88  134.35  134.57  134.65  133.75  133.75  132.55
  132.05  131.05  130.75  131.45  130.85  130.45  130.85  130.35  129.75  130.65
  130.75  129.85  129.55  130.45   130.4  130.05  129.55  129.95  129.55  130.15
  129.35  128.45  128.75  128.25  129.05  128.25  128.25  126.75  126.85  126.45
  126.05  125.25  124.43  131.85  132.42  131.89  125.43  125.43  125.97  127.15
  129.05  128.15  128.75  130.05  132.55  132.95  134.15  136.35  136.95  138.35
Pier Skew, UpSta & Num, DnSta & Num=  ,4930.6, 2 ,4930.6, 2 , 0 , 0 , 0 ,,
     1.5     1.5
  120.48  133.16
     1.5     1.5
  119.73  132.41
Pier Skew, UpSta & Num, DnSta & Num=  ,4957.8, 2 ,4957.8, 2 , 0 , 0 , 0 ,,
     1.5     1.5
  120.53   133.2
     1.5     1.5
  119.78  132.45
Pier Skew, UpSta & Num, DnSta & Num=  ,4985.4, 2 ,4985.4, 2 , 0 , 0 , 0 ,,
     1.5     1.5
  116.76  133.25
     1.5     1.5
  116.01   132.5
Pier Skew, UpSta & Num, DnSta & Num=  ,5013.4, 2 ,5013.4, 2 , 0 , 0 , 0 ,,
     1.5     1.5
  116.62  133.32
     1.5     1.5
  115.87  132.57
Pier Skew, UpSta & Num, DnSta & Num=  ,5040.2, 2 ,5040.2, 2 , 0 , 0 , 0 ,,
     1.5     1.5
   119.2  133.37
     1.5     1.5
  118.45  132.62
Pier Skew, UpSta & Num, DnSta & Num=  ,5067.1, 2 ,5067.1, 2 , 0 , 0 , 0 ,,
     1.5     1.5
  123.62  133.42
     1.5     1.5
  122.87  132.67
Abutment Skew #Up #Dn= , 2 , 2
  4903.7  4936.3
  131.85  120.87
  4903.7  4936.3
   131.1  120.12
Abutment Skew #Up #Dn= , 2 , 2
    5061 5093.69
   122.3  131.89
    5061 5093.69
  121.55  131.14
BR Coef= 1 , 1 , 1 ,1.25, 0 ,,,.8,0,2,0,
WSPro=,,,, 1 ,,,, 0 ,,,, 0 ,,,,-1 ,-1 ,-1 , 0 , 0 , 0 , 0 , 0
BR U #Sta/Elev= 110
  2997.5     136  3007.5   136.2  3037.5   135.7  3047.9  135.63  3127.5   135.1
  3177.9  135.32  3197.5   135.4  3237.5   134.5  3237.9   134.5  3317.5   134.5
  3317.9  134.49  3327.5   134.2  3397.5   133.3  3407.5   133.3  3487.5   132.8
  3507.5   131.8  3527.5   131.5  3727.5   132.2  3747.5   131.8  3787.5   131.6
  3797.5   131.2  3817.5   131.6  3847.5   131.1  3857.5   130.5  3877.5   130.9
  3887.5   131.4  3937.5   131.4  3987.5   131.5  3997.5   130.6  4017.5   130.3
  4037.5   131.2  4057.9  131.15  4077.5   131.1  4097.5     131  4187.5   130.8
  4197.5   130.3  4247.5   130.7  4297.5   130.3  4317.5   130.4  4347.5   130.9
  4367.5   130.1  4397.5   130.1  4407.5   129.7  4477.5   129.5  4487.5   129.2
  4497.5   129.5  4537.5     129  4557.5   129.8  4577.5     129  4617.5     129
  4637.5   128.5  4697.5   127.9  4707.5   127.5  4717.5   127.6  4727.5   127.2
  4781.8  126.87  4826.2  126.61  4827.5   126.6  4837.5   126.8  4873.9  126.31
  4897.5     126  4903.7  125.19 4903.81  125.18  4903.9  125.17  4907.5   124.7
  4924.7  124.36  4927.5   124.3  4930.6  121.57  4936.2  120.88  4936.3  120.87
  4957.8  121.58  4974.3  120.57  4981.7  120.12  4985.4  118.13  4990.2  115.75
    4997  115.14  5004.7  115.28  5009.8  115.75  5013.4  118.11    5021  121.47
  5023.7  122.66  5040.2  120.12  5060.9  122.29    5061   122.3  5067.1  124.94
  5067.5   125.5  5069.5  125.56  5077.5   125.8 5093.49  126.17  5093.6  126.18
  5093.7  126.18  5116.9  126.72  5163.4   127.8  5167.5   127.9  5207.5   128.4
  5207.9  128.41  5277.5   129.3  5317.5   129.8  5337.5   128.9  5427.5   129.5
  5467.5   130.2  5517.5   130.8  5587.5   133.3  5607.5   133.7  5627.5   134.9
  5647.9  135.27  5677.9  135.82  5747.5   137.1  5813.9   137.7  5841.2   139.1
BR U #Mann= 3
  2997.5     .14  4957.8     .06  5023.7     .14
BR U Banks=4957.8,5023.7
BR D #Sta/Elev= 110
  2997.5  135.25  3007.5  135.45  3037.5  134.95  3047.9  134.88  3127.5  134.35
  3177.9  134.57  3197.5  134.65  3237.5  133.75  3237.9  133.75  3317.5  133.75
  3317.9  133.74  3327.5  133.45  3397.5  132.55  3407.5  132.55  3487.5  132.05
  3507.5  131.05  3527.5  130.75  3727.5  131.45  3747.5  131.05  3787.5  130.85
  3797.5  130.45  3817.5  130.85  3847.5  130.35  3857.5  129.75  3877.5  130.15
  3887.5  130.65  3937.5  130.65  3987.5  130.75  3997.5  129.85  4017.5  129.55
  4037.5  130.45  4057.9   130.4  4077.5  130.35  4097.5  130.25  4187.5  130.05
  4197.5  129.55  4247.5  129.95  4297.5  129.55  4317.5  129.65  4347.5  130.15
  4367.5  129.35  4397.5  129.35  4407.5  128.95  4477.5  128.75  4487.5  128.45
  4497.5  128.75  4537.5  128.25  4557.5  129.05  4577.5  128.25  4617.5  128.25
  4637.5  127.75  4697.5  127.15  4707.5  126.75  4717.5  126.85  4727.5  126.45
  4781.8  126.12  4826.2  125.86  4827.5  125.85  4837.5  126.05  4873.9  125.56
  4897.5  125.25  4903.7  124.44 4903.81  124.43  4903.9  124.42  4907.5  123.95
  4924.7  123.61  4927.5  123.55  4930.6  120.82  4936.2  120.13  4936.3  120.12
  4957.8  120.83  4974.3  119.82  4981.7  119.37  4985.4  117.38  4990.2     115
    4997  114.39  5004.7  114.53  5009.8     115  5013.4  117.36    5021  120.72
  5023.7  121.91  5040.2  119.37  5060.9  121.54    5061  121.55  5067.1  124.19
  5067.5  124.75  5069.5  124.81  5077.5  125.05 5093.49  125.42  5093.6  125.43
  5093.7  125.43  5116.9  125.97  5163.4  127.05  5167.5  127.15  5207.5  127.65
  5207.9  127.66  5277.5  128.55  5317.5  129.05  5337.5  128.15  5427.5  128.75
  5467.5  129.45  5517.5  130.05  5587.5  132.55  5607.5  132.95  5627.5  134.15
  5647.9  134.52  5677.9  135.07  5747.5  136.35  5813.9  136.95  5841.2  138.35
BR D #Mann= 3
  2997.5     .14  4957.8     .06  5023.7     .14
BR D Banks=4957.8,5023.7
BC Design=,, 0 ,, 0 ,,,,,,
BC HTab HWMax=139.1

Type RM Length L Ch R = 1 ,30279.7 ,279.3,199.2,132.7
BEGIN DESCRIPTION:
Downstream Section of Bridge/Culvert/Weir
END DESCRIPTION:
XS GIS Cut Line= 2
      3058181.92      13965449.6      3060933.87      13964970.9
#Sta/Elev= 30
  2997.5  135.22  3317.5  133.72  3527.5  130.72  3727.5  131.42  3857.5  129.72
  3987.5  130.72  4017.5  129.52  4037.5  130.42  4537.5  128.22  4557.5  129.02
  4897.5  125.22  4927.5  123.52  4930.6  120.79  4936.3  120.09  4957.8   120.8
  4981.7  119.34  4990.2  114.97    4997  114.36  5009.8  114.97  5023.7  121.88
  5040.2  119.34    5061  121.52  5067.5  124.72  5077.5  125.02  5317.5  129.02
  5337.5  128.12  5517.5  130.02  5627.5  134.12  5813.9  136.92  5841.2  138.32
#Mann= 4 ,-1 , 0
  2997.5     .14       0  4957.8     .07       0  5023.7     .14       0
  5841.2      .2       0
#XS Ineff= 2 , 0
       0    4892     135    5103       0  137.52
Permanent Ineff=
       F       F
Bank Sta=4957.8,5023.7
XS Rating Curve= 0
Exp/Cntr=.5,.3

Type RM Length L Ch R = 1 ,30080.5 ,170,125.4,92
BEGIN DESCRIPTION:
Cross Section 30080.5
Cross Section XS15.3
END DESCRIPTION:
XS GIS Cut Line= 4
      3058484.54      13965908.6      3060171.47      13965290.9
      3060314.02      13965187.9      3060876.33      13965021.6
#Sta/Elev= 30
  3267.3   135.1  3627.3     133  3667.3   134.8  3727.3   134.5  3797.3   131.2
  4067.3   131.4  4147.3   133.6  4277.3   134.4  4337.3   130.8  4387.3   129.7
  4627.3   128.1  4827.3   124.9  4887.3   125.8 4942.45  121.63 4971.45  119.16
 4993.95  121.09 5007.85  114.44 5012.95  113.75 5026.65  113.81 5037.75  120.47
 5057.55  121.34  5063.8   123.7  5133.8   126.9  5183.8   126.5  5509.6   132.7
  5579.6   132.6  5639.6   136.5  5679.6   135.7  5759.6     138    5826     138
#Mann= 5 , 1 , 0
  3267.3      .2       0  3267.3     .14       0 4942.45     .08       0
 5057.55     .14       0    5826      .2       0
#XS Ineff= 2 , 0
       0    4270     134               0
Permanent Ineff=
       F       F
Bank Sta=4993.95,5057.55
XS Rating Curve= 0
Exp/Cntr=.3,.1

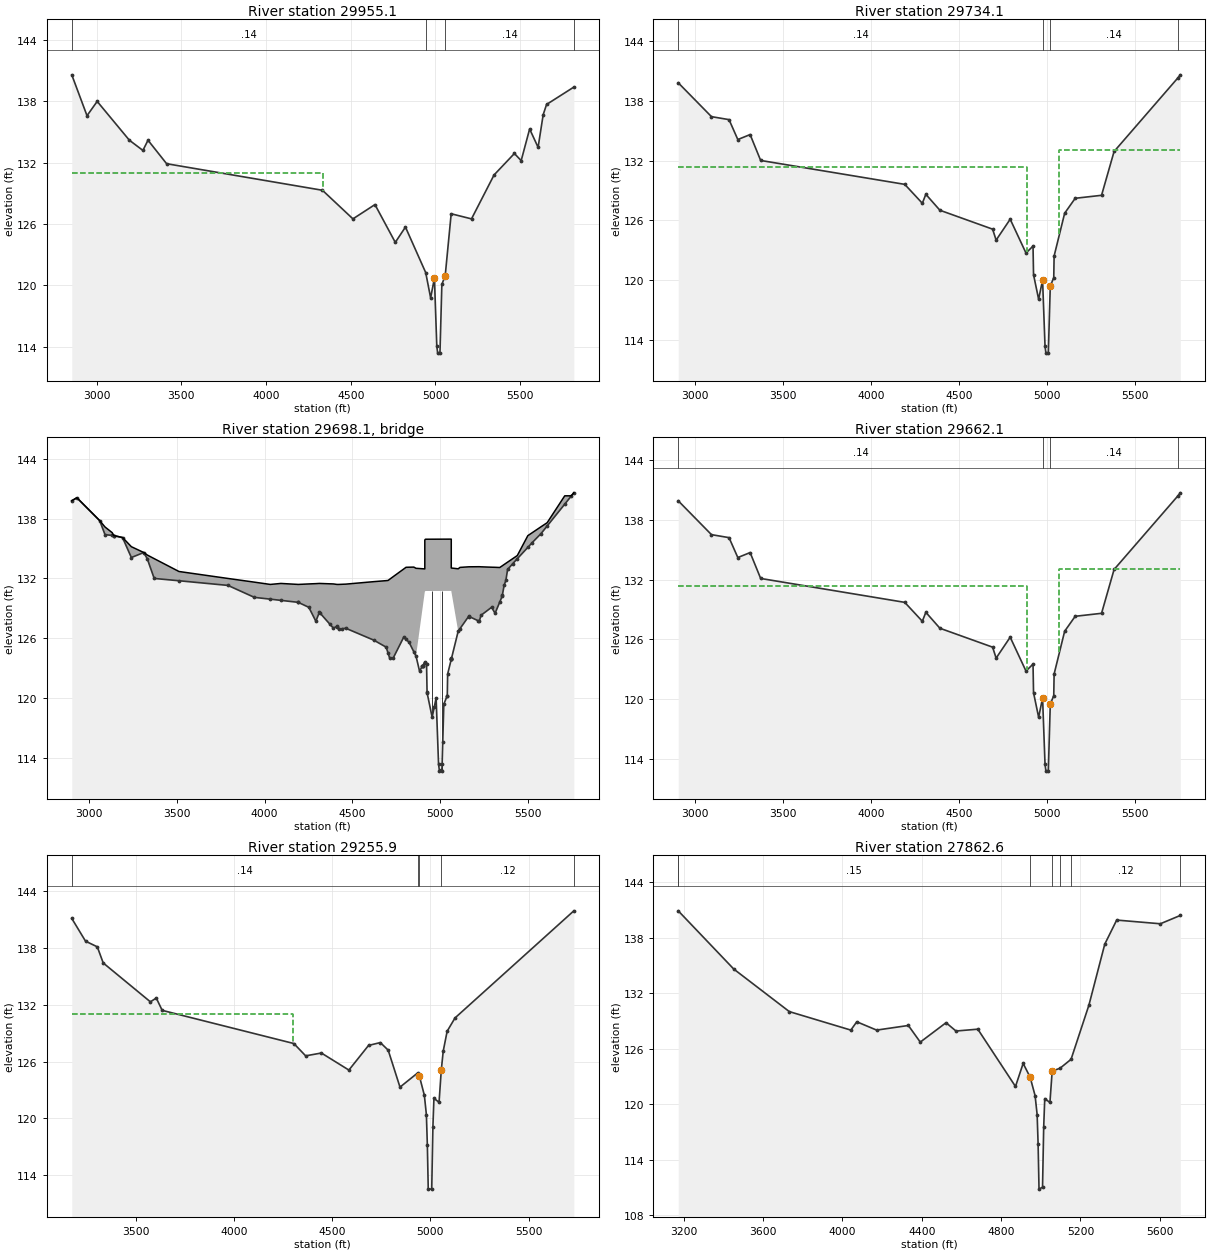
Type RM Length L Ch R = 1 ,29955.1 ,216.6,221,210.4
BEGIN DESCRIPTION:
Cross Section 29955.1
Cross Section XS15.2
END DESCRIPTION:
XS GIS Cut Line= 3
      3058617.43      13966871.9      3060377.38      13965235.4
      3060908.01      13965053.3
#Sta/Elev= 30
  2852.8   140.6  2942.8   136.6  3002.8     138  3192.8   134.2  3272.8   133.2
  3302.8   134.2  3412.8   131.9  4332.8   129.3  4512.8   126.5  4642.8   127.9
  4762.8   124.2  4822.8   125.7 4942.45  121.24 4971.45  118.77 4993.95   120.7
 5007.85  114.05 5012.95  113.36 5026.65  113.42 5037.75  120.08 5057.55  120.95
  5092.8     127  5212.8   126.5    5346   130.8    5466   132.9    5506   132.2
    5556   135.3    5606   133.5    5636   136.7    5656   137.7    5817   139.4
#Mann= 4 ,-1 , 0
  2852.8     .14       0 4942.45     .08       0 5057.55     .14       0
    5817      .2       0
#XS Ineff= 2 , 0
       0    4335     131               0
Permanent Ineff=
       F       F
Bank Sta=4993.95,5057.55
XS Rating Curve= 0
Exp/Cntr=.5,.3

Type RM Length L Ch R = 1 ,29734.1 ,72,72,72
BEGIN DESCRIPTION:
Upstream Section of Bridge/Culvert/Weir
END DESCRIPTION:
XS GIS Cut Line= 3
      3058766.79      13966980.5      3060550.55      13965343.1
      3060933.12      13965204.5
#Sta/Elev= 30
  2902.5  139.83  3091.6  136.43  3191.6  136.13  3241.6  134.13  3311.6  134.63
  3371.6  132.03  4191.6  129.63  4291.6  127.73  4311.6  128.63  4391.6  127.03
  4691.6  125.13  4711.6  124.03  4791.6  126.13  4881.6  122.73  4921.6  123.43
  4924.5  120.56  4953.5  118.09    4976  120.02  4989.9  113.37    4995  112.68
  5008.7  112.74  5019.8   119.4  5039.6  120.27  5041.6  122.43  5101.6  126.73
  5161.6  128.23  5311.6  128.53  5382.9  132.93  5744.9   140.3  5759.8  140.63
#Mann= 4 ,-1 , 0
  2902.5     .14       0    4976     .08       0  5019.8     .14       0
  5744.9      .2       0
#XS Ineff= 2 , 0
       0    4887   131.4    5072       0  133.05
Permanent Ineff=
       F       F
Bank Sta=4976,5019.8
XS Rating Curve= 0
Exp/Cntr=.5,.3

Type RM Length L Ch R = 3 ,29698.1 ,,,
BEGIN DESCRIPTION:
KUYKENDAHL
Structure ID: M100-00-00-06
END DESCRIPTION:
Node Name=Kuykendahl
Bridge Culvert--1,0,-1,-1, 0
Deck Dist Width WeirC Skew NumUp NumDn MinLoCord MaxHiCord MaxSubmerge Is_Ogee
10,52,2.6,0, 58, 57, , , .95, 0, 1,1,,
  2902.5  2931.6  3061.6  3091.6  3132.5  3141.6  3191.6  3241.6  3311.6  3331.6
  3371.6  3512.5  3791.6  3941.6  4032.5  4092.5  4191.6  4251.6  4291.6  4311.6
  4391.6  4411.6  4421.6  4461.6  4621.6  4691.6  4702.5  4711.6  4731.6  4791.6
  4804.7  4821.6  4849.2  4861.6  4911.6  4911.6    4915 5062.19  5062.2  5101.6
    5112  5161.6  5221.6  5231.6  5291.6  5311.6    5338  5351.6  5362.9  5372.9
  5382.9    5438    5498  5572.9    5608    5708  5744.9  5759.8
   139.8  140.11  137.81  137.17   136.6  136.31  136.11  135.19  134.61  134.36
  133.99   132.7     132  131.63   131.4   131.5   131.4  131.45  131.48   131.5
  131.45   131.4   131.4  131.43  131.68  131.78   131.8  131.92  132.18  132.95
  133.12  133.13  133.14  133.02  132.96  135.86  135.94  135.95  133.05  132.97
  133.11  133.17  133.18  133.17  133.13  133.12   133.1  133.26   133.4  133.52
  133.64   134.3   136.3  137.19   137.6   140.3   140.3   140.6
   139.8   140.1   137.8   136.4  136.32   136.3   136.1   134.1   134.6     134
     132  131.77   131.3   130.1  129.92   129.8   129.6   129.1   127.7   128.6
     127   127.2   126.9     127   125.8   125.1   124.5     124     124   126.1
  125.88   125.6  124.63   124.2  130.66  130.66  130.74  130.75  130.75   126.7
  126.96   128.2   127.7   128.3   129.1   128.5  129.62   130.2   131.3   131.8
   132.9  133.98  135.12   136.5  137.27  139.46  140.27   140.6
  2902.5  2931.6  3061.6  3091.6  3141.6  3191.6  3241.6  3311.6  3331.6  3371.6
  3512.5  3791.6  3941.6  4032.5  4092.5  4191.6  4251.6  4291.6  4311.6  4391.6
  4411.6  4421.6  4461.6  4621.6  4691.6  4702.5  4711.6  4731.6  4791.6  4804.7
  4821.6  4849.2  4861.6  4911.6  4911.6    4915 5062.19  5062.2  5101.6    5112
  5161.6  5221.6  5231.6  5291.6  5311.6    5338  5351.6  5362.9  5372.9  5382.9
    5438    5498  5572.9    5608    5708  5744.9  5759.8
  139.94  140.24  137.94  137.17  136.44  136.24  135.19  134.74  134.36  133.99
   132.7     132  131.63   131.4   131.5   131.4  131.45  131.48   131.5  131.45
   131.4   131.4  131.43  131.68  131.78   131.8  131.92  132.18  132.95  133.12
  133.13  133.14  133.02  132.96  135.86  135.94  135.95  133.05  132.97  133.11
  133.17  133.18  133.17  133.13  133.12   133.1  133.26   133.4  133.52  133.64
   134.3   136.3  137.19   137.6   140.3  140.41  140.74
  139.94  140.24  137.94  136.54  136.44  136.24  134.24  134.74  134.14  132.14
  131.91  131.44  130.24  130.06  129.94  129.74  129.24  127.84  128.74  127.14
  127.34  127.04  127.14  125.94  125.24  124.64  124.14  124.14  126.24  126.02
  125.74  124.77  124.34   130.8   130.8  130.88  130.89  130.89  126.84   127.1
  128.34  127.84  128.44  129.24  128.64  129.76  130.34  131.44  131.94  133.04
  134.12  135.26  136.64  137.41   139.6  140.41  140.74
Pier Skew, UpSta & Num, DnSta & Num=  ,4953.4, 2 ,4953.4, 2 , 0 , 0 , 0 ,,
     1.3     1.3
  117.11  131.76
     1.3     1.3
  117.25   131.9
Pier Skew, UpSta & Num, DnSta & Num=  ,5008.6, 2 ,5008.6, 2 , 0 , 0 , 0 ,,
     1.3     1.3
  111.71  131.77
     1.3     1.3
  111.85  131.91
Abutment Skew #Up #Dn= , 2 , 2
  4898.2  4924.5
  130.37  120.53
  4898.2  4924.5
  130.51  120.67
Abutment Skew #Up #Dn= , 2 , 2
  5039.5 5063.49
  120.24  130.21
  5039.5 5063.49
  120.38  130.35
BR Coef= 1 , 1 , 1 ,1.25, 0 ,,,.8,0,2,0,
WSPro=,,,, 1 ,,,, 0 ,,,, 0 ,,,,-1 ,-1 ,-1 , 0 , 0 , 0 , 0 , 0
BR U #Sta/Elev= 92
  2902.5   139.8  2931.6   140.1  3061.6   137.8  3091.6   136.4  3132.5  136.32
  3141.6   136.3  3142.5   136.3  3191.6   136.1  3241.6   134.1  3311.6   134.6
  3331.6     134  3371.6     132  3512.5  131.77  3791.6   131.3  3941.6   130.1
  4032.5  129.92  4092.5   129.8  4191.6   129.6  4192.5  129.59  4251.6   129.1
  4291.6   127.7  4311.6   128.6  4312.5  128.58  4372.5  127.38  4391.6     127
  4411.6   127.2  4412.5  127.17  4421.6   126.9  4442.5  126.95  4461.6     127
  4621.6   125.8  4691.6   125.1  4702.5   124.5  4711.6     124  4731.6     124
  4791.6   126.1  4804.7  125.88  4821.6   125.6  4849.2  124.63  4861.6   124.2
  4881.6   122.7 4898.31   123.2  4898.4   123.2  4898.5  123.21  4898.6  123.21
  4911.6   123.6    4915  123.53  4921.6   123.4  4924.4  120.63  4924.5  120.53
  4953.5  118.06  4965.8  119.12    4976  119.99  4989.9  113.34    4995  112.65
  5006.4  112.72  5008.7  112.71  5010.2  113.35  5013.7  115.54  5019.8  119.37
  5039.5  120.24  5039.6  120.24  5041.6   122.4  5062.2  123.88  5063.2  123.95
 5063.29  123.95  5063.4  123.96  5063.5  123.97  5101.6   126.7    5112  126.96
  5161.6   128.2  5164.7  128.17  5214.3  127.76  5221.6   127.7  5231.6   128.3
  5291.6   129.1  5311.6   128.5    5338  129.62  5351.6   130.2  5352.9   130.3
  5362.9   131.3  5372.9   131.8  5382.9   132.9  5412.9   133.5    5438  133.98
    5498  135.12  5522.9   135.6  5572.9   136.5    5608  137.27    5708  139.46
  5744.9  140.27  5759.8   140.6
BR U #Mann= 4
  2902.5     .14    4976     .07  5019.8     .14  5744.9      .2
BR U Banks=4976,5019.8
BR D #Sta/Elev= 92
  2902.5  139.94  2931.6  140.24  3061.6  137.94  3091.6  136.54  3132.5  136.46
  3141.6  136.44  3142.5  136.44  3191.6  136.24  3241.6  134.24  3311.6  134.74
  3331.6  134.14  3371.6  132.14  3512.5  131.91  3791.6  131.44  3941.6  130.24
  4032.5  130.06  4092.5  129.94  4191.6  129.74  4192.5  129.73  4251.6  129.24
  4291.6  127.84  4311.6  128.74  4312.5  128.72  4372.5  127.52  4391.6  127.14
  4411.6  127.34  4412.5  127.31  4421.6  127.04  4442.5  127.09  4461.6  127.14
  4621.6  125.94  4691.6  125.24  4702.5  124.64  4711.6  124.14  4731.6  124.14
  4791.6  126.24  4804.7  126.02  4821.6  125.74  4849.2  124.77  4861.6  124.34
  4881.6  122.84 4898.31  123.34  4898.4  123.34  4898.5  123.35  4898.6  123.35
  4911.6  123.74    4915  123.67  4921.6  123.54  4924.4  120.77  4924.5  120.67
  4953.5   118.2  4965.8  119.26    4976  120.13  4989.9  113.48    4995  112.79
  5006.4  112.86  5008.7  112.85  5010.2  113.49  5013.7  115.68  5019.8  119.51
  5039.5  120.38  5039.6  120.38  5041.6  122.54  5062.2  124.02  5063.2  124.09
 5063.29  124.09  5063.4   124.1  5063.5  124.11  5101.6  126.84    5112   127.1
  5161.6  128.34  5164.7  128.31  5214.3   127.9  5221.6  127.84  5231.6  128.44
  5291.6  129.24  5311.6  128.64    5338  129.76  5351.6  130.34  5352.9  130.44
  5362.9  131.44  5372.9  131.94  5382.9  133.04  5412.9  133.64    5438  134.12
    5498  135.26  5522.9  135.74  5572.9  136.64    5608  137.41    5708   139.6
  5744.9  140.41  5759.8  140.74
BR D #Mann= 4
  2902.5     .14    4976     .07  5019.8     .14  5744.9      .2
BR D Banks=4976,5019.8
BC Design=,, 0 ,, 0 ,,,,,,
BC HTab HWMax=140.63

Type RM Length L Ch R = 1 ,29662.1 ,276.3,406.2,388.9
BEGIN DESCRIPTION:
Downstream Section of Bridge/Culvert/Weir
END DESCRIPTION:
XS GIS Cut Line= 3
      3058806.15      13967106.5      3060573.87      13965431.1
      3060963.04      13965312.4
#Sta/Elev= 30
  2902.5  139.93  3091.6  136.53  3191.6  136.23  3241.6  134.23  3311.6  134.73
  3371.6  132.13  4191.6  129.73  4291.6  127.83  4311.6  128.73  4391.6  127.13
  4691.6  125.23  4711.6  124.13  4791.6  126.23  4881.6  122.83  4921.6  123.53
  4924.5  120.66  4953.5  118.19    4976  120.12  4989.9  113.47    4995  112.78
  5008.7  112.84  5019.8   119.5  5039.6  120.37  5041.6  122.53  5101.6  126.83
  5161.6  128.33  5311.6  128.63  5382.9  133.03  5744.9   140.4  5759.8  140.73
#Mann= 4 ,-1 , 0
  2902.5     .14       0    4976     .08       0  5019.8     .14       0
  5744.9      .2       0
#XS Ineff= 2 , 0
       0    4887   131.4    5072       0  133.05
Permanent Ineff=
       F       F
Bank Sta=4976,5019.8
XS Rating Curve= 0
Exp/Cntr=.5,.3

Type RM Length L Ch R = 1 ,29255.9 ,1031.81,1393.3,854.8
BEGIN DESCRIPTION:
Cross Section XS15.1
END DESCRIPTION:
XS GIS Cut Line= 3
      3058944.56      13967180.9      3060536.54      13965899.8
       3061002.9      13965690.4
#Sta/Elev= 30
  3175.4   141.1  3245.4   138.7  3305.4   138.1  3335.4   136.4  3575.4   132.3
  3605.4   132.7  3635.4   131.4  4305.4   127.9  4365.4   126.6  4445.4   126.9
  4585.4   125.1  4685.4   127.7  4745.4     128  4785.4   127.2  4845.4   123.3
  4935.5   124.8  4944.5  124.43  4969.4  122.44  4979.7   120.4  4984.6  117.21
  4989.2  112.56  5006.9  112.54  5012.8  119.07  5018.1  122.12  5044.2   121.7
  5055.5  125.09  5065.4   127.1  5085.4   129.2  5125.4   130.6    5730   141.9
#Mann= 5 ,-1 , 0
  3175.4     .14       0  4935.5     .12       0  4944.5     .08       0
  5055.5     .12       0    5730      .2       0
#XS Ineff= 2 , 0
       0    4300     131               0
Permanent Ineff=
       F       F
Bank Sta=4944.5,5055.5
XS Rating Curve= 0
Exp/Cntr=.3,.1

Type RM Length L Ch R = 1 ,27862.6 ,1600.73,1751.1,1530.02
BEGIN DESCRIPTION:
Cross Section 27862.6
Cross Section XS15
END DESCRIPTION:
XS GIS Cut Line= 4
      3059517.29      13967878.5      3060935.71      13966873.1
      3060846.12      13966703.8      3061088.16      13966154.1
#Sta/Elev= 30
  3172.6   140.9  3452.6   134.6  3732.6     130  4042.6     128  4072.6   128.9
  4172.6     128  4332.6   128.5  4392.6   126.7  4522.6   128.8  4572.6   127.9
  4682.6   128.1  4872.6   121.9  4911.2   124.4  4946.5   122.9  4971.4  120.91
  4981.7  118.87  4986.6  115.68  4991.2   110.8  5008.9  111.01  5014.8  117.54
  5020.1  120.59  5046.2  120.17  5057.5  123.56  5097.4  123.88  5152.7  124.84
  5242.7   130.7  5322.7   137.3  5382.7   139.9  5602.7   139.5  5703.4   140.4
#Mann= 7 , 1 , 0
  3172.6      .2       0  3172.6     .15       0  4946.5     .08       0
  5057.5     .15       0  5097.4     .14       0  5152.7     .12       0
  5703.4      .2       0
Bank Sta=4946.5,5057.5
XS Rating Curve= 0
Exp/Cntr=.3,.1

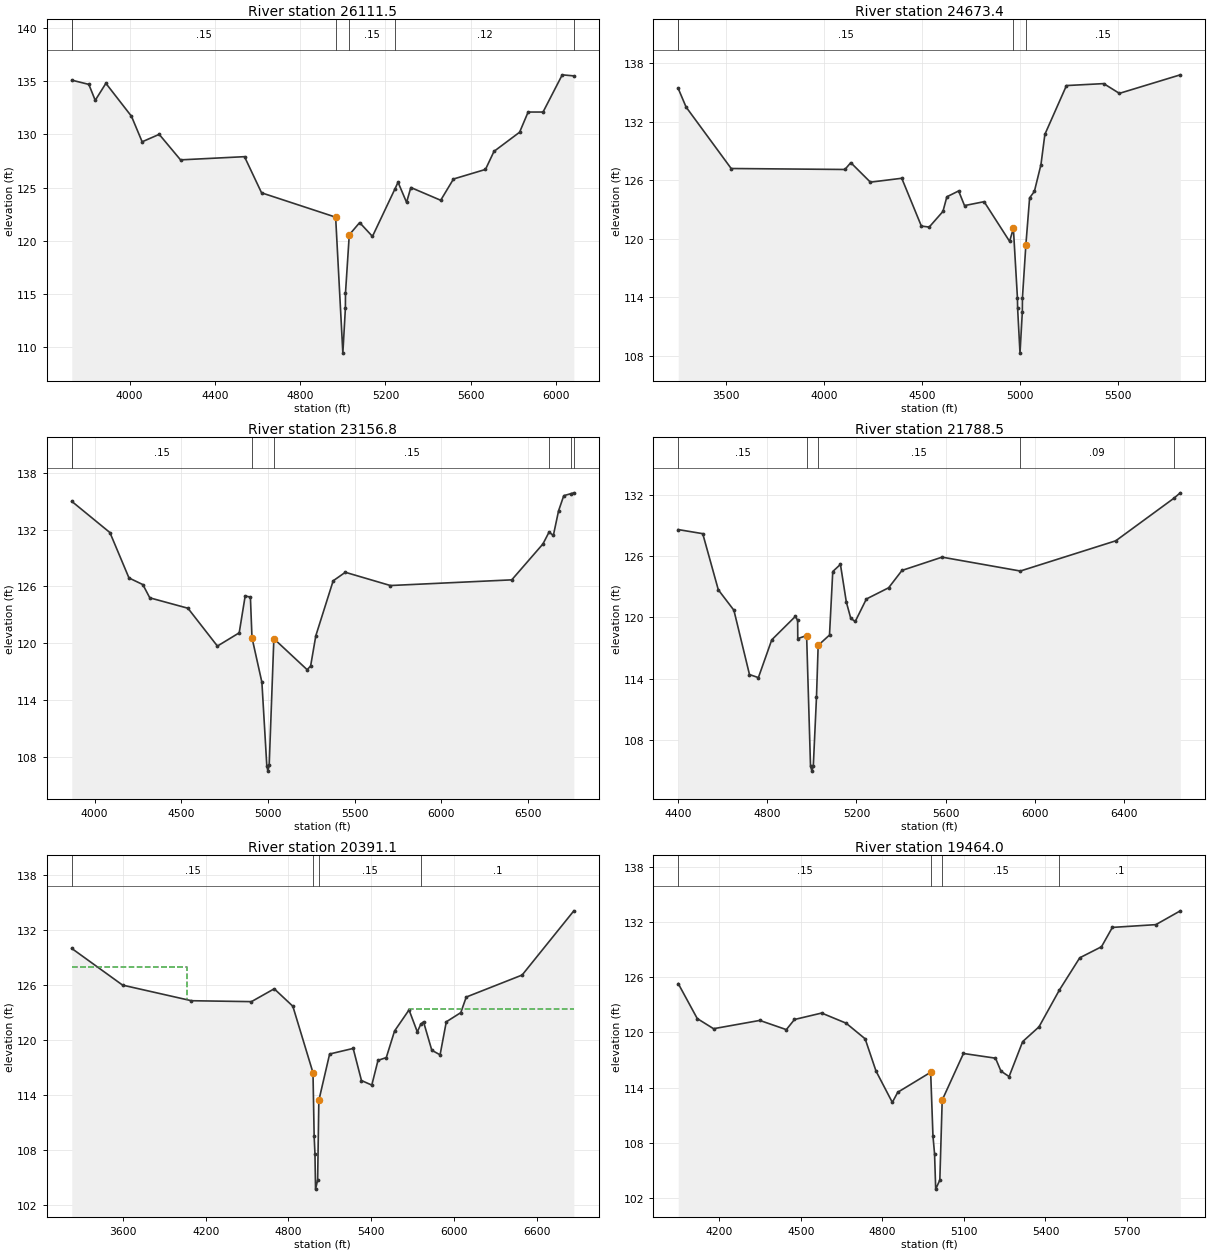
Type RM Length L Ch R = 1 ,26111.5 ,1000.9,1438.1,1111.83
BEGIN DESCRIPTION:
Cross Section 26111.5
Cross Section XS14.5
END DESCRIPTION:
XS GIS Cut Line= 2
      3061755.44      13969021.1      3062103.91      13966692.7
#Sta/Elev= 30
    3729   135.1    3809   134.7    3839   133.2    3889   134.8    4009   131.7
    4059   129.3    4139     130    4239   127.6    4539   127.9    4619   124.5
  4966.4  122.21  5000.2  109.42  5012.1  113.64  5012.6  115.08  5030.3  120.55
    5079   121.7    5139   120.4  5244.6  124.87    5259   125.5    5299   123.6
    5319     125    5459   123.8    5519   125.8    5669   126.7    5709   128.4
    5829   130.2    5869   132.1    5939   132.1    6029   135.6  6083.4   135.5
#Mann= 6 , 1 , 0
    3729      .2       0    3729     .15       0  4966.4     .08       0
  5030.3     .15       0  5244.6     .12       0  6083.4      .2       0
Bank Sta=4966.4,5030.3
XS Rating Curve= 0
Exp/Cntr=.3,.1

Type RM Length L Ch R = 1 ,24673.4 ,779.09,1516.6,1502.06
BEGIN DESCRIPTION:
Cross Section 24673.4
Cross Section XS14
Cross Section M100-00-00-X14
Located At: 10800FT US NORTHCREST
END DESCRIPTION:
XS GIS Cut Line= 4
      3062529.54      13969282.7      3062996.39      13967755.8
      3063092.62      13967543.4      3063244.37      13966828.6
#Sta/Elev= 30
  3257.2   135.4  3297.2   133.5  3527.2   127.2  4107.2   127.1  4137.2   127.8
  4237.2   125.8  4397.2   126.2  4497.2   121.3  4537.2   121.2  4607.2   122.8
  4627.2   124.3  4687.2   124.9  4717.2   123.4  4817.2   123.8  4947.2  119.73
  4966.4  121.07  4987.3  113.89    4988  112.89  5000.2  108.28  5012.1   112.5
  5012.6  113.94  5030.3  119.41  5049.2  124.19  5073.5  124.85  5107.1   127.6
  5127.1   130.7  5237.1   135.7  5427.1   135.9  5507.1   134.9  5817.8   136.8
#Mann= 4 , 1 , 0
  3257.2      .2       0  3257.2     .15       0  4966.4     .08       0
  5030.3     .15       0
Bank Sta=4966.4,5030.3
XS Rating Curve= 0
Exp/Cntr=.3,.1

Type RM Length L Ch R = 1 ,23156.8 ,1171.32,1368.3,856.58
BEGIN DESCRIPTION:
Cross Section 23156.8
Cross Section XS13
Cross Section M100-00-00-X13
Located At: 4TH US GOLF CART BRIDGE M100-00-00-05
END DESCRIPTION:
XS GIS Cut Line= 4
      3062729.58      13969393.3      3063507.41      13968820.9
      3063819.33      13968820.9       3065168.9      13967928.2
#Sta/Elev= 30
  3868.2     135  4088.2   131.7  4198.2   126.9  4278.2   126.2  4318.2   124.8
  4538.2   123.7  4708.2   119.7  4833.9   121.1  4868.3  124.99  4898.5  124.88
  4907.6  120.59  4964.8  115.87  4993.1  107.05  4999.4  106.48  5006.9  107.12
  5033.8  120.48  5225.9   117.2  5245.9   117.6  5275.9   120.8  5375.9   126.6
  5445.9   127.5  5705.9   126.1  6405.9   126.7  6585.9   130.5  6620.7  131.74
  6645.9   131.4  6675.9     134  6705.9   135.6  6746.9  135.81    6764   135.9
#Mann= 7 , 1 , 0
  3868.2      .2       0  3868.2     .15       0  4907.6     .08       0
  5033.8     .15       0  6620.7     .12       0  6746.9     .15       0
    6764      .2       0
Bank Sta=4907.6,5033.8
XS Rating Curve= 0
Exp/Cntr=.3,.1

Type RM Length L Ch R = 1 ,21788.5 ,1287.99,1397.4,836.68
BEGIN DESCRIPTION:
Cross Section 21788.5
Cross Section XS12
Cross Section M100-00-00-X12
Located At: 3RD US GOLF CART BRIDGE M100-00-00-05
END DESCRIPTION:
XS GIS Cut Line= 4
      3064115.09      13969985.1      3064376.91      13969551.7
      3064540.75      13969378.1      3065441.06      13968165.9
#Sta/Elev= 30
  4399.6   128.6  4509.6   128.2  4579.6   122.7  4649.6   120.7  4719.6   114.4
  4759.6   114.1  4819.6   117.8  4925.9   120.1  4935.9   119.7  4936.5  117.92
  4976.2  118.22  4993.7  105.45    5000  104.94  5006.3  105.46  5020.5  112.17
  5028.1  117.26    5079  118.27  5093.6  124.49  5128.1  125.19  5154.6   121.5
  5174.6   119.9  5194.6   119.6  5244.6   121.8  5344.6   122.9  5404.6   124.6
  5584.6   125.9    5936  124.54  6364.6   127.5  6624.6  131.65  6654.6   132.2
#Mann= 5 ,-1 , 0
  4399.6     .15       0  4976.2     .08       0  5028.1     .15       0
    5936     .09       0  6624.6     .15       0
Bank Sta=4976.2,5028.1
XS Rating Curve= 0
Exp/Cntr=.3,.1

Type RM Length L Ch R = 1 ,20391.1 ,914.2,927.1,574.35
BEGIN DESCRIPTION:
Cross Section Xs11.5
Ineffective Flow at Left edge of Cross Section inserted due to flow overflowing into M104.
END DESCRIPTION:
XS GIS Cut Line= 6
      3064815.35      13971314.9      3065566.29      13970943.8
      3065501.14      13970056.6      3065492.83      13969969.3
      3065371.53      13968946.7      3065657.48      13968204.9
#Sta/Elev= 30
    3229     130  3597.6     126  4096.6   124.3  4531.6   124.2  4696.6   125.6
  4831.6   123.7  4977.7  116.45  4986.1  109.55    4992  107.59  4996.2  103.76
  5011.4  104.75  5020.1  113.43  5098.3  118.49    5269   119.1    5329   115.6
    5404   115.1    5449   117.8    5509   118.1    5569     121    5674   123.3
    5734   120.9  5759.1  121.74    5779     122    5839   118.9    5899   118.4
    5944     122    6049     123  6088.7   124.7  6493.7   127.1  6868.7   134.1
#Mann= 4 ,-1 , 0
    3229     .15       0  4977.7     .08       0  5020.1     .15       0
  5759.1      .1       0
#XS Ineff= 2 , 0
       0  4066.6     128    5675       0   123.4
Permanent Ineff=
       F       F
Bank Sta=4977.7,5020.1
XS Rating Curve= 0
Exp/Cntr=.3,.1

Type RM Length L Ch R = 1 ,19464.0 ,1343.61,1690.4,1596.7
BEGIN DESCRIPTION:
Cross Section 19464.0
Cross Section XS11
Cross Section M100-00-00-X11
Located At: 2ND US GOLF CART BRIDGE M100-00-00-05
Ineffective Flow at Left edge of Cross Section inserted due to flow overflowing into M104.
END DESCRIPTION:
XS GIS Cut Line= 4
      3066228.64      13970161.5      3066302.62      13969841.4
      3065929.21      13969155.7    3065954.2072   13968412.1806
#Sta/Elev= 30
  4048.9   125.3  4118.9   121.5  4178.9   120.4  4348.9   121.3  4446.6   120.3
  4476.6   121.4  4576.6   122.1  4666.6     121  4736.6   119.3  4776.6   115.8
  4836.6   112.4  4856.6   113.5  4977.7  115.67  4986.1  108.77    4992  106.81
  4996.2  102.98  5011.4  103.97  5020.1  112.65  5098.3  117.71  5216.2   117.2
  5236.2   115.8  5266.2   115.2  5316.2     119  5376.2   120.6  5450.9  124.58
  5526.2   128.1  5606.2   129.3  5646.2   131.4  5806.2   131.7  5896.2   133.2
#Mann= 4 ,-1 , 0
  4048.9     .15       0  4977.7     .08       0  5020.1     .15       0
  5450.9      .1       0
Bank Sta=4977.7,5020.1
XS Rating Curve= 0
Exp/Cntr=.3,.1