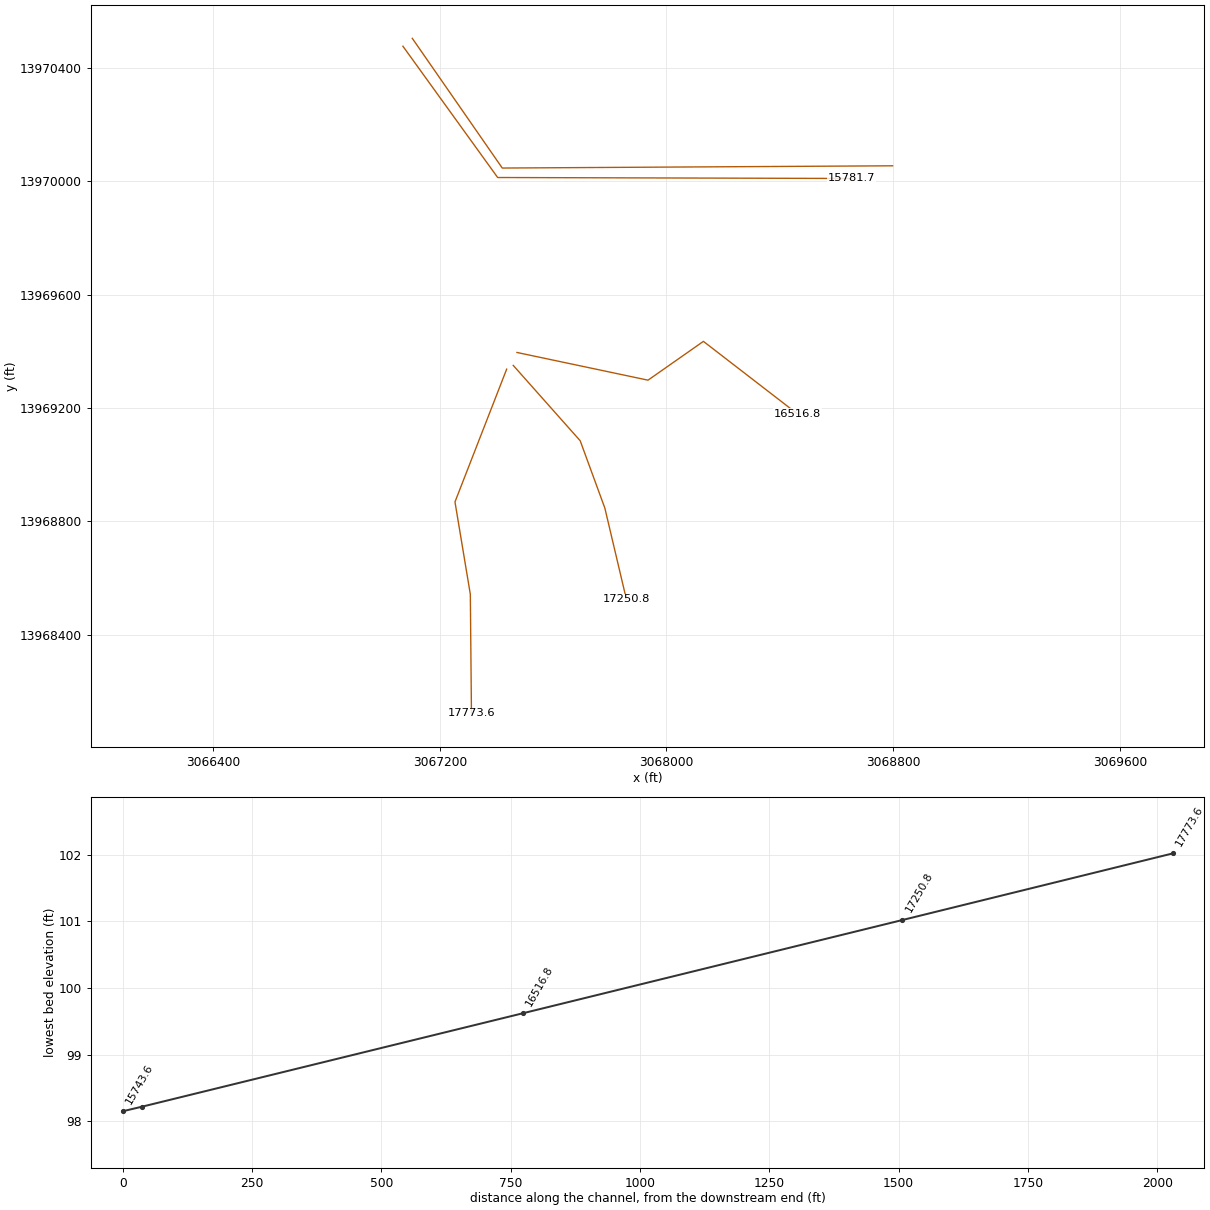
HEC-RAS study M100-00-00.prj: M100-00-00

--- M100-00-00.g01 (geometry) --- (continued)

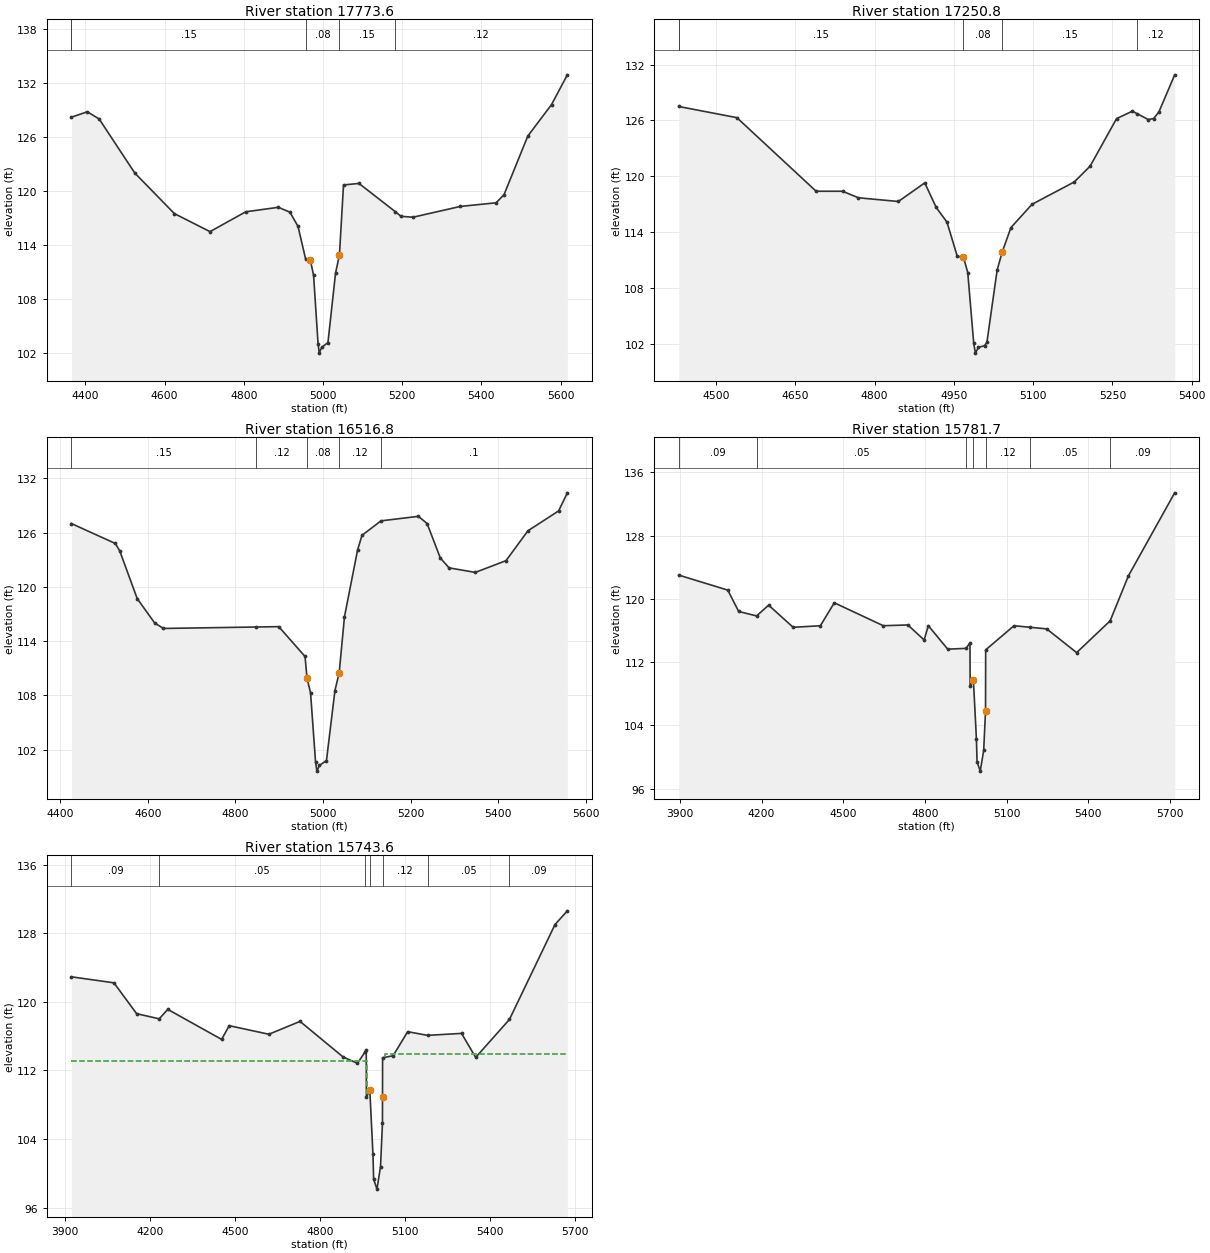
Type RM Length L Ch R = 1 ,17773.6 ,451.19,522.8,541.21
BEGIN DESCRIPTION:
Cross Section 17773.6
Cross Section XS10
Cross Section M100-00-00-X10
Located At: US GOLF CART BRIDGE M100-00-00-05
END DESCRIPTION:
XS GIS Cut Line= 4
      3067435.83       13969337.      3067253.36      13968868.8
      3067307.56      13968543.3      3067311.52      13968123.3
#Sta/Elev= 30
  4364.7   128.2  4404.7   128.8  4434.7     128  4524.7     122  4624.7   117.5
  4714.7   115.5  4804.7   117.7  4887.2   118.2  4916.5  117.66  4936.9  116.08
  4956.4  112.41  4968.1  112.32  4976.2  110.67  4987.5  103.08  4990.7  102.02
  4996.4  102.65  5012.5  103.19  5031.8  110.93  5041.5  112.89  5051.8  120.68
  5090.8  120.85  5182.4  117.72  5197.2   117.2  5227.2   117.1  5347.2   118.3
  5437.2   118.7  5457.2   119.6  5517.2   126.1  5577.2   129.6  5617.2   132.9
#Mann= 5 , 1 , 0
  4364.7      .2       0  4364.7     .15       0  4956.4     .08       0
  5041.5     .15       0  5182.4     .12       0
Bank Sta=4968.1,5041.5
XS Rating Curve= 0
Exp/Cntr=.3,.1

Type RM Length L Ch R = 1 ,17250.8 ,252.5,734,887.04
BEGIN DESCRIPTION:
Cross Section 17250.8
Cross Section XS09.3
END DESCRIPTION:
XS GIS Cut Line= 4
        3067459.      13969350.2      3067695.34      13969084.5
      3067782.46      13968846.9      3067858.36      13968525.7
#Sta/Elev= 30
  4429.2   127.5  4539.2   126.3  4689.2   118.4  4739.2   118.4  4769.2   117.7
  4844.8   117.3  4894.8   119.3  4916.5  116.66  4936.9  115.08  4956.4  111.41
  4968.1  111.32  4976.2  109.67  4987.5  102.08  4990.7  101.02  4996.4  101.65
  5007.9  101.81  5012.5  102.19  5031.8  109.93  5041.5  111.89  5057.9   114.5
  5097.9     117  5177.9   119.4  5207.9   121.1  5257.9   126.2  5287.9     127
  5296.4  126.74  5317.9   126.1  5327.9   126.2  5337.9   126.9  5367.9   130.9
#Mann= 5 , 1 , 0
  4429.2      .2       0  4429.2     .15       0  4968.1     .08       0
  5041.5     .15       0  5296.4     .12       0
Bank Sta=4968.1,5041.5
XS Rating Curve= 0
Exp/Cntr=.3,.1

Type RM Length L Ch R = 1 ,16516.8 ,675.66,735.1,608.33
BEGIN DESCRIPTION:
Cross Section 16516.8
Cross Section XS09.2
END DESCRIPTION:
XS GIS Cut Line= 4
      3067472.04      13969395.8      3067934.79      13969298.1
      3068130.32      13969434.9      3068462.18      13969179.2
#Sta/Elev= 30
  4425.8     127  4525.8   124.8  4535.8     124  4575.8   118.7  4615.8     116
  4635.8   115.4  4847.8  115.56  4898.8   115.6  4958.8   112.3  4963.3  109.91
  4971.4  108.27  4982.7  100.68  4985.9   99.62  4991.6  100.25  5007.7  100.79
    5027  108.53  5036.7  110.49  5048.8   116.7  5078.8   124.1  5088.8   125.7
  5132.1   127.3  5217.4   127.8  5237.4     127  5267.4   123.2  5287.4   122.1
  5347.4   121.6  5417.4   122.9  5467.4   126.2  5537.4   128.4  5557.4   130.4
#Mann= 5 ,-1 , 0
  4425.8     .15       0  4847.8     .12       0  4963.3     .08       0
  5036.7     .12       0  5132.1      .1       0
Bank Sta=4963.3,5036.7
XS Rating Curve= 0
Exp/Cntr=.3,.1

Type RM Length L Ch R = 1 ,15781.7 ,36.6,38.1,39.6
BEGIN DESCRIPTION:
Cross Section 15781.7
Cross Section XS09.15
END DESCRIPTION:
XS GIS Cut Line= 3
      3067069.59      13970475.5      3067404.03      13970012.6
      3068654.03      13970009.2
#Sta/Elev= 30
  3895.8     123  4075.8   121.1  4115.8   118.4  4181.5  117.84  4225.8   119.2
  4315.8   116.4  4415.8   116.6  4466.9   119.5  4646.9   116.6  4736.9   116.7
  4796.9   114.8  4812.1  116.61  4883.4  113.64    4951  113.74  4965.1  114.44
  4965.8  108.94  4977.7  109.76  4988.8  102.29  4991.2   99.38  5002.9   98.22
  5015.5  100.84  5022.3  105.88  5022.8  113.55  5126.9   116.6    5184  116.41
  5246.9   116.2  5356.9   113.2  5479.9  117.22  5546.9   122.9  5716.9   133.4
#Mann= 7 ,-1 , 0
  3895.8     .09       0  4181.5     .05       0    4951     .12       0
  4977.7     .08       0  5022.3     .12       0    5184     .05       0
  5479.9     .09       0
Bank Sta=4977.7,5022.3
XS Rating Curve= 0
Exp/Cntr=.5,.3

Type RM Length L Ch R = 1 ,15743.6 ,29.2,29.2,29.2
BEGIN DESCRIPTION:
Upstream Section of Bridge/Culvert/Weir
END DESCRIPTION:
XS GIS Cut Line= 3
      3067102.66      13970503.3      3067420.27       13970046.
      3068798.32      13970053.9
#Sta/Elev= 30
    3922  122.92    4072  122.22    4152  118.62  4231.6  118.02    4262  119.12
    4452  115.62  4478.8  117.22  4618.8  116.22  4728.8  117.72  4880.8  113.57
  4931.6  112.83  4957.9  114.14  4962.5  114.37  4963.1  108.87  4975.1  109.69
  4986.2  102.22  4988.6   99.31  5000.3   98.15  5012.9  100.77  5019.7  105.81
  5019.9  108.88  5020.2  113.48  5057.2  113.71  5108.8  116.52  5178.9  116.09
  5298.8  116.32  5348.8  113.52    5468  117.95  5628.8  129.02  5672.4  130.62
#Mann= 7 ,-1 , 0
    3922     .09       0  4231.6     .05       0  4957.9     .12       0
  4975.1     .08       0  5019.9     .12       0  5178.9     .05       0
    5468     .09       0
#XS Ineff= 2 , 0
       0  4965.1  113.11  5027.8       0  113.93
Permanent Ineff=
       F       F
Bank Sta=4975.1,5019.9
XS Rating Curve= 0
Exp/Cntr=.5,.3