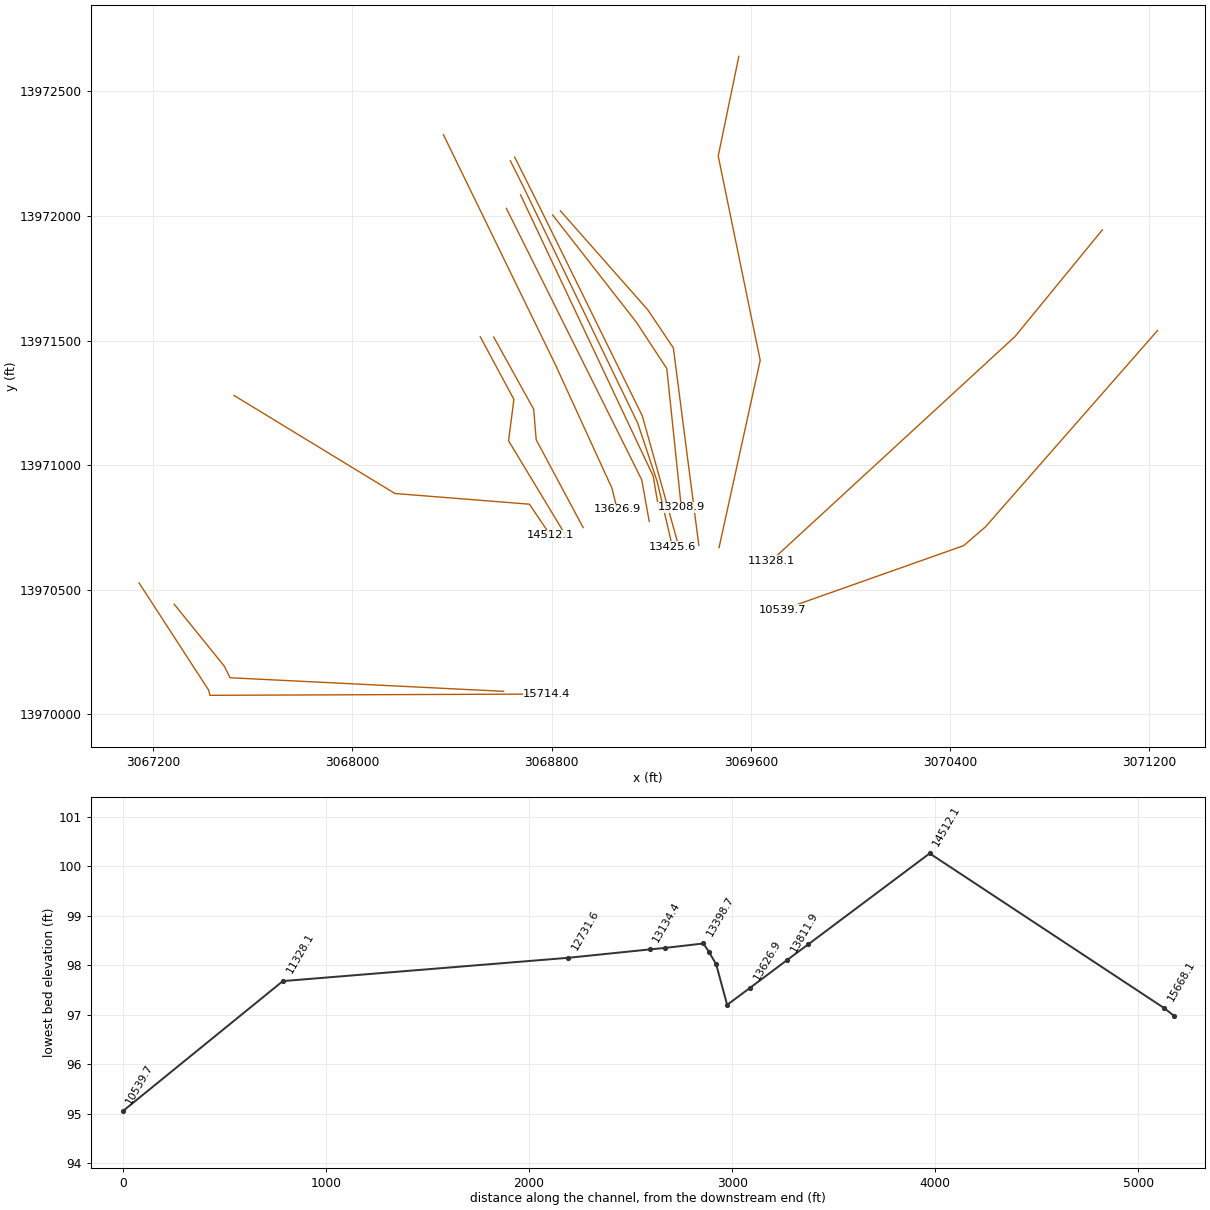
HEC-RAS study M100-00-00.prj: M100-00-00

--- M100-00-00.g01 (geometry) --- (continued)

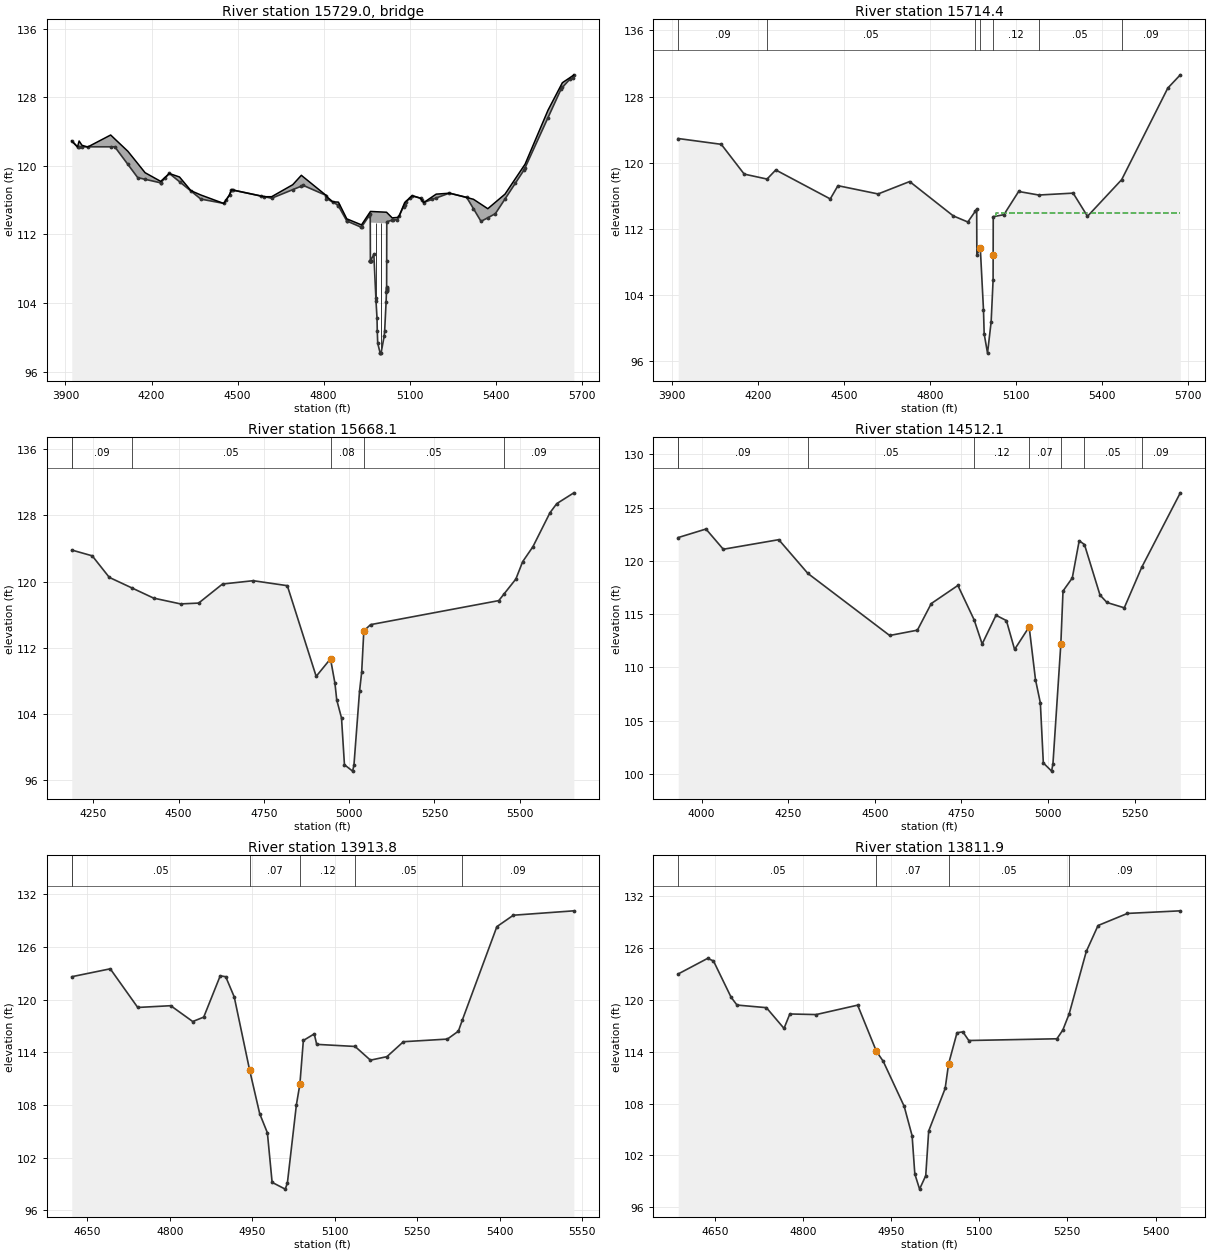
Type RM Length L Ch R = 3 ,15729.0 ,,,
BEGIN DESCRIPTION:
GOLF CART BRIDGE DS KUYKENDAHL
Structure ID: M100-00-00-05
END DESCRIPTION:
Node Name=Golf Cart Br.
Bridge Culvert--1,0,-1,-1, 0
Deck Dist Width WeirC Skew NumUp NumDn MinLoCord MaxHiCord MaxSubmerge Is_Ogee
10,9.2,2.6,0, 60, 60, , , .95, 0, 1,1,,
    3922    3942  3947.6  3957.6  3977.6  4057.6    4072  4117.6    4152  4177.6
    4232    4262  4297.6  4337.6    4372    4452    4472  4478.8  4592.4  4618.8
  4692.4  4722.4  4728.8  4809.5    4810  4832.4  4851.7  4880.8  4932.1  4962.5
  4963.1 4963.43  4963.5 5019.29  5019.4  5019.7  5020.2  5039.1  5057.2  5062.9
  5082.4  5088.8  5108.8  5138.8  5148.8  5192.4  5238.8  5298.8  5322.4  5348.8
  5372.4  5398.8  5432.4  5502.4  5582.4  5628.8  5632.4  5658.8  5668.8  5672.4
   122.9   122.2   122.9   122.4   122.2   123.6  123.14   121.7  120.27   119.2
  118.19  119.11   118.7   117.1   116.6  115.61  116.61  117.21   116.4   116.4
   117.8   118.9  118.72  116.53  116.43   115.8  115.77  113.82  113.11  114.64
  114.67  114.68  114.68  114.59  114.59  114.58  114.56  113.93  113.98  114.11
   115.7  115.92  116.51  116.21  115.71   116.7  116.81  116.31   116.1  115.52
     115  115.75   116.7   120.2   126.5  129.47   129.7  130.29  130.52   130.6
   122.9   122.2   122.2   122.2   122.2   122.2   122.2  120.15   118.6  118.41
     118   119.1  118.13  117.04   116.1   115.6   116.6   117.2  116.39   116.2
   117.2  117.61   117.7  116.52  116.17  115.74   115.3  113.55  112.83  114.35
  108.85  108.87  113.38  113.29  105.52  105.79  113.46  113.64  113.69   114.1
  115.44   115.8   116.5   116.2   115.7  116.23   116.8   116.3  114.98   113.5
  113.92   114.4  116.11  119.76  125.61     129  129.13   130.1   130.2   130.6
    3922    3942  3947.6  3957.6  3977.6  4057.6    4072  4117.6    4152  4177.6
    4232    4262  4297.6  4337.6    4372    4452    4472  4478.8  4592.4  4618.8
  4692.4  4722.4  4728.8  4809.5    4810  4832.4  4851.7  4880.8  4932.1  4962.5
  4963.1 4963.43  4963.5 5019.29  5019.4  5019.7  5020.2  5039.1  5057.2  5062.9
  5082.4  5088.8  5108.8  5138.8  5148.8  5192.4  5238.8  5298.8  5322.4  5348.8
  5372.4  5398.8  5432.4  5502.4  5582.4  5628.8  5632.4  5658.8  5668.8  5672.4
   122.9   122.2   122.9   122.4   122.2   123.6  123.14   121.7  120.27   119.2
  118.19  119.11   118.7   117.1   116.6  115.61  116.61  117.21   116.4   116.4
   117.8   118.9  118.72  116.53  116.43   115.8  115.77  113.82  113.11  114.64
  114.67  114.68  114.68  114.59  114.59  114.58  114.56  113.93  113.98  114.11
   115.7  115.92  116.51  116.21  115.71   116.7  116.81  116.31   116.1  115.52
     115  115.75   116.7   120.2   126.5  129.47   129.7  130.29  130.52   130.6
   122.9   122.2   122.2   122.2   122.2   122.2   122.2  120.15   118.6  118.41
     118   119.1  118.13  117.04   116.1   115.6   116.6   117.2  116.39   116.2
   117.2  117.61   117.7  116.52  116.17  115.74   115.3  113.55  112.83  114.35
  108.85  108.87  113.38  113.29  105.52  105.79  113.46  113.64  113.69   114.1
  115.44   115.8   116.5   116.2   115.7  116.23   116.8   116.3  114.98   113.5
  113.92   114.4  116.11  119.76  125.61     129  129.13   130.1   130.2   130.6
Pier Skew, UpSta & Num, DnSta & Num=  ,4982.6, 2 ,4982.6, 2 , 0 , 0 , 0 ,,
       1       1
  102.97  114.35
       1       1
  101.82  114.35
Pier Skew, UpSta & Num, DnSta & Num=  ,5000.3, 2 ,5000.3, 2 , 0 , 0 , 0 ,,
       1       1
   97.14  114.32
       1       1
   95.99  114.32
BR Coef= 1 , 1 , 1 ,1.25, 0 ,,,.8,0,2,0,
WSPro=,,,, 1 ,,,, 0 ,,,, 0 ,,,,-1 ,-1 ,-1 , 0 , 0 , 0 , 0 , 0
BR U #Sta/Elev= 97
    3922  122.92    3942  122.22  3947.6  122.22  3957.6  122.22  3977.6  122.22
  4057.6  122.22    4072  122.22  4117.6  120.17    4152  118.62  4177.6  118.43
  4231.6  118.02    4232  118.02  4247.6  118.59    4262  119.12  4297.6  118.15
  4337.6  117.06    4372  116.12    4452  115.62  4460.8  116.06    4472  116.62
  4478.8  117.22  4480.8  117.21  4482.4  117.19  4582.4  116.48  4592.4  116.41
  4618.8  116.22  4692.4  117.22  4722.4  117.63  4728.8  117.72  4809.5  116.54
    4810  116.19  4832.4  115.76    4850  115.42  4851.7  115.32  4880.5  113.59
  4880.8  113.57  4931.6  112.83  4932.1  112.85  4957.9  114.14  4962.5  114.37
  4963.1  108.87  4963.2  108.88 4963.31  108.88 4963.43  108.89  4963.5   108.9
  4963.6   108.9  4963.7  108.91  4975.1  109.69  4982.2   104.6  4982.6  104.28
  4986.2  102.22  4987.1  100.77  4988.6   99.31  4996.7   98.22  4997.1   98.21
  5000.3   98.15  5011.1  100.13  5012.9  100.77  5017.8  104.09 5019.17  105.33
 5019.29  105.44  5019.4  105.54  5019.5  105.63  5019.6  105.72  5019.7  105.81
  5019.9  108.88  5020.2  113.48  5039.1  113.66  5041.1  113.68  5057.2  113.71
  5062.9  114.12  5078.7  115.25  5082.4  115.46  5088.8  115.82  5102.4   116.3
  5108.8  116.52  5138.8  116.22  5142.4  116.04  5148.8  115.72  5178.9  116.09
  5192.4  116.25  5238.8  116.82  5298.8  116.32  5322.4     115  5348.8  113.52
  5372.4  113.94  5398.8  114.42  5432.4  116.13    5468  117.95  5498.8  119.52
  5502.4  119.78  5582.4  125.63  5628.8  129.02  5632.4  129.15  5658.8  130.12
  5668.8  130.22  5672.4  130.62
BR U #Mann= 7
    3922     .09  4231.6     .05  4957.9     .12  4975.1     .07  5019.9     .12
  5178.9     .05    5468     .09
BR D #Sta/Elev= 97
    3922  122.92    3942  122.22  3947.6  122.22  3957.6  122.22  3977.6  122.22
  4057.6  122.22    4072  122.22  4117.6  120.17    4152  118.62  4177.6  118.43
  4231.6  118.02    4232  118.02  4247.6  118.59    4262  119.12  4297.6  118.15
  4337.6  117.06    4372  116.12    4452  115.62  4460.8  116.06    4472  116.62
  4478.8  117.22  4480.8  117.21  4482.4  117.19  4582.4  116.48  4592.4  116.41
  4618.8  116.22  4692.4  117.22  4722.4  117.63  4728.8  117.72  4809.5  116.54
    4810  116.19  4832.4  115.76    4850  115.42  4851.7  115.32  4880.5  113.59
  4880.8  113.57  4931.6  112.83  4932.1  112.85  4957.9  114.14  4962.5  114.37
  4963.1  108.87  4963.2  108.88 4963.31  108.88 4963.43  108.89  4963.5   108.9
  4963.6   108.9  4963.7  108.91  4975.1  109.69  4982.2   104.6  4982.6  104.28
  4986.2  102.22  4987.1  100.77  4988.6   99.31  4996.7   98.22  4997.1   98.21
  5000.3   96.98  5011.1  100.13  5012.9  100.77  5017.8  104.09 5019.17  105.33
 5019.29  105.44  5019.4  105.54  5019.5  105.63  5019.6  105.72  5019.7  105.81
  5019.9  108.88  5020.2  113.48  5039.1  113.66  5041.1  113.68  5057.2  113.71
  5062.9  114.12  5078.7  115.25  5082.4  115.46  5088.8  115.82  5102.4   116.3
  5108.8  116.52  5138.8  116.22  5142.4  116.04  5148.8  115.72  5178.9  116.09
  5192.4  116.25  5238.8  116.82  5298.8  116.32  5322.4     115  5348.8  113.52
  5372.4  113.94  5398.8  114.42  5432.4  116.13    5468  117.95  5498.8  119.52
  5502.4  119.78  5582.4  125.63  5628.8  129.02  5632.4  129.15  5658.8  130.12
  5668.8  130.22  5672.4  130.62
BR D #Mann= 7
    3922     .09  4231.6     .05  4957.9     .12  4975.1     .07  5019.9     .12
  5178.9     .05    5468     .09
BC Design=,, 0 ,, 0 ,,,,,,
BC HTab HWMax=130.62

Type RM Length L Ch R = 1 ,15714.4 ,46.3,46.3,46.3
BEGIN DESCRIPTION:
Downstream Section of Bridge/Culvert/Weir
END DESCRIPTION:
XS GIS Cut Line= 5
      3067142.94      13970526.6      3067422.34      13970096.2
      3067427.58      13970075.2        3068786.      13970080.4
      3068780.76      13970080.4
#Sta/Elev= 30
    3922  122.92    4072  122.22    4152  118.62  4231.6  118.02    4262  119.12
    4452  115.62  4478.8  117.22  4618.8  116.22  4728.8  117.72  4880.8  113.57
  4931.6  112.83  4957.9  114.14  4962.5  114.37  4963.1  108.87  4975.1  109.69
  4986.2  102.22  4988.6   99.31  5000.3   96.98  5012.9  100.77  5019.7  105.81
  5019.9  108.88  5020.2  113.48  5057.2  113.71  5108.8  116.52  5178.9  116.09
  5298.8  116.32  5348.8  113.52    5468  117.95  5628.8  129.02  5672.4  130.62
#Mann= 7 ,-1 , 0
    3922     .09       0  4231.6     .05       0  4957.9     .12       0
  4975.1     .08       0  5019.9     .12       0  5178.9     .05       0
    5468     .09       0
#XS Ineff= 2 , 0
       0    4952  113.11    5030       0  113.93
Permanent Ineff=
       F       F
Bank Sta=4975.1,5019.9
XS Rating Curve= 0
Exp/Cntr=.5,.3

Type RM Length L Ch R = 1 ,15668.1 ,884.61,1156,874.71
BEGIN DESCRIPTION:
Cross Section 15668.1
Cross Section XS09.1
END DESCRIPTION:
XS GIS Cut Line= 4
      3067284.01      13970441.1      3067484.69      13970193.1
      3067508.34      13970145.8      3068606.99      13970091.2
#Sta/Elev= 30
  4186.7   123.8  4246.7   123.1  4296.7   120.5  4363.4  119.22  4426.7     118
  4505.7   117.3  4558.6   117.4  4628.6   119.7  4718.6   120.1  4818.6   119.5
  4903.2  108.56  4945.2  110.68  4958.2  107.74  4963.5  105.72  4977.5  103.54
  4986.1    97.9    5010   97.13  5013.9   97.84  5030.3  106.75  5036.6  109.07
  5042.9  114.05  5062.7   114.8  5438.6   117.7  5454.1  118.51  5488.6   120.3
  5508.6   122.4  5538.6   124.2  5588.6   128.3  5608.6   129.4  5658.6   130.7
#Mann= 6 , 1 , 0
  4186.7      .2       0  4186.7     .09       0  4363.4     .05       0
  4945.2     .08       0  5042.9     .05       0  5454.1     .09       0
Bank Sta=4945.2,5042.9
XS Rating Curve= 0
Exp/Cntr=.3,.1

Type RM Length L Ch R = 1 ,14512.1 ,692.66,598.3,155.47
BEGIN DESCRIPTION:
Cross Section 14512.1
Cross Section XS09
END DESCRIPTION:
XS GIS Cut Line= 4
      3067524.18      13971279.4      3068170.49      13970885.6
      3068710.48      13970842.7      3068794.29      13970718.3
#Sta/Elev= 30
  3932.8   122.2  4012.8     123  4062.8   121.1  4222.8     122  4306.8  118.83
  4542.8     113  4622.8   113.5  4662.8     116  4739.6   117.7  4786.5  114.47
  4809.6   112.2  4849.6   114.9  4879.6   114.4  4903.2  111.69  4945.2  113.81
  4963.5  108.85  4977.5  106.67  4986.1  101.03    5010  100.26  5013.9  100.97
  5036.6   112.2  5042.9  117.18  5069.6   118.4  5089.6   121.9  5104.8  121.54
  5149.6   116.8  5169.6   116.1  5219.6   115.6  5270.2  119.42  5381.3   126.4
#Mann= 8 , 1 , 0
  3932.8      .2       0  3932.8     .09       0  4306.8     .05       0
  4786.5     .12       0  4945.2     .07       0  5036.6     .12       0
  5104.8     .05       0  5270.2     .09       0
Bank Sta=4945.2,5036.6
XS Rating Curve= 0
Exp/Cntr=.3,.1

Type RM Length L Ch R = 1 ,13913.8 ,49.21,101.9,90.4
BEGIN DESCRIPTION:
Cross Section 13913.8
Cross Section XS8.8
END DESCRIPTION:
XS GIS Cut Line= 4
      3068513.08      13971515.1       3068648.1      13971263.6
      3068626.78      13971097.3      3068864.59      13970703.5
#Sta/Elev= 30
  4621.7   122.6  4691.7   123.5  4741.7   119.1  4801.7   119.3  4841.7   117.5
  4861.7     118  4891.7   122.7  4901.7   122.6  4917.2   120.3  4945.2  111.97
  4963.5  107.01  4977.5  104.83  4986.1   99.19    5010   98.42  5013.9   99.13
  5030.3  108.04  5036.6  110.36  5042.9  115.34  5062.7  116.09  5067.2   114.9
    5137  114.66  5164.9   113.1  5194.9   113.5  5224.9   115.2  5304.9   115.5
  5324.9   116.4  5332.2  117.69  5394.9   128.3  5424.9   129.6  5534.9   130.1
#Mann= 6 , 1 , 0
  4621.7      .2       0  4621.7     .05       0  4945.2     .07       0
  5036.6     .12       0    5137     .05       0  5332.2     .09       0
Bank Sta=4945.2,5036.6
XS Rating Curve= 0
Exp/Cntr=.3,.1

Type RM Length L Ch R = 1 ,13811.9 ,173.43,185,189.41
BEGIN DESCRIPTION:
Cross Section 13811.9
Cross Section XS8.7
END DESCRIPTION:
XS GIS Cut Line= 4
      3068566.99       13971514.       3068727.7      13971223.8
      3068737.65      13971101.5      3068926.22      13970748.8
#Sta/Elev= 30
  4587.8     123  4637.8   124.8  4647.8   124.5  4677.8   120.3  4687.8   119.4
  4737.8   119.1  4767.8   116.7  4777.7  118.37  4822.4   118.3  4893.1  119.39
  4925.1  114.04  4936.7  112.89  4972.3  107.69  4985.8  104.28  4990.4   99.87
  4998.5   98.11    5009   99.67    5014  104.83    5042  109.75  5047.9  112.61
  5062.2   116.2  5072.2   116.3  5082.2   115.3  5232.2   115.5  5242.2   116.5
  5253.1  118.39  5282.2   125.6  5302.2   128.6  5352.2     130  5442.2   130.3
#Mann= 4 ,-1 , 0
  4587.8     .05       0  4925.1     .07       0  5047.9     .05       0
  5253.1     .09       0
Bank Sta=4925.1,5047.9
XS Rating Curve= 0
Exp/Cntr=.3,.1

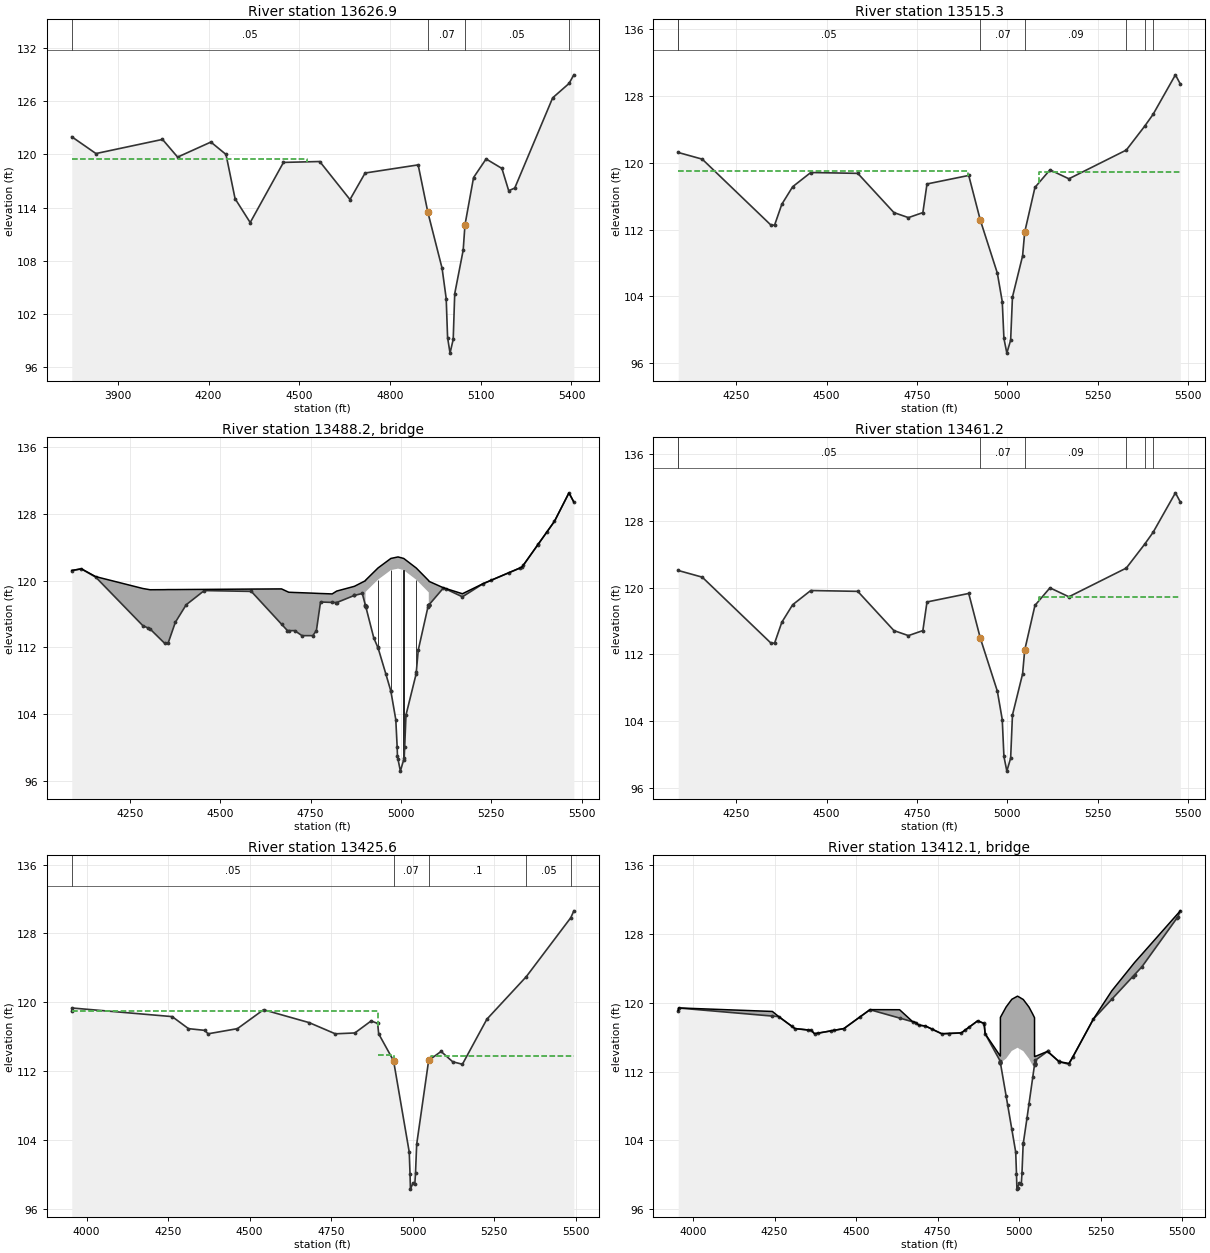
Type RM Length L Ch R = 1 ,13626.9 ,113.13,111.65,111.34
BEGIN DESCRIPTION:
Cross Section 13626.9
Cross Section XS8.5
END DESCRIPTION:
XS GIS Cut Line= 4
       3068365.3       13972326.      3068814.66      13971403.2
      3069041.74      13970907.4      3069062.88      13970821.5
#Sta/Elev= 30
  3747.7     122  3827.7   120.1  4047.7   121.7  4097.7   119.7  4207.7   121.4
  4257.7     120  4287.7     115  4337.7   112.3  4447.7   119.1  4567.7   119.2
  4667.7   114.9  4717.7   117.9  4893.1  118.82  4925.1  113.47  4972.3  107.12
  4985.8  103.71  4990.4    99.3  4998.5   97.54    5009    99.1    5014  104.26
    5042  109.18  5047.9  112.04  5076.3  117.39  5117.7  119.49    5170  118.42
  5192.5   115.9  5212.5   116.2  5337.9   126.4  5391.9  128.02  5407.9     129
#Mann= 4 ,-1 , 0
  3747.7     .05       0  4925.1     .07       0  5047.9     .05       0
  5391.9     .09       0
#XS Ineff= 2 , 0
       0    4525   119.5               0
Permanent Ineff=
       F       F
Bank Sta=4925.1,5047.9
XS Rating Curve= 0
Exp/Cntr=.5,.3

Type RM Length L Ch R = 1 ,13515.3 ,54.1,54.1,54.1
BEGIN DESCRIPTION:
Upstream Section of Bridge/Culvert/Weir
END DESCRIPTION:
XS GIS Cut Line= 3
      3068617.86      13972030.7      3069161.59      13970940.4
      3069191.65      13970773.2
#Sta/Elev= 30
  4089.9  121.23  4156.3  120.43  4346.3  112.53  4356.3  112.53  4376.3  115.03
  4406.3  117.13  4456.3  118.83  4586.3  118.73  4686.3  114.03  4726.3  113.43
  4766.3  114.03  4777.7  117.46  4893.1  118.48  4925.1  113.13  4972.2  106.78
  4985.8  103.37  4990.4   98.96  4998.5    97.2    5009   98.76    5014  103.92
    5042  108.84  5047.9   111.7  5076.2  117.05  5117.7  119.15    5170  118.08
  5328.8  121.52  5379.4  124.37  5402.7  125.79  5464.6  130.53  5478.1  129.43
#Mann= 7 , 1 , 0
  4089.9      .2       0  4089.9     .05       0  4925.1     .07       0
  5047.9     .09       0  5328.8     .05       0  5379.4     .05       0
  5402.7     .09       0
#XS Ineff= 2 , 0
       0    4892     119    5087       0  118.89
Permanent Ineff=
       F       F
Bank Sta=4925.1,5047.9
XS Rating Curve= 0
Exp/Cntr=.5,.3

Type RM Length L Ch R = 3 ,13488.2 ,,,
BEGIN DESCRIPTION:
NORTHCREST ROAD
Structure ID: BR M100-00-00-04
END DESCRIPTION:
Node Name=Northcrest Rd
Bridge Culvert--1,0,-1,-1, 0
Deck Dist Width WeirC Skew NumUp NumDn MinLoCord MaxHiCord MaxSubmerge Is_Ogee
10,34.1,2.6,0, 41, 41, , , .95, 0, 1,1,,
  4089.9  4116.3  4156.3  4286.3  4306.3  4346.3  4356.3  4376.3  4406.3  4456.3
  4586.3  4669.9  4686.3  4689.9  4706.3  4726.3  4756.3  4766.3  4777.7  4809.9
  4822.4  4871.4  4893.1  4901.9 4902.11  4902.2  4936.7  4972.2    4992  5007.7
  5042.4 5076.99  5077.1  5077.4  5117.7    5170  5226.3  5334.6  5424.6  5464.6
  5478.1
   121.2  121.41  120.47  119.05   118.9  118.91  118.92  118.92  118.93  118.94
  118.98     119  118.67   118.6  118.57  118.54  118.49  118.47  118.45   118.4
  118.74  119.31  119.79  119.98  120.04  120.04  121.51  122.65  122.83  122.65
   121.5  119.98  119.97  119.91  119.13  118.42  119.61  121.61  127.11  130.51
   129.4
   121.2   121.4   120.4   114.6   114.2   112.5   112.5     115   117.1   118.8
   118.7  114.77     114     114     114   113.4   113.4     114  117.43  117.38
  117.36  118.22  118.45  117.02  116.99  118.64  120.11  121.25  121.43  121.25
   120.1  118.58  117.07  117.08  119.12  118.05   119.6   121.6   127.1   130.5
   129.4
  4089.9  4116.3  4156.3  4286.3  4306.3  4346.3  4356.3  4376.3  4406.3  4456.3
  4586.3  4669.9  4686.3  4689.9  4706.3  4726.3  4756.3  4766.3  4777.7  4809.9
  4822.4  4871.4  4893.1  4901.9 4902.11  4902.2  4936.7  4972.2    4992  5007.7
  5042.4 5076.99  5077.1  5077.4  5117.7    5170  5226.3  5334.6  5424.6  5464.6
  5478.1
  121.98  122.18  121.18  119.05   118.9  118.91  118.92  118.92  118.93  119.58
  119.48     119  118.67   118.6  118.57  118.54  118.49  118.47  118.45   118.4
  118.74  119.31  119.79  119.98  120.04  120.04  121.51  122.65  122.83  122.65
   121.5  119.98  119.97  119.91   119.9  118.83  120.38  122.38  127.88  131.28
  130.18
  121.98  122.18  121.18  115.38  114.98  113.28  113.28  115.78  117.88  119.58
  119.48  115.55  114.78  114.78  114.78  114.18  114.18  114.78  118.21  118.16
  118.14     119  119.23   117.8  117.77  119.42  120.89  122.03  122.21  122.03
  120.88  119.36  117.85  117.86   119.9  118.83  120.38  122.38  127.88  131.28
  130.18
Pier Skew, UpSta & Num, DnSta & Num=  ,4936.7, 2 ,4936.7, 2 , 0 , 0 , 0 ,,
     1.2     1.2
  110.86  121.13
     1.2     1.2
  111.64  121.91
Pier Skew, UpSta & Num, DnSta & Num=  ,4972.3, 2 ,4972.3, 2 , 0 , 0 , 0 ,,
     1.2     1.2
  105.57  122.26
     1.2     1.2
  106.35  123.04
Pier Skew, UpSta & Num, DnSta & Num=  ,5007, 2 ,5007, 2 , 0 , 0 , 0 ,,
     1.2     1.2
   97.35  122.27
     1.2     1.2
   98.13  123.05
Pier Skew, UpSta & Num, DnSta & Num=  ,5042, 2 ,5042, 2 , 0 , 0 , 0 ,,
     1.2     1.2
   107.7  121.13
     1.2     1.2
  108.48  121.91
Abutment Skew #Up #Dn= , 2 , 2
    4902  4903.2
  118.64  116.81
    4902  4903.2
  119.42  117.59
BR Coef= 1 , 1 , 1 ,1.25, 0 ,,,.8,0,2,0,
WSPro=,,,, 1 ,,,, 0 ,,,, 0 ,,,,-1 ,-1 ,-1 , 0 , 0 , 0 , 0 , 0
BR U #Sta/Elev= 74
  4089.9   121.2  4116.3   121.4  4156.3   120.4  4286.3   114.6  4299.9  114.33
  4306.3   114.2  4346.3   112.5  4356.3   112.5  4376.3     115  4406.3   117.1
  4456.3   118.8  4586.3   118.7  4669.9  114.77  4686.3     114  4689.9     114
  4706.3     114  4726.3   113.4  4756.3   113.4  4766.3     114  4777.7  117.43
  4809.9  117.38  4821.5  117.36  4822.4  117.36  4871.3  118.22  4871.4  118.22
  4893.1  118.45  4901.9  117.02    4902  117.01 4902.11  116.99  4902.2  116.98
  4902.3  116.96  4903.1  116.83  4903.2  116.81  4925.1   113.1  4936.2     112
  4936.7  111.95  4958.3  108.81  4972.2  106.75  4972.3  106.72  4985.8  103.34
  4989.6  100.05  4990.4   98.93    4992   98.58  4998.5   97.17  5007.7   98.54
    5009   98.73  5010.4  100.08    5014  103.89    5042  108.81  5042.4     109
  5047.9  111.67  5074.4  116.78  5076.2  117.02  5076.3  117.03  5076.9  117.06
 5076.99  117.06  5077.1  117.07  5077.2  117.07  5077.4  117.08  5117.7  119.12
  5124.2  118.99    5170  118.05  5226.3   119.6  5249.9  120.04  5299.9  120.96
  5328.8  121.49  5334.6   121.6  5338.1  121.81  5378.1  124.26  5379.4  124.34
  5402.7  125.76  5424.6   127.1  5464.6   130.5  5478.1   129.4
BR U #Mann= 6
  4089.9     .05  4925.1     .06  5047.9     .09  5328.8     .05  5379.4     .05
  5402.7     .09
BR U Banks=4925.1,5047.9
BR D #Sta/Elev= 74
  4089.9  121.98  4116.3  122.18  4156.3  121.18  4286.3  115.38  4299.9  115.11
  4306.3  114.98  4346.3  113.28  4356.3  113.28  4376.3  115.78  4406.3  117.88
  4456.3  119.58  4586.3  119.48  4669.9  115.55  4686.3  114.78  4689.9  114.78
  4706.3  114.78  4726.3  114.18  4756.3  114.18  4766.3  114.78  4777.7  118.21
  4809.9  118.16  4821.5  118.14  4822.4  118.14  4871.3     119  4871.4     119
  4893.1  119.23  4901.9   117.8    4902  117.79 4902.11  117.77  4902.2  117.76
  4902.3  117.74  4903.1  117.61  4903.2  117.59  4925.1  113.88  4936.2  112.78
  4936.7  112.73  4958.3  109.59  4972.2  107.53  4972.3   107.5  4985.8  104.12
  4989.6  100.83  4990.4   99.71    4992   99.36  4998.5   97.95  5007.7   99.32
    5009   99.51  5010.4  100.86    5014  104.67    5042  109.59  5042.4  109.78
  5047.9  112.45  5074.4  117.56  5076.2   117.8  5076.3  117.81  5076.9  117.84
 5076.99  117.84  5077.1  117.85  5077.2  117.85  5077.4  117.86  5117.7   119.9
  5124.2  119.77    5170  118.83  5226.3  120.38  5249.9  120.82  5299.9  121.74
  5328.8  122.27  5334.6  122.38  5338.1  122.59  5378.1  125.04  5379.4  125.12
  5402.7  126.54  5424.6  127.88  5464.6  131.28  5478.1  130.18
BR D #Mann= 6
  4089.9     .05  4925.1     .06  5047.9     .09  5328.8     .05  5379.4     .05
  5402.7     .09
BR D Banks=4925.1,5047.9
BC Design=,, 0 ,, 0 ,,,,,,
BC HTab HWMax=130.53

Type RM Length L Ch R = 1 ,13461.2 ,35.6,35.6,35.6
BEGIN DESCRIPTION:
Downstream Section of Bridge/Culvert/Weir
END DESCRIPTION:
XS GIS Cut Line= 3
      3068674.92      13972084.6      3069207.47      13970955.7
       3069230.8      13970817.7
#Sta/Elev= 30
  4089.9  122.05  4156.3  121.25  4346.3  113.35  4356.3  113.35  4376.3  115.85
  4406.3  117.95  4456.3  119.65  4586.3  119.55  4686.3  114.85  4726.3  114.25
  4766.3  114.85  4777.7  118.28  4893.1   119.3  4925.1  113.95  4972.2   107.6
  4985.8  104.19  4990.4   99.78  4998.5   98.02    5009   99.58    5014  104.74
    5042  109.66  5047.9  112.52  5076.2  117.87  5117.7  119.97    5170   118.9
  5328.8  122.34  5379.4  125.19  5402.7  126.61  5464.6  131.35  5478.1  130.25
#Mann= 7 , 1 , 0
  4089.9      .2       0  4089.9     .05       0  4925.1     .07       0
  5047.9     .09       0  5328.8     .05       0  5379.4     .05       0
  5402.7     .09       0
#XS Ineff= 2 , 0
       0    4892     119    5087       0  118.89
Permanent Ineff=
       F       F
Bank Sta=4925.1,5047.9
XS Rating Curve= 0
Exp/Cntr=.5,.3

Type RM Length L Ch R = 1 ,13425.6 ,26.9,26.9,26.9
BEGIN DESCRIPTION:
Upstream Section of Bridge/Culvert/Weir
END DESCRIPTION:
XS GIS Cut Line= 5
      3068633.96      13972221.7       3068686.1      13972117.4
       3069145.4       13971168.      3069224.18      13970931.7
      3069284.79      13970671.1
#Sta/Elev= 30
  3954.7  119.03  3955.9  119.33  4262.5  118.33  4312.5  116.93  4362.5  116.73
  4372.5  116.33  4462.5  116.93  4542.5  119.13  4682.5  117.63  4762.5  116.33
  4822.5  116.43  4872.5  117.83  4892.4  117.53  4895.5  116.33  4941.2  113.19
  4989.2  102.58  4991.6  100.07  4992.9   98.27  5000.1   98.93  5006.4   98.91
  5008.4  100.11    5012  103.48  5048.7  113.23  5086.8  114.28  5122.4  113.08
  5152.2  112.79  5227.2  118.03  5348.1  122.98  5484.6  129.84  5493.8  130.63
#Mann= 5 ,-1 , 0
  3954.7     .05       0  4941.2     .07       0  5048.7      .1       0
  5348.1     .05       0  5484.6     .09       0
#XS Ineff= 3 ,-1
  3954.7    4894     119    4894  4941.2  113.82    5057  5493.8  113.77
Permanent Ineff=
       F       F       F
Bank Sta=4941.2,5048.7
XS Rating Curve= 0
Exp/Cntr=.5,.3

Type RM Length L Ch R = 3 ,13412.1 ,,,
BEGIN DESCRIPTION:
GOLF CART BRIDGE
Structure ID: M100-00-00-03
END DESCRIPTION:
Node Name=Golf Cart Br
Bridge Culvert--1,0,-1,-1, 0
Deck Dist Width WeirC Skew NumUp NumDn MinLoCord MaxHiCord MaxSubmerge Is_Ogee
10,6.9,2.6,0, 42, 41, , , .95, 0, 1,1,,
  3954.7  3955.9  4243.3  4262.5  4312.5  4362.5  4372.5  4462.5  4542.5  4633.3
  4673.3  4682.5  4692.5  4712.5  4762.5  4822.5  4872.5  4892.4  4895.5  4941.2
  4942.2  4942.3  4959.8  4977.2  4994.8  5012.4  5029.9  5041.4  5046.9    5047
 5047.19  5048.7  5086.8  5122.4  5152.2  5163.8  5227.2  5283.8  5353.8  5376.3
  5486.3  5493.8
   119.1  119.41     119  118.41  117.01  116.81  116.41  117.01  119.21   119.2
  117.81  117.71  117.41  117.31  116.41  116.51  117.91  117.61  116.41  113.85
  113.82  118.31  119.52  120.41  120.78  120.39  119.51  118.69  118.27  113.77
  113.76  113.76  114.36  113.16  112.96  113.68  118.11   121.4   124.7  125.66
  130.38   130.7
   119.1   119.4  118.46   118.4     117   116.8   116.4     117   119.2  118.23
   117.8   117.7   117.4   117.3   116.4   116.5   117.9   117.6   116.4  113.26
  113.04  113.02  113.52  114.41  114.78  114.39  113.51  112.69  112.82  112.84
  112.89   113.3  114.35  113.15  112.86  113.67   118.1  120.42  123.28   124.2
     130   130.7
  3954.7  3955.9  4243.3  4262.5  4312.5  4362.5  4372.5  4462.5  4542.5  4633.3
  4673.3  4682.5  4692.5  4712.5  4762.5  4822.5  4872.5  4892.4  4895.5  4941.2
  4942.1  4942.2  4959.8  4977.2  4994.8  5012.4  5029.9  5041.4  5046.9    5047
 5047.19  5048.7  5086.8  5122.4  5152.2  5227.2  5283.8  5353.8  5376.3  5486.3
  5493.8
   119.2   119.5     119   118.5   117.1   116.9   116.5   117.1   119.3   119.2
   117.9   117.8   117.5   117.4   116.5   116.6     118   117.7   116.5  113.85
  113.82  118.32  119.52  120.41  120.78  120.39  119.51  118.69  118.27  113.77
  113.76  113.76  114.45  113.25  112.96   118.2   121.4   124.7  125.66  130.38
   130.8
   119.2   119.5  118.56   118.5   117.1   116.9   116.5   117.1   119.3  118.33
   117.9   117.8   117.5   117.4   116.5   116.6     118   117.7   116.5  113.36
  113.16  113.14  113.62  114.51  114.88  114.49  113.61  112.79  112.92  112.94
  112.99   113.4  114.45  113.25  112.96   118.2  120.52  123.38   124.3   130.1
   130.8
BR Coef= 1 , 1 , 0 ,1.25, 0 ,,,.8,0,2,0,
WSPro=,,,, 1 ,,,, 0 ,,,, 0 ,,,,-1 ,-1 ,-1 , 0 , 0 , 0 , 0 , 0
BR U #Sta/Elev= 73
  3954.7   119.1  3955.9   119.4  4243.3  118.46  4262.5   118.4  4303.3  117.26
  4312.5     117  4353.3  116.84  4362.5   116.8  4372.5   116.4  4383.3  116.47
  4423.3  116.74  4433.3  116.81  4462.5     117  4513.3   118.4  4542.5   119.2
  4633.3  118.23  4673.3   117.8  4682.5   117.7  4692.5   117.4  4712.5   117.3
  4733.3  116.93  4762.5   116.4  4783.3  116.43  4822.5   116.5  4833.3   116.8
  4846.6  117.17  4872.5   117.9  4892.4   117.6  4892.5  117.56  4895.5   116.4
  4941.2  113.26  4941.8  113.13 4941.91   113.1    4942  113.08  4942.1  113.06
  4942.2  113.04  4942.3  113.02  4959.8  109.18  4964.7   108.1  4977.2  105.32
  4989.2  102.65  4991.6  100.14  4992.9   98.34  4994.8   98.51  5000.1      99
  5006.4   98.98  5008.4  100.18    5012  103.55  5012.4  103.65  5023.9  106.62
  5029.9  108.24  5041.4  111.33  5046.9  112.82    5047  112.84  5047.1  112.87
 5047.19  112.89  5047.3  112.92  5047.4  112.95  5048.7   113.3  5086.7  114.35
  5086.8  114.35  5120.6  113.21  5122.4  113.15  5152.2  112.86  5163.8  113.67
  5227.2   118.1  5283.8  120.42  5348.1  123.05  5353.8  123.28  5376.3   124.2
  5484.6  129.91  5486.3     130  5493.8   130.7
BR U #Mann= 5
  3954.7     .05  4941.2     .06  5048.7      .1  5348.1     .05  5484.6     .09
BR U Banks=4941.2,5048.7
BR D #Sta/Elev= 73
  3954.7   119.2  3955.9   119.5  4243.3  118.56  4262.5   118.5  4303.3  117.36
  4312.5   117.1  4353.3  116.94  4362.5   116.9  4372.5   116.5  4383.3  116.57
  4423.3  116.84  4433.3  116.91  4462.5   117.1  4513.3   118.5  4542.5   119.3
  4633.3  118.33  4673.3   117.9  4682.5   117.8  4692.5   117.5  4712.5   117.4
  4733.3  117.03  4762.5   116.5  4783.3  116.53  4822.5   116.6  4833.3   116.9
  4846.6  117.27  4872.5     118  4892.4   117.7  4892.5  117.66  4895.5   116.5
  4941.2  113.36  4941.8  113.23 4941.91   113.2    4942  113.18  4942.1  113.16
  4942.2  113.14  4942.3  113.12  4959.8  109.28  4964.7   108.2  4977.2  105.42
  4989.2  102.75  4991.6  100.24  4992.9   98.44  4994.8   98.61  5000.1    99.1
  5006.4   99.08  5008.4  100.28    5012  103.65  5012.4  103.75  5023.9  106.72
  5029.9  108.34  5041.4  111.43  5046.9  112.92    5047  112.94  5047.1  112.97
 5047.19  112.99  5047.3  113.02  5047.4  113.05  5048.7   113.4  5086.7  114.45
  5086.8  114.45  5120.6  113.31  5122.4  113.25  5152.2  112.96  5163.8  113.77
  5227.2   118.2  5283.8  120.52  5348.1  123.15  5353.8  123.38  5376.3   124.3
  5484.6  130.01  5486.3   130.1  5493.8   130.8
BR D #Mann= 5
  3954.7     .05  4941.2     .06  5048.7      .1  5348.1     .05  5484.6     .09
BR D Banks=4941.2,5048.7
BC Design=,, 0 ,, 0 ,,,,,,
BC HTab HWMax=130.63

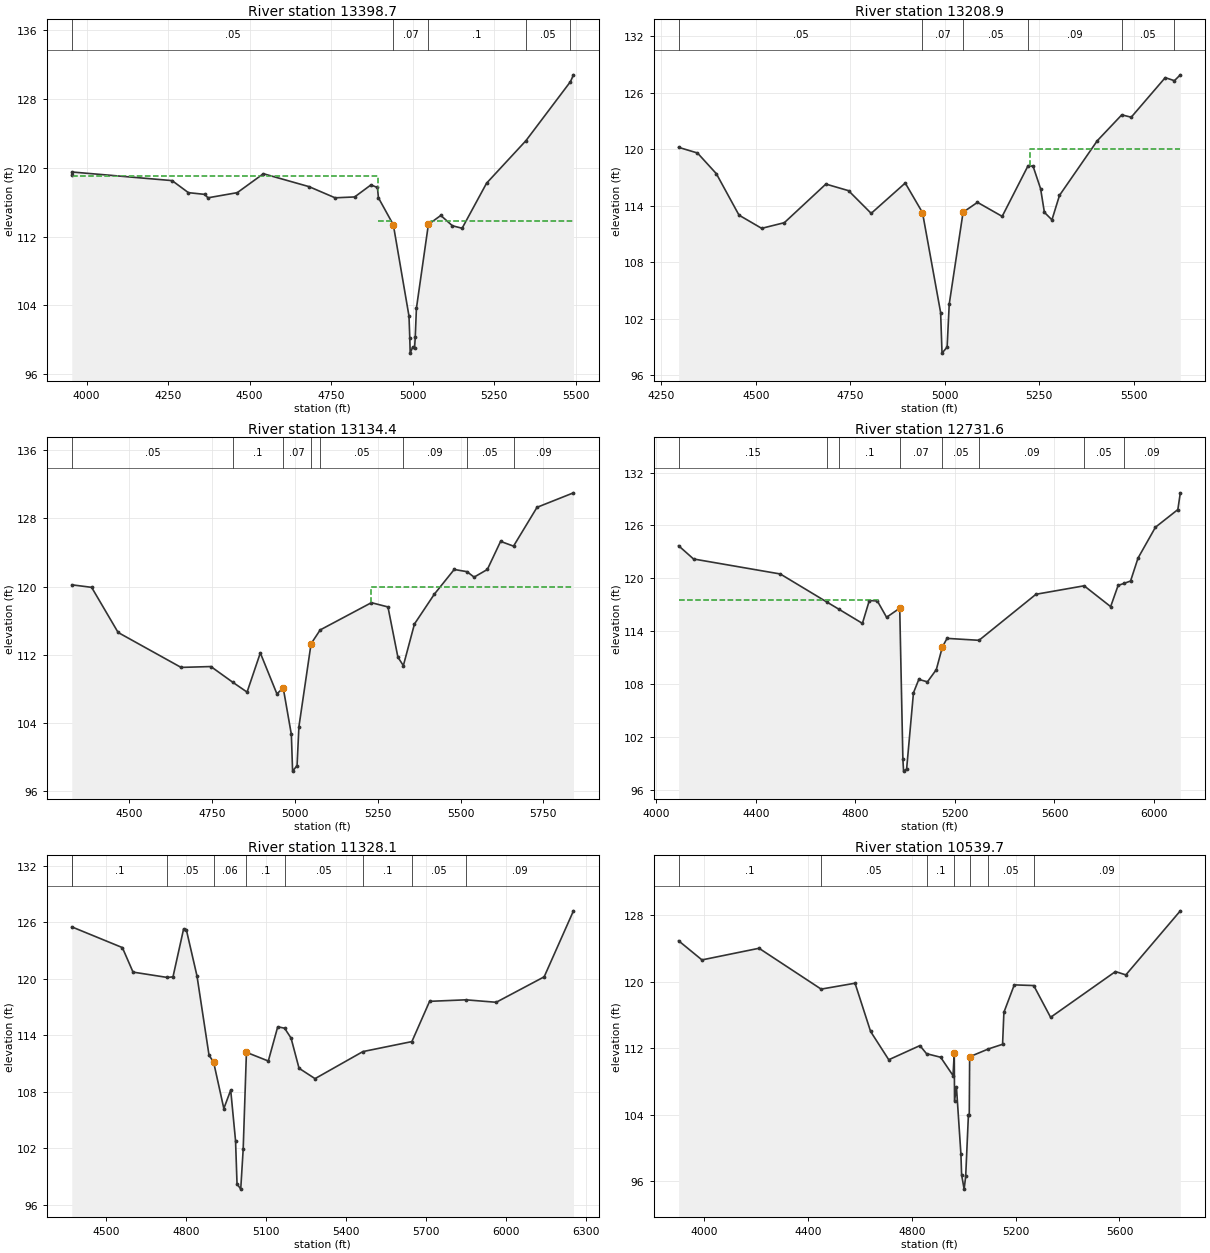
Type RM Length L Ch R = 1 ,13398.7 ,103.5,189.75,148.5
BEGIN DESCRIPTION:
Downstream Section of Bridge/Culvert/Weir
END DESCRIPTION:
XS GIS Cut Line= 4
      3068651.19      13972236.5      3068748.95       13972041.
      3069164.04      13971196.7      3069314.17      13970658.7
#Sta/Elev= 30
  3954.7   119.2  3955.9   119.5  4262.5   118.5  4312.5   117.1  4362.5   116.9
  4372.5   116.5  4462.5   117.1  4542.5   119.3  4682.5   117.8  4762.5   116.5
  4822.5   116.6  4872.5     118  4892.4   117.7  4895.5   116.5  4941.2  113.36
  4989.2  102.75  4991.6  100.24  4992.9   98.44  5000.1    99.1  5006.4   99.08
  5008.4  100.28    5012  103.65  5048.7   113.4  5086.8  114.45  5122.4  113.25
  5152.2  112.96  5227.2   118.2  5348.1  123.15  5484.6  130.01  5493.8   130.8
#Mann= 5 ,-1 , 0
  3954.7     .05       0  4941.2     .07       0  5048.7      .1       0
  5348.1     .05       0  5484.6     .09       0
#XS Ineff= 3 ,-1
  3954.7    4894     119    4894  4941.2  113.82    5057  5493.8  113.77
Permanent Ineff=
       F       F       F
Bank Sta=4941.2,5048.7
XS Rating Curve= 0
Exp/Cntr=.5,.3

Type RM Length L Ch R = 1 ,13208.9 ,57.08,74.5,42.59
BEGIN DESCRIPTION:
Cross Section 13208.9
Cross Section XS8.3
END DESCRIPTION:
XS GIS Cut Line= 4
      3068803.95      13972003.8      3069140.75      13971572.2
      3069262.12      13971387.2      3069320.29      13970830.3
#Sta/Elev= 30
  4295.3   120.2  4345.3   119.6  4395.3   117.4  4455.3     113  4515.3   111.6
  4575.3   112.2  4685.3   116.3  4745.3   115.6  4805.3  113.19  4895.5  116.41
  4941.2  113.27  4989.2  102.66  4992.9   98.35  5006.4   98.99    5012  103.56
  5048.7  113.31  5086.8  114.36  5152.2  112.87  5220.8  118.25    5234   118.2
    5254   115.8    5264   113.3    5284   112.5    5304   115.1    5404   120.9
  5468.9  123.65    5494   123.4    5584   127.6  5608.3  127.28    5624   127.9
#Mann= 6 ,-1 , 0
  4295.3     .05       0  4941.2     .07       0  5048.7     .05       0
  5220.8     .09       0  5468.9     .05       0  5608.3     .09       0
#XS Ineff= 2 , 0
       0                    5225       0     120
Permanent Ineff=
       F       F
Bank Sta=4941.2,5048.7
XS Rating Curve= 0
Exp/Cntr=.3,.1

Type RM Length L Ch R = 1 ,13134.4 ,493.45,402.8,359.6
BEGIN DESCRIPTION:
Cross Section 13134.4
Cross Section XS8.1
END DESCRIPTION:
XS GIS Cut Line= 4
      3068834.74      13972020.8      3069185.01      13971624.1
      3069288.51      13971470.4      3069390.76       13970677.
#Sta/Elev= 30
  4326.3   120.2  4386.3   119.9  4466.3   114.6  4656.3   110.5  4746.3   110.6
  4813.3  108.73  4855.5   107.6  4895.5   112.2  4945.5   107.4  4964.7  108.08
  4989.2  102.63  4992.9   98.32  5006.4   98.96    5012  103.53  5048.7  113.28
  5076.2   114.9  5230.8   118.1  5280.8   117.6  5310.8   111.7  5327.3  110.71
  5360.8   115.6  5420.8   119.1  5480.8     122  5519.5  121.74  5540.8   121.1
  5580.8     122  5620.8   125.3  5659.8  124.74  5730.8   129.3  5840.8     131
#Mann= 8 ,-1 , 0
  4326.3     .05       0  4813.3      .1       0  4964.7     .07       0
  5048.7      .1       0  5076.2     .05       0  5327.3     .09       0
  5519.5     .05       0  5659.8     .09       0
#XS Ineff= 2 , 0
       0                    5230       0     120
Permanent Ineff=
       F       F
Bank Sta=4964.7,5048.7
XS Rating Curve= 0
Exp/Cntr=.3,.1

Type RM Length L Ch R = 1 ,12731.6 ,1265.5,1403.5,807.1
BEGIN DESCRIPTION:
Cross Section 12731.6
Cross Section XS08
END DESCRIPTION:
XS GIS Cut Line= 4
      3069551.39      13972640.9      3069468.61      13972240.7
      3069637.23      13971420.5      3069471.91      13970668.4
#Sta/Elev= 30
  4089.7   123.7  4149.7   122.2  4498.3   120.5  4685.4  117.32  4734.7  116.49
  4828.3   114.9    4856  117.49  4888.3  117.44  4925.4  115.59  4978.2  116.62
  4990.9    99.5  4993.7   98.15  5005.9   98.39  5033.4  107.03  5054.9  108.55
  5089.5  108.27  5125.3  109.66  5149.5  112.22  5168.3   113.2  5296.7  112.98
  5525.7   118.2  5719.2  119.16  5825.7   116.8  5855.7   119.2    5879  119.43
  5905.7   119.7  5935.7   122.3  6005.7   125.8  6095.7   127.8  6105.7   129.7
#Mann= 8 ,-1 , 0
  4089.7     .15       0  4685.4     .05       0  4734.7      .1       0
  4978.2     .07       0  5149.5     .05       0  5296.7     .09       0
  5719.2     .05       0    5879     .09       0
#XS Ineff= 2 , 0
       0    4890   117.5    5720       0     119
Permanent Ineff=
       F       F
Bank Sta=4978.2,5149.5
XS Rating Curve= 0
Exp/Cntr=.3,.1

Type RM Length L Ch R = 1 ,11328.1 ,607.06,788.4,533.71
BEGIN DESCRIPTION:
Cross Section 11328.1
Cross Section XS07
Cross Section M100-00-00-X07
Located At: 2ND DS NORTHCREST
Rise in Terrain in right overbank due to Golf Course
END DESCRIPTION:
XS GIS Cut Line= 3
      3071011.09      13971944.2      3070660.72      13971516.3
      3069681.98      13970615.7
#Sta/Elev= 30
  4371.6   125.5  4561.6   123.3  4601.6   120.7  4730.9  120.13  4751.6   120.2
  4791.6   125.3  4801.6   125.2  4841.6   120.3  4886.9  111.87  4903.8  111.18
  4942.4  106.23  4968.2  108.18  4986.4   102.8  4991.9   98.24  5005.8   97.68
    5015   101.9  5027.2  112.19  5109.3  111.27  5144.7   114.9  5170.5  114.75
  5194.7   113.7  5224.7   110.5  5284.7   109.4  5464.4  112.27  5648.2  113.33
  5714.7   117.6    5851  117.76  5964.7   117.5  6144.7   120.2  6254.7   127.2
#Mann= 9 , 1 , 0
  4371.6      .2       0  4371.6      .1       0  4730.9     .05       0
  4903.8     .06       0  5027.2      .1       0  5170.5     .05       0
  5464.4      .1       0  5648.2     .05       0    5851     .09       0
Bank Sta=4903.8,5027.2
XS Rating Curve= 0
Exp/Cntr=.3,.1

Type RM Length L Ch R = 1 ,10539.7 ,127.8,114.8,101.9
BEGIN DESCRIPTION:
Cross Section 10539.7
Cross Section XS06.5
END DESCRIPTION:
XS GIS Cut Line= 4
      3071232.69      13971540.1      3070542.24      13970752.2
      3070454.29      13970676.3      3069728.38      13970419.5
#Sta/Elev= 30
  3900.8   124.9  3990.8   122.6  4210.8     124  4450.2  119.09  4580.8   119.8
  4640.8     114  4710.8   110.6  4830.8   112.3  4856.4  111.33  4910.8   110.9
  4958.5   108.7  4963.3  111.43  4964.3  105.67  4971.8  107.27    4989   99.22
  4991.5   96.79  5001.3   95.05  5007.3   96.58  5017.8  103.94  5021.1  103.91
  5022.6  110.96    5095   111.9  5149.5  112.46  5154.6   116.3  5194.6   119.6
  5269.5  119.52  5334.6   115.7  5584.6   121.2  5624.6   120.8  5834.6   128.5
#Mann= 7 ,-1 , 0
  3900.8      .1       0  4450.2     .05       0  4856.4      .1       0
  4963.3     .06       0  5022.6      .1       0    5095     .05       0
  5269.5     .09       0
#XS Ineff= 2 , 0
       0                    5200       0   119.5
Permanent Ineff=
       F       F
Bank Sta=4963.3,5022.6
XS Rating Curve= 0
Exp/Cntr=.5,.3