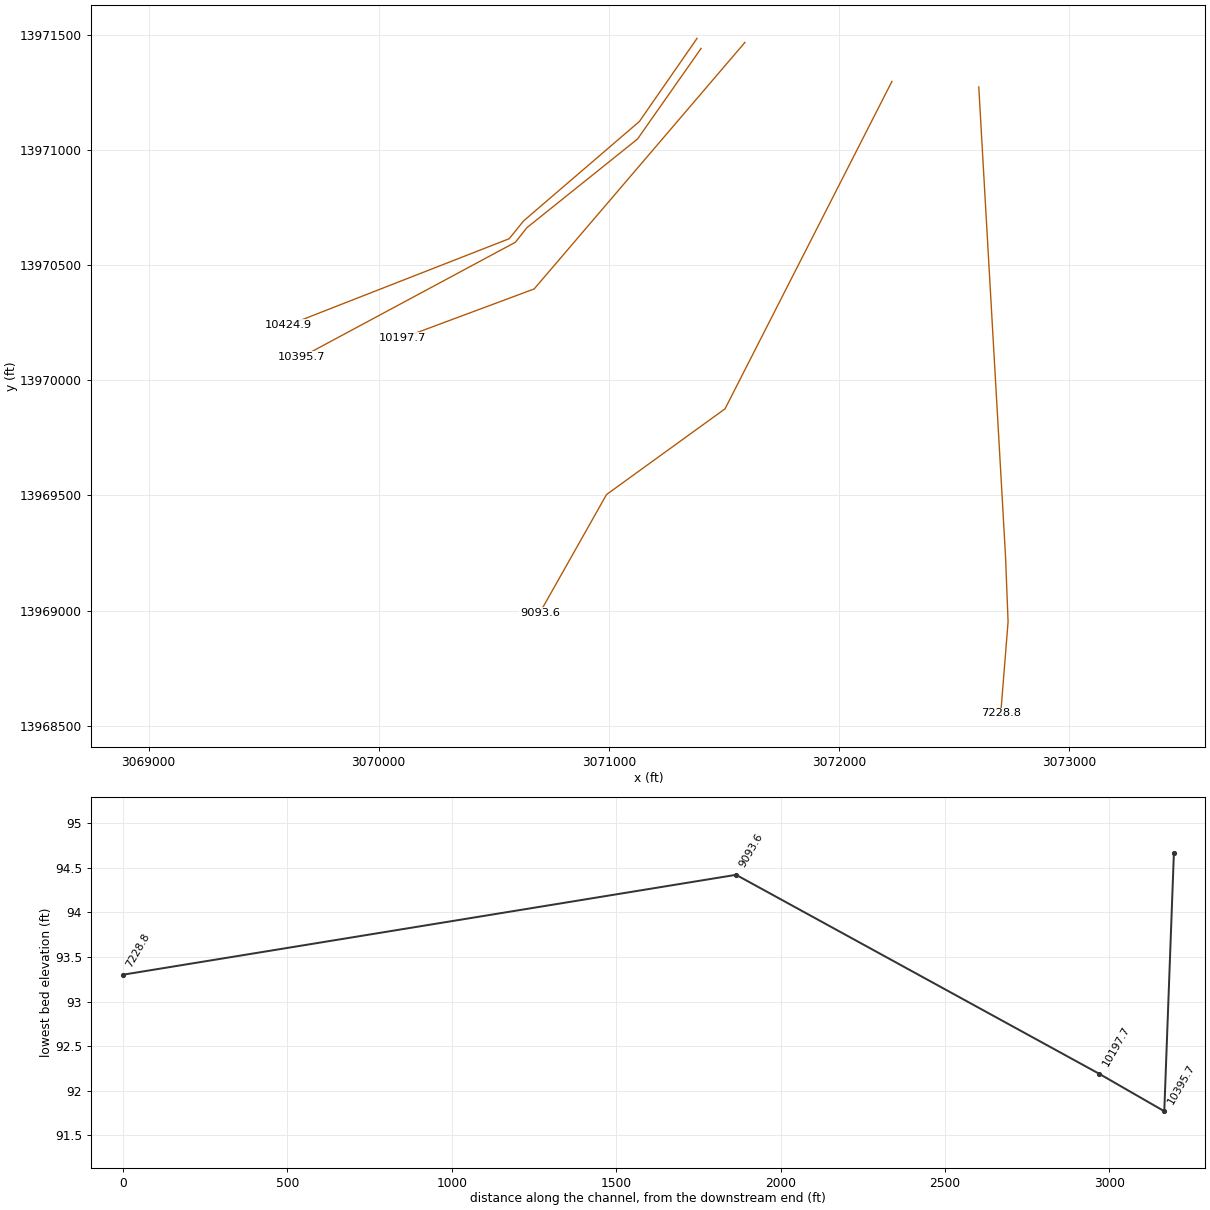
HEC-RAS study M100-00-00.prj: M100-00-00

--- M100-00-00.g01 (geometry) --- (continued)

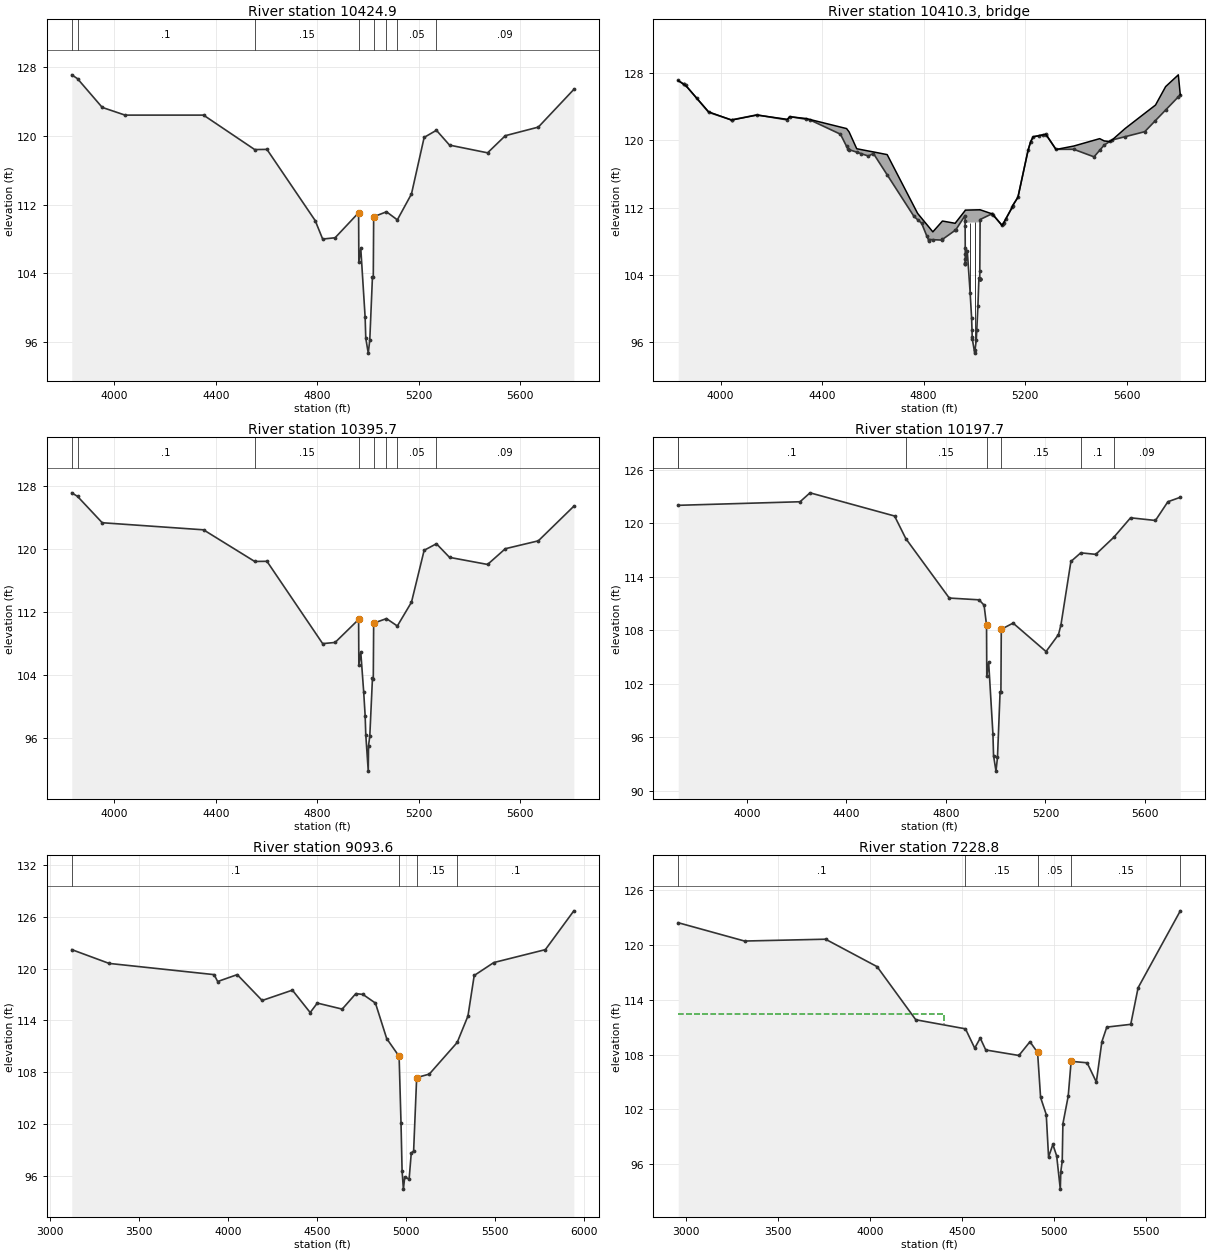
Type RM Length L Ch R = 1 ,10424.9 ,29.2,29.2,29.2
BEGIN DESCRIPTION:
Upstream Section of Bridge/Culvert/Weir
END DESCRIPTION:
XS GIS Cut Line= 5
      3071383.23      13971486.2      3071132.87      13971125.2
      3070629.82      13970693.2      3070567.07      13970615.6
      3069608.72      13970240.9
#Sta/Elev= 30
  3832.7  127.13  3855.3  126.68  3952.7  123.33  4042.7  122.43    4352  122.43
  4553.7  118.41    4602  118.43    4792  110.13  4821.6  107.97  4870.6  108.12
  4963.3  111.04  4964.2  105.28  4971.8  106.88    4989   98.83  4991.5    96.4
  5001.3   94.66  5007.3   96.19  5017.8  103.55  5021.1  103.52  5022.6  110.57
  5073.1  111.15  5115.9  110.21  5171.6  113.23  5221.6  119.83    5270  120.66
  5321.6  118.93  5471.6  118.03  5541.6  120.03  5671.6  121.03  5811.6  125.43
#Mann= 8 , 1 , 0
  3832.7      .2       0  3855.3      .1       0  4553.7     .15       0
  4963.3     .06       0  5022.6     .15       0  5073.1      .1       0
  5115.9     .05       0    5270     .09       0
#XS Ineff= 2 , 0
       0  4953.3   109.1  5032.6       0  109.84
Permanent Ineff=
       F       F
Bank Sta=4963.3,5022.6
XS Rating Curve= 0
Exp/Cntr=.5,.3

Type RM Length L Ch R = 3 ,10410.3 ,,,
BEGIN DESCRIPTION:
GOLF CART BRIDGE
Structure ID: M100-00-00-02
END DESCRIPTION:
Node Name=Golf Cart
Bridge Culvert--1,0,-1,-1, 0
Deck Dist Width WeirC Skew NumUp NumDn MinLoCord MaxHiCord MaxSubmerge Is_Ogee
10,9.2,2.6,0, 56, 56, , , .95, 0, 1,1,,
  3832.7  3862.7  3952.7  4042.7  4142.7  4262.7    4272  4336.2    4352    4472
  4496.2    4502  4506.2  4536.2    4582    4602  4656.2    4762  4776.2    4792
  4821.6  4822.4  4836.2  4870.6  4874.1  4924.1  4926.4  4963.3 4964.01  4964.1
 5020.79  5020.9  5021.1  5022.6  5070.1  5109.6  5149.5  5150.7  5171.6  5211.6
  5221.6  5231.6  5281.6  5321.6  5391.6  5471.6  5493.8  5511.6  5533.8  5541.6
  5593.8  5671.6  5713.8  5753.8  5803.8  5811.6
   127.1  126.51  123.39  122.41  123.01   122.5  122.81   122.6  122.48  121.58
   121.4  121.17     121     119  118.73  118.62   118.3  112.13   111.3  110.72
  109.64  109.61   109.1  110.27  110.39  110.12  110.21  111.63  111.69  111.69
  111.73  111.73  111.74  111.73  111.24  109.84  112.05  112.21  113.21  118.81
  119.81  120.41  120.71  118.91  119.32  120.01   120.2  119.93  119.85  120.01
   121.4  123.22   124.2   126.4   127.8   125.4
   127.1   126.5   123.3   122.4     123   122.4   122.8  122.48   122.4   120.7
  119.25   118.9  118.86  118.56   118.1   118.4  115.86   110.9  110.52   110.1
  107.94  108.16  108.14  108.09  108.17  109.25   109.3  111.01  106.46  110.19
  110.23  103.49  103.49  110.54  111.23  109.83  112.04   112.2   113.2   118.8
   119.8   120.4   120.7   118.9   118.9     118  118.78   119.4  119.84     120
   120.4     121  122.33  123.58  125.15   125.4
  3832.7  3862.7  3952.7  4042.7  4142.7  4262.7    4272  4336.2    4352    4472
  4496.2    4502  4506.2  4536.2    4582    4602  4656.2    4762  4776.2    4792
  4821.6  4822.4  4836.2  4870.6  4874.1  4924.1  4926.4  4963.3 4964.01  4964.1
 5020.79  5020.9  5021.1  5022.6  5070.1  5109.6  5149.5  5150.7  5171.6  5211.6
  5221.6  5231.6  5281.6  5321.6  5391.6  5471.6  5493.8  5511.6  5533.8  5541.6
  5593.8  5671.6  5713.8  5753.8  5803.8  5811.6
   127.1  126.51  123.39  122.41  123.01   122.5  122.81   122.6  122.48  121.58
   121.4  121.17     121     119  118.73  118.62   118.3  112.13   111.3  110.72
  109.64  109.61   109.1  110.27  110.39  110.12  110.21  111.63  111.69  111.69
  111.73  111.73  111.74  111.73  111.24  109.84  112.05  112.21  113.21  118.81
  119.81  120.41  120.71  118.91  119.32  120.01   120.2  119.93  119.85  120.01
   121.4  123.22   124.2   126.4   127.8   125.4
   127.1   126.5   123.3   122.4     123   122.4   122.8  122.48   122.4   120.7
  119.25   118.9  118.86  118.56   118.1   118.4  115.86   110.9  110.52   110.1
  107.94  108.16  108.14  108.09  108.17  109.25   109.3  111.01  106.46  110.19
  110.23  103.49  103.49  110.54  111.23  109.83  112.04   112.2   113.2   118.8
   119.8   120.4   120.7   118.9   118.9     118  118.78   119.4  119.84     120
   120.4     121  122.33  123.58  125.15   125.4
Pier Skew, UpSta & Num, DnSta & Num=  ,4983.2, 2 ,4983.2, 2 , 0 , 0 , 0 ,,
       1       1
  100.58  111.18
       1       1
   97.11  111.18
Pier Skew, UpSta & Num, DnSta & Num=  ,5002.5, 2 ,5002.5, 2 , 0 , 0 , 0 ,,
       1       1
   93.86   111.2
       1       1
      91   111.2
BR Coef= 1 , 1 , 1 ,1.25, 0 ,,,.8,0,2,0,
WSPro=,,,, 1 ,,,, 0 ,,,, 0 ,,,,-1 ,-1 ,-1 , 0 , 0 , 0 , 0 , 0
BR U #Sta/Elev= 92
  3832.7  127.13  3855.2  126.68  3855.3  126.68  3862.7  126.53  3905.2  125.02
  3952.7  123.33  4042.7  122.43  4045.2  122.45  4142.7  123.03  4262.7  122.43
    4272  122.83  4336.2  122.51    4352  122.43    4472  120.73  4496.2  119.28
    4502  118.93  4506.2  118.89  4536.2  118.59  4553.7  118.41    4582  118.13
    4602  118.43  4656.2  115.89    4762  110.93  4776.2  110.55    4792  110.13
    4812  108.63  4821.6  107.97  4822.4  108.19  4836.2  108.17  4870.6  108.12
  4874.1   108.2  4924.1  109.28  4926.4  109.33  4963.3  111.04  4963.4  110.38
  4963.5  109.74  4963.9  107.19 4964.01  106.49  4964.1  105.92  4964.2  105.28
  4964.3   105.3  4964.8  105.41  4971.8  106.88  4983.2  101.87    4989   98.83
  4990.6   97.39  4991.3   96.62  4991.5    96.4  5001.3   94.66  5002.4   95.02
  5007.3   96.19  5009.3   97.37  5013.8  100.22  5017.8  103.55  5020.6  103.52
 5020.67  103.52 5020.79  103.52  5020.9  103.52    5021  103.52  5021.1  103.52
  5021.3  104.46  5022.6  110.57  5069.1  111.25  5070.1  111.26  5073.1  111.15
  5109.6  109.86  5112.3  110.01  5115.9  110.21  5123.8  110.65  5149.5  112.07
  5150.7  112.23  5171.6  113.23  5211.6  118.83  5221.6  119.83  5231.6  120.43
  5253.8  120.56    5270  120.66  5281.6  120.73  5283.8  120.63  5321.6  118.93
  5391.6  118.93  5471.6  118.03  5493.8  118.81  5511.6  119.43  5533.8  119.87
  5541.6  120.03  5593.8  120.43  5671.6  121.03  5713.8  122.36  5753.8  123.61
  5803.8  125.18  5811.6  125.43
BR U #Mann= 8
  3832.7      .2  3855.3      .1  4553.7     .15  4963.3     .05  5022.6     .15
  5073.1      .1  5115.9     .05    5270     .09
BR D #Sta/Elev= 92
  3832.7  127.13  3855.2  126.68  3855.3  126.68  3862.7  126.53  3905.2  125.02
  3952.7  123.33  4042.7  122.43  4045.2  122.45  4142.7  123.03  4262.7  122.43
    4272  122.83  4336.2  122.51    4352  122.43    4472  120.73  4496.2  119.28
    4502  118.93  4506.2  118.89  4536.2  118.59  4553.7  118.41    4582  118.13
    4602  118.43  4656.2  115.89    4762  110.93  4776.2  110.55    4792  110.13
    4812  108.63  4821.6  107.97  4822.4  108.19  4836.2  108.17  4870.6  108.12
  4874.1   108.2  4924.1  109.28  4926.4  109.33  4963.3  111.04  4963.4  110.38
  4963.5  109.74  4963.9  107.19 4964.01  106.49  4964.1  105.92  4964.2  105.28
  4964.3   105.3  4964.8  105.41  4971.8  106.88  4983.2  101.87    4989   98.83
  4990.6   97.39  4991.3   96.62  4991.5    96.4  5001.3   91.77  5002.4   95.02
  5007.3   96.19  5009.3   97.37  5013.8  100.22  5017.8  103.55  5020.6  103.52
 5020.67  103.52 5020.79  103.52  5020.9  103.52    5021  103.52  5021.1  103.52
  5021.3  104.46  5022.6  110.57  5069.1  111.25  5070.1  111.26  5073.1  111.15
  5109.6  109.86  5112.3  110.01  5115.9  110.21  5123.8  110.65  5149.5  112.07
  5150.7  112.23  5171.6  113.23  5211.6  118.83  5221.6  119.83  5231.6  120.43
  5253.8  120.56    5270  120.66  5281.6  120.73  5283.8  120.63  5321.6  118.93
  5391.6  118.93  5471.6  118.03  5493.8  118.81  5511.6  119.43  5533.8  119.87
  5541.6  120.03  5593.8  120.43  5671.6  121.03  5713.8  122.36  5753.8  123.61
  5803.8  125.18  5811.6  125.43
BR D #Mann= 8
  3832.7      .2  3855.3      .1  4553.7     .15  4963.3     .05  5022.6     .15
  5073.1      .1  5115.9     .05    5270     .09
BC Design=,, 0 ,, 0 ,,,,,,
BC HTab HWMax=127.13

Type RM Length L Ch R = 1 ,10395.7 ,198,198,198
BEGIN DESCRIPTION:
Downstream Section of Bridge/Culvert/Weir
END DESCRIPTION:
XS GIS Cut Line= 5
      3071400.79      13971442.5      3071124.55      13971048.7
       3070643.6      13970663.3      3070593.83      13970600.1
      3069666.08       13970102.
#Sta/Elev= 30
  3832.7  127.13  3855.3  126.68  3952.7  123.33    4352  122.43  4553.7  118.41
    4602  118.43  4821.6  107.97  4870.6  108.12  4963.3  111.04  4964.2  105.28
  4971.8  106.88  4983.2  101.87    4989   98.83  4991.5    96.4  5001.3   91.77
  5002.4   95.02  5007.3   96.19  5017.8  103.55  5021.1  103.52  5022.6  110.57
  5073.1  111.15  5115.9  110.21  5171.6  113.23  5221.6  119.83    5270  120.66
  5321.6  118.93  5471.6  118.03  5541.6  120.03  5671.6  121.03  5811.6  125.43
#Mann= 8 ,-1 , 0
  3832.7      .2       0  3855.3      .1       0  4553.7     .15       0
  4963.3     .06       0  5022.6     .15       0  5073.1      .1       0
  5115.9     .05       0    5270     .09       0
#XS Ineff= 2 , 0
       0    4952  110.12    5033       0  109.73
Permanent Ineff=
       F       F
Bank Sta=4963.3,5022.6
XS Rating Curve= 0
Exp/Cntr=.5,.3

Type RM Length L Ch R = 1 ,10197.7 ,978.82,1104.1,949.05
BEGIN DESCRIPTION:
Cross Section 10197.7
Cross Section XS06
END DESCRIPTION:
XS GIS Cut Line= 3
      3071591.16      13971468.4      3070675.44      13970397.3
      3070103.81      13970184.4
#Sta/Elev= 30
  3723.4     122  4213.4   122.4  4253.4   123.4  4593.4   120.8  4638.8  118.26
  4813.4   111.6  4933.4   111.4  4953.4   110.8  4963.3  108.57  4964.3  102.81
  4971.8  104.41    4989   96.36  4991.5   93.93  5001.3   92.19  5007.3   93.72
  5017.8  101.08  5021.1  101.05  5022.6   108.1  5070.1  108.79  5202.6   105.6
  5252.6   107.5  5262.6   108.6  5302.6   115.7  5342.3  116.67  5402.6   116.5
  5475.7  118.43  5542.6   120.6  5642.6   120.3  5692.6   122.4  5742.6   122.9
#Mann= 7 , 1 , 0
  3723.4      .2       0  3723.4      .1       0  4638.8     .15       0
  4963.3     .06       0  5022.6     .15       0  5342.3      .1       0
  5475.7     .09       0
Bank Sta=4963.3,5022.6
XS Rating Curve= 0
Exp/Cntr=.3,.1

Type RM Length L Ch R = 1 ,9093.6  ,1368.06,1864.8,1736.58
BEGIN DESCRIPTION:
Cross Section 9093.6
Cross Section M100-00-00-X05
Located At: US GOSLING
Cross Section XS05
END DESCRIPTION:
XS GIS Cut Line= 4
      3072229.88       13971299.      3071504.79      13969876.5
        3070990.      13969504.2      3070700.03      13968990.4
#Sta/Elev= 30
  3120.4   122.2  3330.4   120.6  3920.4   119.3  3940.4   118.5  4050.4   119.3
  4190.4   116.3  4360.4   117.5  4460.4   114.9  4500.4     116  4640.4   115.3
  4717.1   117.1  4757.1     117  4827.1     116  4890.5  111.88  4960.2  109.82
  4970.9  102.09  4976.9   96.56  4984.3   94.42  4991.9   95.85  5016.4   95.56
  5028.5    98.6  5041.8   98.85  5058.9  107.36  5129.8  107.76  5286.6  111.43
  5347.1   114.5  5382.3   119.2  5492.3   120.7  5782.3   122.2  5942.3   126.7
#Mann= 4 ,-1 , 0
  3120.4      .1       0  4960.2     .06       0  5058.9     .15       0
  5286.6      .1       0
Bank Sta=4960.2,5058.9
XS Rating Curve= 0
Exp/Cntr=.3,.1

Type RM Length L Ch R = 1 ,7228.8  ,82.7,87.6,77.4
BEGIN DESCRIPTION:
Cross Section XS04.5
END DESCRIPTION:
XS GIS Cut Line= 4
      3072607.23     13971274.97      3072723.36     13969237.79
      3072734.56     13968951.21      3072702.73     13968553.31
#Sta/Elev= 30
  2957.5   122.4  3317.5   120.4  3757.5   120.6  4037.5   117.6  4247.5   111.8
  4517.3  110.81  4567.5   108.7  4597.5   109.8  4627.5   108.5  4807.5   107.9
  4867.5   109.4 4908.95  108.23 4925.25  103.31 4955.95  101.45 4968.55   96.81
 4991.95   98.18 5012.65   96.92 5032.25    93.3 5035.05   95.21 5042.75   96.36
 5046.35  100.43 5075.25  103.46 5091.05  107.26    5178   107.1    5228     105
    5258   109.4  5284.8     111  5414.8   111.3  5454.8   115.3    5684   123.7
#Mann= 5 ,-1 , 0
  2957.5      .1       0  4517.3     .15       0 4908.95     .05       0
 5091.05     .15       0    5684      .2       0
#XS Ineff= 2 , 0
       0    4400   112.4               0
Permanent Ineff=
       F       F
Bank Sta=4908.95,5091.05
XS Rating Curve= 0
Exp/Cntr=.5,.3