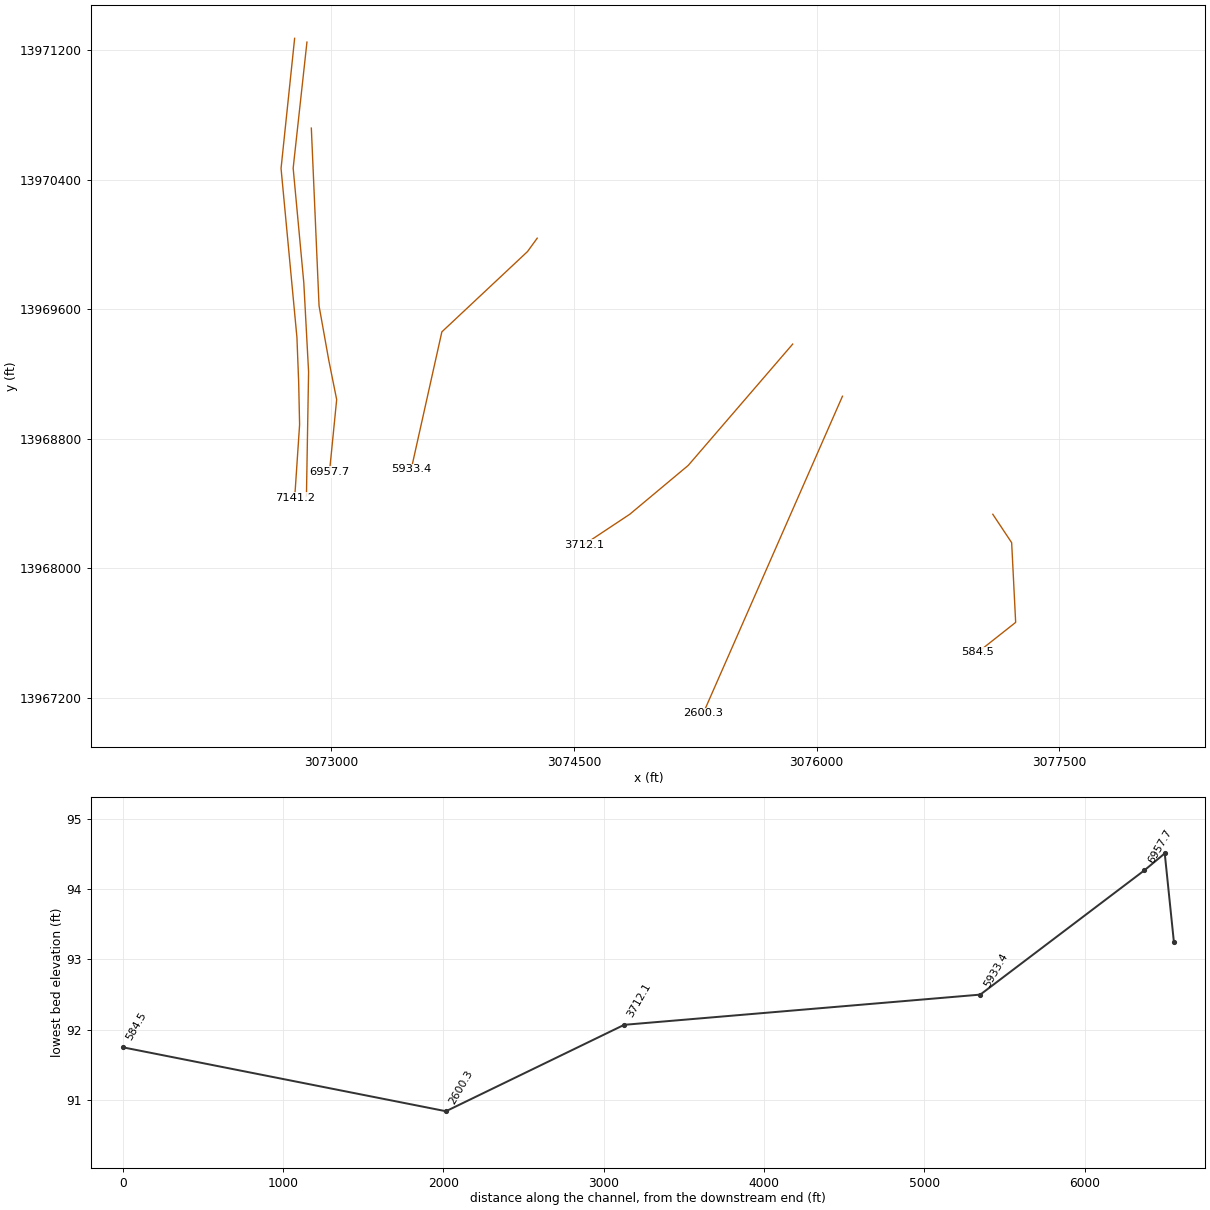
HEC-RAS study M100-00-00.prj: M100-00-00

--- M100-00-00.g01 (geometry) --- (continued)

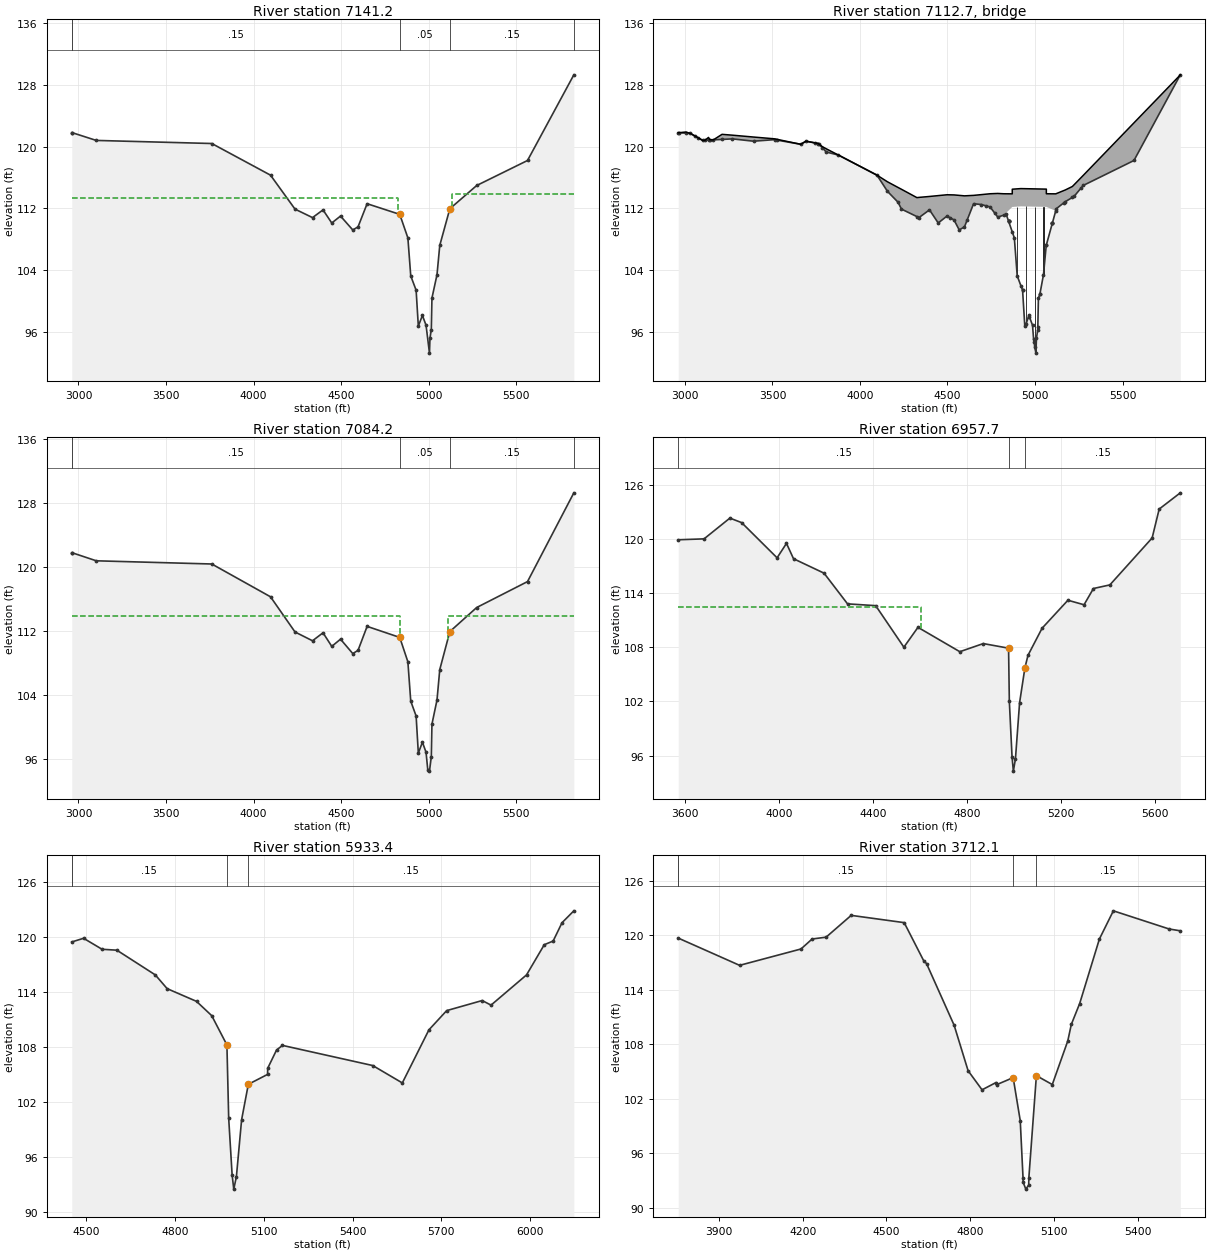
Type RM Length L Ch R = 1 ,7141.2  ,57,57,57
BEGIN DESCRIPTION:
Upstream Section of Bridge/Culvert/Weir
END DESCRIPTION:
XS GIS Cut Line= 6
      3072774.66      13971272.6      3072690.71      13970468.9
      3072788.82      13969424.8      3072799.59      13969146.8
       3072805.3       13968886.      3072775.16      13968435.7
#Sta/Elev= 30
  2961.7  121.81  2964.7  121.81  3101.7  120.81  3761.7  120.41  4097.1  116.31
  4237.1  111.91  4337.1  110.81  4397.1  111.81  4447.1  110.11  4497.1  111.01
  4567.1  109.21  4597.1  109.61    4649  112.61  4835.5  111.23  4881.9  108.18
  4898.3  103.26    4929   101.4  4941.6   96.76    4965   98.13  4985.7   96.87
  5005.3   93.25  5008.1   95.16  5015.8   96.31  5019.4  100.38  5048.3  103.41
  5064.1  107.21  5121.7  111.96  5275.1  114.97  5565.4  118.21  5830.1  129.31
#Mann= 5 , 1 , 0
  2961.7      .2       0  2964.7     .15       0  4835.5     .05       0
  5121.7     .15       0  5830.1      .2       0
#XS Ineff= 2 , 0
       0  4825.5   113.4  5131.7       0  113.92
Permanent Ineff=
       F       F
Bank Sta=4835.5,5121.7
XS Rating Curve= 0
Exp/Cntr=.5,.3

Type RM Length L Ch R = 3 ,7112.7  ,,,
BEGIN DESCRIPTION:
GOSLING
Structure ID: M100-00-00-01
END DESCRIPTION:
Node Name=Gosling
Bridge Culvert--1,0,-1,-1, 0
Deck Dist Width WeirC Skew NumUp NumDn MinLoCord MaxHiCord MaxSubmerge Is_Ogee
10,37,2.6,0, 48, 48, , , .95, 0, 1,1,,
  2961.7  3004.7  3031.7  3101.7  3114.7  3134.7    3142    3162    3212  3271.7
  3391.7  3511.7  3661.7  3691.7  3761.7  3785.2  3807.1  3877.1  4097.1  4157.1
  4217.1  4237.1  4325.2  4337.1  4397.1  4447.1  4497.1  4537.1  4567.1  4597.1
    4649  4694.2  4743.1  4787.1  4820.7    4870  4870.1  4918.9 5064.79  5064.8
  5118.4  5121.7  5172.8  5213.3  5223.4  5275.1  5565.4  5830.1
   121.8   121.9  121.71  120.81  120.83   121.2   120.9  120.88   121.6  121.49
  121.25  121.02  120.31  120.71  120.41     120  119.73  118.91  116.31  115.45
  114.72  114.48   113.4  113.43  113.55  113.66  113.77  113.75  113.69  113.63
  113.69  113.79   113.9  113.94   113.9  113.89  114.49  114.57   114.5   113.9
  113.89  113.92  114.39  114.84  115.07  116.27  123.09   129.3
   121.8  121.74   121.7   120.8  120.82  120.84  120.85  120.87  120.93     121
   120.7   120.9   120.3   120.7   120.4  119.85   119.3   118.9   116.3   114.2
   112.8   111.9  110.93   110.8   111.8   110.1     111   110.5   109.2   109.6
   112.6  112.49  112.18  110.87  111.11  112.19  112.19  112.27   112.2   112.2
  111.68  111.95  112.86  113.41  113.55  114.96   118.2   129.3
  2961.7  3004.7  3031.7  3101.7  3114.7  3134.7    3142    3162    3212  3271.7
  3391.7  3511.7  3661.7  3691.7  3761.7  3785.2  3807.1  3877.1  4097.1  4157.1
  4217.1  4237.1  4325.2  4337.1  4397.1  4447.1  4497.1  4537.1  4567.1  4597.1
    4649  4694.2  4743.1  4787.1  4820.7    4870  4870.1  4918.9 5064.79  5064.8
  5118.4  5121.7  5172.8  5213.3  5223.4  5275.1  5565.4  5830.1
   121.8   121.9  121.71  120.81  120.83   121.2   120.9  120.88   121.6  121.49
  121.25  121.02  120.31  120.71  120.41     120  119.73  118.91  116.31  115.45
  114.72  114.48   113.4  113.43  113.55  113.66  113.77  113.75  113.69  113.63
  113.69  113.79   113.9  113.94   113.9  113.89  114.49  114.57   114.5   113.9
  113.89  113.92  114.39  114.84  115.07  116.27  123.09   129.3
   121.8  121.74   121.7   120.8  120.82  120.84  120.85  120.87  120.93     121
   120.7   120.9   120.3   120.7   120.4  119.85   119.3   118.9   116.3   114.2
   112.8   111.9  110.93   110.8   111.8   110.1     111   110.5   109.2   109.6
   112.6  112.49  112.18  110.87  111.11  112.19  112.19  112.27   112.2   112.2
  111.68  111.95  112.86  113.41  113.55  114.96   118.2   129.3
Pier Skew, UpSta & Num, DnSta & Num=  ,4898.3, 2 ,4898.3, 2 , 0 , 0 , 0 ,,
     1.3     1.3
  102.21  113.24
     1.3     1.3
  103.48  114.51
Pier Skew, UpSta & Num, DnSta & Num=  ,4948.1, 2 ,4948.1, 2 , 0 , 0 , 0 ,,
     1.3     1.3
   95.94  113.23
     1.3     1.3
   97.21   114.5
Pier Skew, UpSta & Num, DnSta & Num=  ,4998.3, 2 ,4998.3, 2 , 0 , 0 , 0 ,,
     1.3     1.3
   92.95  113.24
     1.3     1.3
   94.22  114.51
Pier Skew, UpSta & Num, DnSta & Num=  ,5048.3, 2 ,5048.3, 2 , 0 , 0 , 0 ,,
     1.3     1.3
  102.32  113.22
     1.3     1.3
  103.59  114.49
Abutment Skew #Up #Dn= , 2 , 2
  4849.1    4929
  112.54  101.39
  4849.1    4929
  113.81  102.66
Abutment Skew #Up #Dn= , 2 , 2
  5027.9 5099.19
  100.89  112.62
  5027.9 5099.19
  102.16  113.89
BR Coef= 1 , 1 , 1 ,1.25, 0 ,,,.8,0,2,0,
WSPro=,,,, 1 ,,,, 0 ,,,, 0 ,,,,-1 ,-1 ,-1 , 0 , 0 , 0 , 0 , 0
BR U #Sta/Elev= 88
  2961.7  121.81  2964.7  121.81  3004.7  121.75  3031.7  121.71  3054.7  121.41
  3074.7  121.16  3101.7  120.81  3114.7  120.83  3134.7  120.85    3142  120.86
    3162  120.88    3212  120.94  3271.7  121.01  3391.7  120.71  3511.7  120.91
  3523.8  120.86  3661.7  120.31  3691.7  120.71  3745.2  120.48  3761.7  120.41
  3767.1  120.31  3785.2  119.86  3807.1  119.31  3877.1  118.91  4097.1  116.31
  4157.1  114.21  4217.1  112.81  4237.1  111.91  4325.2  110.94  4337.1  110.81
  4397.1  111.81  4447.1  110.11  4497.1  111.01    4512  110.82  4537.1  110.51
  4567.1  109.21  4597.1  109.61    4612  110.47    4649  112.61  4694.2   112.5
  4719.1  112.34  4743.1  112.19  4771.4  111.35  4787.1  110.88  4820.7  111.12
  4835.5  111.23  4849.1  110.34 4849.21  110.33  4849.3  110.32  4849.5  110.31
    4870  108.96  4881.9  108.18  4898.3  103.26  4918.9  102.01  4928.9  101.41
    4929   101.4  4941.6   96.76  4948.1   96.97    4965   98.13  4967.4   97.98
  4985.7   96.87  4991.9   95.07  4995.7   94.65  4998.3   94.03  5005.3   93.25
  5008.1   95.16  5015.8   96.31  5016.1   96.65  5019.4  100.38  5027.8  100.89
  5027.9   100.9  5048.3  103.41  5064.1  107.21  5064.8  107.27  5098.9  110.08
 5098.99  110.09  5099.1   110.1  5099.2   110.1  5118.4  111.69  5121.7  111.96
  5166.5  112.76  5172.8  112.87  5213.3  113.42  5223.4  113.56  5262.2  114.62
  5275.1  114.97  5565.4  118.21  5830.1  129.31
BR U #Mann= 4
  2961.7      .2  2964.7     .15  4835.5     .04  5121.7     .15
BR D #Sta/Elev= 87
  2961.7  121.81  2964.7  121.81  3004.7  121.75  3031.7  121.71  3054.7  121.41
  3074.7  121.16  3101.7  120.81  3114.7  120.83  3134.7  120.85    3142  120.86
    3162  120.88    3212  120.94  3271.7  121.01  3391.7  120.71  3511.7  120.91
  3523.8  120.86  3661.7  120.31  3691.7  120.71  3745.2  120.48  3761.7  120.41
  3767.1  120.31  3785.2  119.86  3807.1  119.31  3877.1  118.91  4097.1  116.31
  4157.1  114.21  4217.1  112.81  4237.1  111.91  4325.2  110.94  4337.1  110.81
  4397.1  111.81  4447.1  110.11  4497.1  111.01    4512  110.82  4537.1  110.51
  4567.1  109.21  4597.1  109.61    4612  110.47    4649  112.61  4694.2   112.5
  4719.1  112.34  4743.1  112.19  4771.4  111.35  4787.1  110.88  4820.7  111.12
  4835.5  111.23  4849.1  110.34 4849.21  110.33  4849.3  110.32  4849.5  110.31
    4870  108.96  4881.9  108.18  4898.3  103.26  4918.9  102.01  4928.9  101.41
    4929   101.4  4941.6   96.76  4948.1   96.97    4965   98.13  4967.4   97.98
  4985.7   96.87  4991.9   95.07  4995.7   94.65  5005.3   94.51  5008.1   95.16
  5015.8   96.31  5016.1   96.65  5019.4  100.38  5027.8  100.89  5027.9   100.9
  5048.3  103.41  5064.1  107.21  5064.8  107.27  5098.9  110.08 5098.99  110.09
  5099.1   110.1  5099.2   110.1  5118.4  111.69  5121.7  111.96  5166.5  112.76
  5172.8  112.87  5213.3  113.42  5223.4  113.56  5262.2  114.62  5275.1  114.97
  5565.4  118.21  5830.1  129.31
BR D #Mann= 4
  2961.7      .2  2964.7     .15  4835.5     .04  5121.7     .15
BC Design=,, 0 ,, 0 ,,,,,,
BC HTab HWMax=129.31

Type RM Length L Ch R = 1 ,7084.2  ,126.5,126.5,126.5
BEGIN DESCRIPTION:
Downstream Section of Bridge/Culvert/Weir
END DESCRIPTION:
XS GIS Cut Line= 5
      3072850.75      13971249.4      3072765.55      13970470.4
      3072831.33      13969762.2      3072860.82      13969212.1
      3072847.59       13968445.
#Sta/Elev= 30
  2961.7  121.81  2964.7  121.81  3101.7  120.81  3761.7  120.41  4097.1  116.31
  4237.1  111.91  4337.1  110.81  4397.1  111.81  4447.1  110.11  4497.1  111.01
  4567.1  109.21  4597.1  109.61    4649  112.61  4835.5  111.23  4881.9  108.18
  4898.3  103.26    4929   101.4  4941.6   96.76    4965   98.13  4985.7   96.87
  4995.7   94.65  5005.3   94.51  5015.8   96.31  5019.4  100.38  5048.3  103.41
  5064.1  107.21  5121.7  111.96  5275.1  114.97  5565.4  118.21  5830.1  129.31
#Mann= 5 ,-1 , 0
  2961.7      .2       0  2964.7     .15       0  4835.5     .05       0
  5121.7     .15       0  5830.1      .2       0
#XS Ineff= 2 , 0
       0    4839  113.85    5109       0  113.89
Permanent Ineff=
       F       F
Bank Sta=4835.5,5121.7
XS Rating Curve= 0
Exp/Cntr=.5,.3

Type RM Length L Ch R = 1 ,6957.7  ,1084.1,1024.3,717.7
BEGIN DESCRIPTION:
Cross Section Survey data from M100-00-00-X04
Cross Section XS04.1
END DESCRIPTION:
XS GIS Cut Line= 6
      3072877.81      13970717.9      3072889.58     13970447.15
      3072925.55     13969619.69      3072985.39     13969284.68
      3073034.36     13969040.77      3072989.88       13968593.
#Sta/Elev= 30
  3570.8   119.9  3680.8     120  3790.8   122.3  3840.8   121.8  3991.8   117.9
  4031.8   119.5  4061.8   117.8  4191.8   116.2  4291.8   112.8  4411.8   112.6
  4531.8     108  4591.8   110.2    4770   107.5    4870   108.4 4977.67  107.89
  4980.9  102.01  4992.5   95.83  4998.1   94.27    5007   95.64  5024.6  101.85
  5047.3  105.72  5060.4   107.1  5120.4   110.1  5230.4   113.2  5299.1   112.7
  5339.1   114.5  5409.1   114.9  5589.1   120.1  5619.1   123.3  5709.1   125.1
#Mann= 3 ,-1 , 0
  3570.8     .15       0 4977.67     .05       0  5047.3     .15       0
#XS Ineff= 2 , 0
       0    4605   112.5               0
Permanent Ineff=
       F       F
Bank Sta=4977.67,5047.3
XS Rating Curve= 0
Exp/Cntr=.3,.1

Type RM Length L Ch R = 1 ,5933.4  ,1706.86,2221.3,1674.54
BEGIN DESCRIPTION:
Cross Section 5933.4
Cross Section M100-00-00-X04
Cross Section XS04
END DESCRIPTION:
XS GIS Cut Line= 4
      3074273.44       13970038.      3074213.24      13969955.1
      3073684.17      13969459.1      3073494.87      13968609.9
#Sta/Elev= 30
  4450.3   119.5  4490.3   119.9  4552.8   118.7  4602.8   118.6  4732.8   115.9
  4772.8   114.4  4872.1  113.01  4923.5  111.45  4974.9  108.25  4980.9  100.24
  4992.5   94.06  4998.1    92.5    5007   93.87  5024.6  100.08  5047.3  103.95
  5112.3  105.03  5112.8   105.7  5142.8   107.7  5162.8   108.2    5468     106
    5568   104.1    5658   109.9    5718     112    5838   113.1    5868   112.6
    5988   115.9    6048   119.2    6078   119.6    6108   121.6    6148   122.9
#Mann= 4 , 1 , 0
  4450.3      .2       0  4450.3     .15       0  4974.9     .05       0
  5047.3     .15       0
Bank Sta=4974.9,5047.3
XS Rating Curve= 0
Exp/Cntr=.3,.1

Type RM Length L Ch R = 1 ,3712.1  ,952.37,1111.8,1099.64
BEGIN DESCRIPTION:
Cross Section 3712.1
Cross Section M100-00-00-X03
Cross Section XS03
END DESCRIPTION:
XS GIS Cut Line= 5
      3075851.74      13969383.6      3075629.92      13969125.9
      3075206.38      13968634.1       3074845.1      13968332.2
      3074561.82      13968144.3
#Sta/Elev= 30
  3753.6   119.7  3973.6   116.7  4193.6   118.5  4233.6   119.6  4283.6   119.8
  4373.6   122.2  4563.6   121.4  4633.6   117.2  4643.6   116.9  4742.7   110.1
  4792.7   105.1  4842.7     103  4892.7   103.8  4894.5  103.56  4954.2  104.34
  4979.6   99.61  4989.6    93.3    4990   92.82  4999.6   92.07  5009.9   92.52
  5010.4   93.29  5037.5  104.56  5094.5  103.58    5150  108.38  5162.7   110.2
  5192.7   112.5  5263.4   119.6  5313.4   122.7  5513.4   120.7  5553.4   120.5
#Mann= 4 , 1 , 0
  3753.6      .2       0  3753.6     .15       0  4954.2     .05       0
  5037.5     .15       0
Bank Sta=4954.2,5037.5
XS Rating Curve= 0
Exp/Cntr=.3,.1

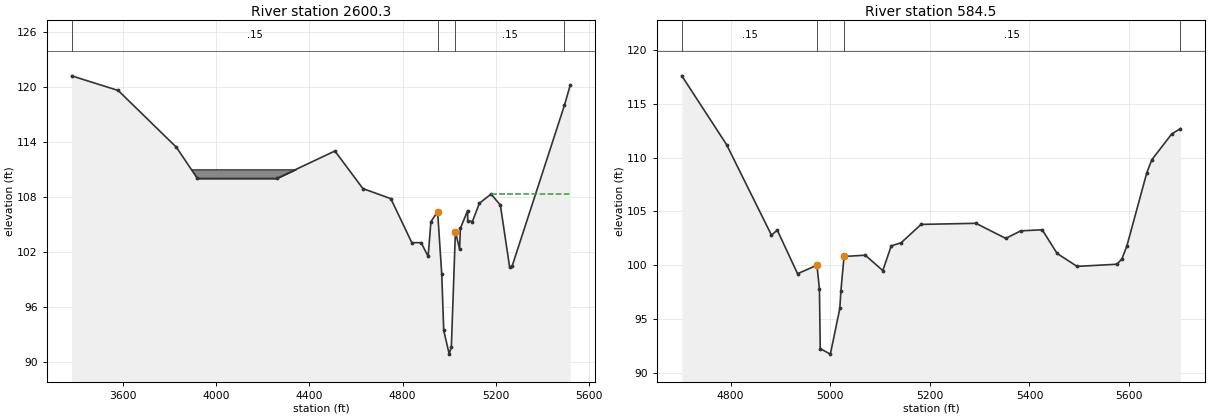
Type RM Length L Ch R = 1 ,2600.3  ,1758.21,2015.8,1976.66
BEGIN DESCRIPTION:
Cross Section 2600.3
Cross Section M100-00-00-X02
END DESCRIPTION:
XS GIS Cut Line= 2
      3076159.22      13969061.4      3075298.67      13967102.1
#Sta/Elev= 30
  3379.9   121.2  3579.9   119.6  3829.9   113.4  3919.9     110  4259.9     110
  4509.9     113  4629.9   108.9  4749.9   107.8  4839.9     103  4879.9     103
  4909.9   101.5  4921.9  105.29  4950.6  106.38  4968.3   99.58  4976.9   93.42
  5000.4   90.84  5009.6   91.66    5027  104.19    5045  102.29  5048.2  104.56
  5079.3  106.49  5079.9   105.4  5099.9   105.3  5129.9   107.3  5179.9   108.3
  5219.9   107.1  5259.9   100.3  5269.9   100.4  5494.8  117.98  5519.9   120.2
#Mann= 4 ,-1 , 0
  3379.9     .15       0  4950.6     .05       0    5027     .15       0
  5494.8      .1       0
#XS Ineff= 2 , 0
       0                    5180       0   108.3
Permanent Ineff=
       F       F
#Block Obstruct= 2 , 0
       0    4510     111               0
Bank Sta=4950.6,5027
XS Rating Curve= 0
Exp/Cntr=.3,.1

Type RM Length L Ch R = 1 ,584.5   ,0,0,0
BEGIN DESCRIPTION:
Cross Section XS01
Cross Section M100-00-00-X01
END DESCRIPTION:
XS GIS Cut Line= 4
      3077088.09       13968332.      3077204.51      13968156.7
      3077229.24      13967664.3       3076995.8      13967479.7
#Sta/Elev= 30
  4702.1   117.6  4792.1   111.2  4882.1   102.8  4893.7  103.27  4934.5   99.22
  4973.4  100.01  4978.4   97.78    4980   92.26  5000.3   91.75  5019.3   95.99
  5021.5   97.65  5027.8  100.82  5070.4  100.94  5105.6   99.51  5122.5   101.8
  5142.5   102.1  5182.5   103.8  5292.5   103.9  5352.5   102.5  5382.5   103.2
  5425.6   103.3  5455.6   101.1  5495.6    99.9  5575.6   100.1  5585.6   100.6
  5595.6   101.8  5635.6   108.6  5645.6   109.8  5685.6   112.2  5703.2   112.7
#Mann= 4 ,-1 , 0
  4702.1     .15       0  4973.4     .05       0  5027.8     .15       0
  5703.2      .2       0
Bank Sta=4973.4,5027.8
XS Rating Curve= 0
Exp/Cntr=.3,.1

Chan Stop Cuts=-1